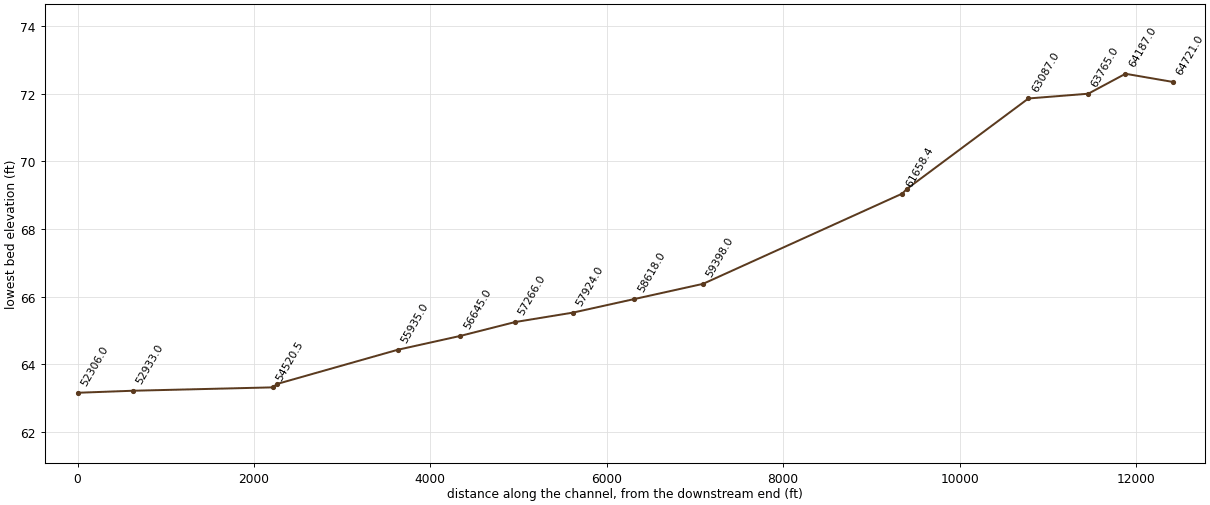
--- 04072003_Bear_Creek.prj (project) ---

Proj Title=Bear Creek
Current Plan=p02
Default Exp/Contr=.3,.1
English Units
Geom File=g01
Flow File=f02
Flow File=f01
Plan File=p02
Plan File=p01
Y Axis Title=Elevation
X Axis Title(PF)=Main Channel Distance
X Axis Title(XS)=Station
BEGIN DESCRIPTION:
END DESCRIPTION:
DSS Export Rating Curves= 0
DSS Export Rating Curve Sorted= 0
DSS Export Volume Flow Curves= 0
DXF OffsetX= 0
DXF OffsetY= 0
DXF ScaleX= 1
DXF ScaleY= 10

--- 04072003_Bear_Creek.p02 (plan) ---

Plan Title=Bear Creek FW
Version=Version 3.0.1  Mar 2001
Short Identifier=fw
Geom File=g01
Flow File=f02
Subcritical Flow
K Sum by GR= 0
Std Step Tol= 0.01
Critical Tol= 0.01
Num of Std Step Trials= 20
Max Error Tol= 0.3
Flow Tol Ratio= 0.001
Split Flow NTrial= 30
Split Flow Tol= 0.02
Split Flow Ratio= 0.02
Log Output Level= 0
Friction Slope Method= 1
Unsteady Friction Slope Method= 2
Parabolic Critical Depth
Global Vel Dist= 0 , 0 , 0
Global Log Level= 0
CheckData=True
Encroach Param= 0 ,0,0, 2
Encroach River=Main Stem
Encroach Reach=Reach - 1
Encroach Node=64721.0
       1    4918    5278
Encroach Node=64187.0
       1    4900    5300
Encroach Node=63765.0
       1    4800    5250
Encroach Node=63087.0
       1    4850    5300
Encroach Node=61705.7
       1    4940    5300
Encroach Node=61682.0
       1    4940    5300
Encroach Node=61658.4
       1    4940    5300
Encroach Node=59398.0
       1    4800    5500
Encroach Node=58618.0
       1    4800    5390
Encroach Node=57924.0
       1    4650    5320
Encroach Node=57266.0
       1    4600    5350
Encroach Node=56645.0
       1    4300    6100
Encroach Node=55935.0
       1    4600    6000
Encroach Node=54567.5
       1    4900    6000
Encroach Node=54544.0
       1    4900    6000
Encroach Node=54520.5
       1    4900    6000
Encroach Node=52933.0
       1    4640    5780
Encroach Node=52306.0
       1    4550    5600
Encroach Node=51597.0
       1    4500    5520
Encroach Node=51031.0
       1    4360    5410
Encroach Node=50287.0
       1    4260    5210
Encroach Node=49893.0
       1    4230    5180
Encroach Node=49288.0
       1    4300    5190
Encroach Node=48596.0
       1    4068    5369
Encroach Node=47944.0
       1    4075    5460
Encroach Node=47393.0
       1    4090    5520
Encroach Node=46950.0
       1    4175    5430
Encroach Node=44748.0
       1    4895    5070
Encroach Node=44733.0
       1    4895    5070
Encroach Node=44718.0
       1    4895    5070
Encroach Node=42741.0
       1    4755    5595
Encroach Node=41771.4
       1    4897    5095
Encroach Node=41745.0
       1    4897    5095
Encroach Node=41718.7
       1    4897    5095
Encroach Node=39410.0
       1    4600    5590
Encroach Node=38802.0
       1    4640    5620
Encroach Node=38384.0
       1    4635    5605
Encroach Node=37836.0
       1    4575    5690
Encroach Node=37166.0
       1    4650    5750
Encroach Node=36639.0
       1    4800    5490
Encroach Node=36111.0
       1    4820    5480
Encroach Node=35554.0
       1    4880    5450
Encroach Node=34806.8
       1    4920    5095
Encroach Node=34701.8
       1    4920    5095
Encroach Node=34596.8
       1    4920    5095
Encroach Node=33040.0
       1    4640    5370
Encroach Node=32524.0
       1    4635    5370
Encroach Node=32122.0
       1    4645    5365
Encroach Node=31155.0
       1    4916    5087
Encroach Node=31129.0
       1    4916    5087
Encroach Node=31103.0
       1    4916    5087
Encroach Node=29393.0
       1    4650    5370
Encroach Node=28435.0
       1    4680    5350
Encroach Node=27714.0
       1    4475    5105
Encroach Node=27204.0
       1    4680    5290
Encroach Node=26460.0
       1    4660    5250
Encroach Node=26014.0
       1    4750    5330
Encroach Node=25416.0
       1    4520    5110
Encroach Node=24913.0
       1    4585    5200
Encroach Node=24410.7
       1    4675    5300
Encroach Node=24387.6
       1    4675    5300
Encroach Node=24364.5
       1    4675    5300
Encroach Node=23395.0
       1    4550    5300
Encroach Node=22589.0
       1    4630    5425
Encroach Node=22166.0
       1    4640    5405
Encroach Node=21427.0
       1    4600    5200
Encroach Node=20799.0
       1    4600    5370
Encroach Node=20348.0
       1    4500    5203
Encroach Node=19769.0
       1    4645    5265
Encroach Node=19057.0
       1    4590    5230
Encroach Node=18436.0
       1    4590    5220
Encroach Node=17813.0
       1    4675    5340
Encroach Node=17300.0
       1    4595    5295
Encroach Node=16855.0
       1    4605    5320
Encroach Node=16449.0
       1    4615    5255
Encroach Node=15749.0
       1    4710    5340
Encroach Node=15042.0
       1    4580    5160
Encroach Node=14575.0
       1    4570    5120
Encroach Node=13883.0
       1    4900    5440
Encroach Node=13139.0
       1    4915    5450
Encroach Node=12334.0
       1    4650    5300
Encroach Node=11577.4
       1    4715    5285
Encroach Node=11557.0
       1    4715    5285
Encroach Node=11536.7
       1    4715    5285
Encroach Node=10070.0
       1    4545    5185
Encroach Node=9363.0
       1    4720    5415
Encroach Node=8861.0
       1    4650    5375
Encroach Node=8139.0
       1    4550    5280
Encroach Node=7147.0
       1    4740    5460
Encroach Node=6510.0
       1    4640    5360
Encroach Node=5887.0
       1    4510    5240
Encroach Node=5247.0
       1    4670    5530
Encroach Node=4861.0
       1    4595    5520
Encroach Node=3747.0
       1    4410    5300
Encroach Node=3368.0
       1    4370    5210
Encroach Node=2974.0
       1    4430    5210
Encroach Node=2205.0
       1    4650    5385
Encroach Node=1632.0
       1    4620    5320
Computation Interval=1HOUR
Output Interval=1HOUR
Run HTab= 0
Run UNet= 0
Run PostProcess= 0
UNET Theta= 1
UNET ZTol= 0.02
UNET ZSATol= 0.1
UNET MxIter= 20
UNET MaxInSteps= 20
UNET DtIC= 0
UNET DtMin= 0
UNET MaxCRTS= 20
UNET WFStab= 2
UNET SFStab= 1
UNET WFX= 1
UNET SFX= 1
UNET Convert EG Bridges=-1
UNET Use Existing IB Tables=-1
Instantaneous Interval=1HOUR
Write IC File= 0
Write Velocity= 0
Write Detailed= 0

--- 04072003_Bear_Creek.p01 (plan) ---

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Plan Title=Bear Creek
Short Identifier=Base Plan
Geom File=g01
Flow File=f01
Interactive Comp Mode
Encroach Param= -1, 0, 0, 0

--- 04072003_Bear_Creek.f02 (steady flow) ---

Flow Title=Bear_Creek_FW
Version=Version 3.0.1  Mar 2001
Number of Profiles= 2
Profile Names=100-YEAR,100-YEAR FW
River Rch & RM=Main Stem,Reach - 1       ,64721.0
    2260    2260
River Rch & RM=Main Stem,Reach - 1       ,59398
    2530    2530
River Rch & RM=Main Stem,Reach - 1       ,56645
    2570    2570
River Rch & RM=Main Stem,Reach - 1       ,52306
    2690    2690
River Rch & RM=Main Stem,Reach - 1       ,51597
    2820    2820
River Rch & RM=Main Stem,Reach - 1       ,50287
    5580    5580
River Rch & RM=Main Stem,Reach - 1       ,42741
    5750    5750
River Rch & RM=Main Stem,Reach - 1       ,39410
    6170    6170
River Rch & RM=Main Stem,Reach - 1       ,34806.8
    6600    6600
River Rch & RM=Main Stem,Reach - 1       ,26014
    6760    6760
River Rch & RM=Main Stem,Reach - 1       ,22589.0
    7040    7040
Boundary for River Rch & Prof#=Main Stem,Reach - 1       , 1
Up Type= 0
Dn Type= 1
Dn Known WS=46.77
Boundary for River Rch & Prof#=Main Stem,Reach - 1       , 2
Up Type= 0
Dn Type= 1
Dn Known WS=47.77
DSS Import GetInterval= 0
DSS Import GetPeak= 0
DSS Import FillOption= 0

--- 04072003_Bear_Creek.f01 (steady flow) ---

Flow Title= Bear Creek
Number of Profiles= 4
Profile Names=10-YEAR,50-YEAR,100-YEAR,500-YEAR
River Rch & RM=Main Stem,Reach - 1,64721
    1040    1840    2260    3470
River Rch & RM=Main Stem,Reach - 1,59398
    1170    2060    2530    3850
River Rch & RM=Main Stem,Reach - 1,56645
    1200    2090    2570    3910
River Rch & RM=Main Stem,Reach - 1,52306
    1260    2190    2690    4080
River Rch & RM=Main Stem,Reach - 1,51597
    1320    2310    2820    4280
River Rch & RM=Main Stem,Reach - 1,50287
    2360    4430    5580    9050
River Rch & RM=Main Stem,Reach - 1,42741
    2420    4550    5750    9360
River Rch & RM=Main Stem,Reach - 1,39410
    2560    4870    6170   10100
River Rch & RM=Main Stem,Reach - 1,34806.8
    2700    5190    6600   10900
River Rch & RM=Main Stem,Reach - 1,26014
    2750    5320    6760   11200
River Rch & RM=Main Stem,Reach - 1,22589.0
    2870    5540    7040   11600
Boundary for River Rch & Prof#=Main Stem,Reach - 1, 1
Up Type= 0
Dn Type= 3
Dn Slope= 0.00130
Boundary for River Rch & Prof#=Main Stem,Reach - 1, 2
Up Type= 0
Dn Type= 3
Dn Slope= 0.00130
Boundary for River Rch & Prof#=Main Stem,Reach - 1, 3
Up Type= 0
Dn Type= 3
Dn Slope= 0.00130
Boundary for River Rch & Prof#=Main Stem,Reach - 1, 4
Up Type= 0
Dn Type= 3
Dn Slope= 0.00130

--- 04072003_Bear_Creek.g01 (geometry) ---

Geom Title=Geom 01 by CodeH2 for Windows

River Reach=Main Stem,Reach - 1
Reach XY= 2
              .5             .95              .5             .05

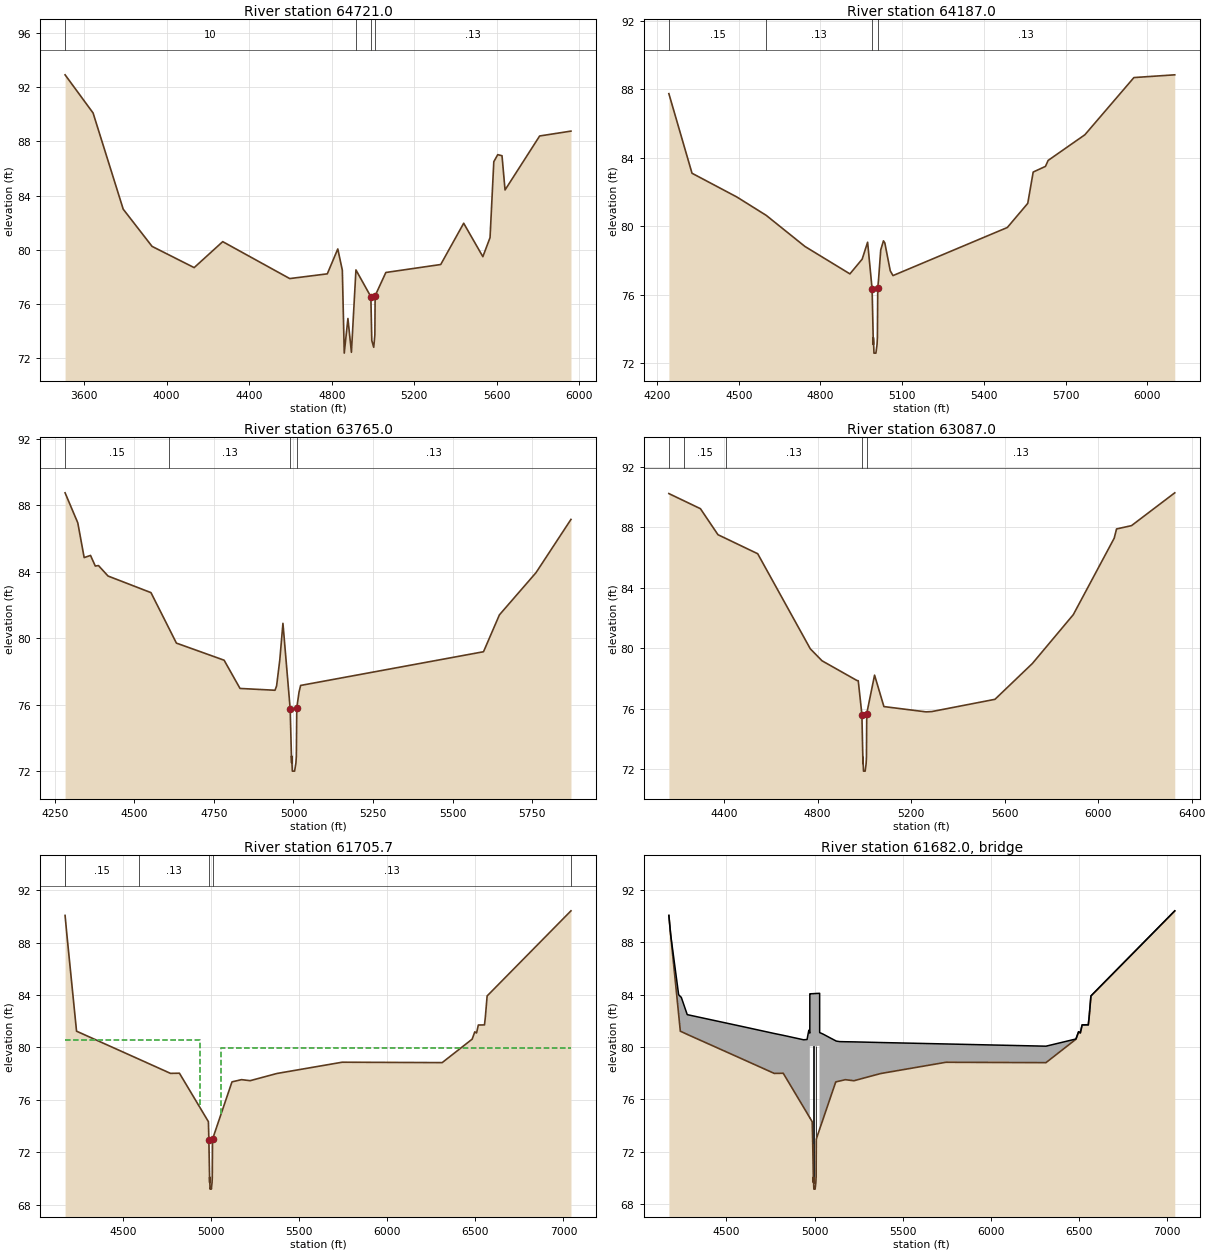
Type RM Length L Ch R = 1 ,64721.0,534,534,534
BEGIN DESCRIPTION:
Cross Section Bear Creek 85.0
END DESCRIPTION:
#Sta/Elev= 30
  3508.8   92.92  3644.4    90.1  3790.3   82.99    3930   80.24  4133.9   78.67
  4272.2   80.59  4596.7   77.86  4778.7   78.21  4829.5   80.05  4851.5   78.48
  4860.8   72.35  4878.6   74.91  4895.5   72.41  4917.4    78.5 4989.65   76.52
 4994.15   73.28 5003.55   72.78 5009.05   73.69 5010.35   76.59  5062.2   78.31
    5328    78.9  5439.2   81.95  5532.1   79.48  5566.9   80.89  5585.1    86.5
  5604.1   87.02  5624.8   86.94  5639.5   84.41  5807.1    88.4  5958.8   88.76
#Mann= 4 , 1 , 0
 3508.80      10       0  4917.4    0.13       0 4989.65    0.05       0
 5010.35    0.13       0
Bank Sta=4989.65,5010.35
Exp/Cntr=0.3,0.1

Type RM Length L Ch R = 1 ,64187.0,422,422,422
BEGIN DESCRIPTION:
Cross Section Bear Creek 84.0
END DESCRIPTION:
#Sta/Elev= 30
  4243.1   87.75  4328.1    83.1  4493.1   81.71  4600.6   80.64  4743.1   78.82
  4908.1   77.22  4953.1   78.08  4973.1   79.07 4989.65   76.33 4994.15   73.09
 4994.25    73.5 4996.45   72.59 5003.55   72.59 5007.65   73.08 5009.05    73.5
 5010.35    76.4  5013.1   76.85  5021.3   78.62  5031.3   79.15  5036.3   79.03
  5056.3    77.4  5066.3   77.12  5486.3   79.93  5561.3   81.34  5581.3   83.17
  5626.3    83.5  5636.3   83.85  5771.3   85.35  5951.3   88.69  6101.3   88.85
#Mann= 4 , 1 , 0
 4243.10    0.15       0  4600.6    0.13       0 4989.65    0.05       0
 5010.35    0.13       0
Bank Sta=4989.65,5010.35
Exp/Cntr=0.3,0.1

Type RM Length L Ch R = 1 ,63765.0,678,678,678
BEGIN DESCRIPTION:
Cross Section Bear Creek 83.0
END DESCRIPTION:
#Sta/Elev= 30
  4281.9   88.76  4321.9   86.95  4341.9   84.86  4361.9   84.99  4376.9   84.35
  4386.9   84.38  4416.9   83.75  4551.9   82.75  4608.3   80.61  4631.9   79.71
  4781.9   78.68  4831.9   76.98  4941.9   76.87  4946.9   77.13  4956.9   78.68
  4966.9    80.9 4989.65   75.74 4994.15    72.5 4994.25   72.91 4996.45      72
 5003.55      72 5007.65   72.49 5009.05   72.91 5010.35   75.81  5017.5   76.76
  5022.5   77.16  5597.5   79.19  5647.5   81.41  5762.5   83.95  5872.5   87.16
#Mann= 4 , 1 , 0
 4281.90    0.15       0  4608.3    0.13       0 4989.65    0.05       0
 5010.35    0.13       0
Bank Sta=4989.65,5010.35
Exp/Cntr=0.3,0.1

Type RM Length L Ch R = 1 ,63087.0,1381.35,1381.35,1381.35
BEGIN DESCRIPTION:
Cross Section Bear Creek 82.0
END DESCRIPTION:
#Sta/Elev= 29
    4164   90.22  4228.9   89.74    4299   89.22    4374    87.5  4406.4   87.26
    4544   86.24    4769   79.95    4819   79.16    4969   77.85    4974   77.84
 4989.65    75.6 4994.15   72.36 4994.25   72.77 4996.45   71.86 5003.55   71.86
 5007.65   72.35 5009.05   72.77 5010.35   75.67  5043.8   78.21  5083.8   76.13
  5263.8   75.78  5288.8    75.8  5558.8   76.61  5718.8   78.98  5893.8   82.21
  6068.8   87.27  6078.8   87.88  6142.8    88.1  6327.8   90.27
#Mann= 5 , 1 , 0
 4164.00    0.13       0  4228.9    0.15       0  4406.4    0.13       0
 4989.65    0.05       0 5010.35    0.13       0
Bank Sta=4989.65,5010.35
Exp/Cntr=0.5,0.3

Type RM Length L Ch R = 1 ,61705.7,47.3,47.3,47.3
BEGIN DESCRIPTION:
Upstream Section of Bridge/Culvert/Weir
END DESCRIPTION:
#Sta/Elev= 30
  4173.3   90.08  4183.3   88.63  4238.3   81.24  4594.3   79.09  4770.9   78.02
  4821.9   78.03  4986.2   74.33  4988.8   72.92  4993.3   69.68  4993.4   70.09
  4995.6   69.18  5001.6   69.34  5002.7   69.18  5006.8   69.67  5008.2   70.09
  5009.5   72.99  5119.9   77.37  5174.2   77.54  5222.7   77.46  5374.6   78.01
  5744.6   78.87    6312   78.84    6482   80.63    6497   81.19    6507    81.1
    6517   81.71    6552   81.72    6557   82.33    6567   83.93  7042.5   90.43
#Mann= 6 , 1 , 0
 4173.30     0.2       0  4173.3    0.15       0  4594.3    0.13       0
  4988.8    0.05       0  5009.5    0.13       0  7042.5     0.2       0
#XS Ineff= 2 , 0
       0    4940   80.56    5058       0   79.95
Bank Sta=4988.80,5009.50
Exp/Cntr=0.5,0.3

Type RM Length L Ch R = 3 ,61682.0,,,
BEGIN DESCRIPTION:
LA GRANGE RD
Structure ID: L_BEACR7
END DESCRIPTION:
Bridge Culvert--1,0,-1,-1, 0
Deck Dist Width WeirC Skew NumUp NumDn MinLoCord MaxHiCord MaxSubmerge Is_Ogee
10,27.3,2.6,,54,54,,,0.95,0,1,1,,
  4173.3  4183.3  4228.8  4238.3  4243.8  4277.5  4594.3  4770.9  4821.9    4937
    4957    4967 4972.41 4972.52  4972.6 4972.73 4972.84  4986.2  4986.3  4988.8
  4993.3  4993.4  4995.6  5001.6  5002.7  5006.8  5008.2  5009.5  5015.2  5015.3
 5027.69  5027.8  5028.3 5028.41 5028.52    5047  5087.4  5119.9  5122.4  5142.4
  5174.2  5222.7  5374.6  5744.6    6312    6482    6497    6507    6517  6543.8
    6552    6557    6567  7042.5
   90.06   88.61      84   83.87    83.8   82.48   81.56   81.04    80.9   80.56
   80.58   81.29   81.07   81.07   81.07   84.07   84.07   84.08   84.08   84.08
   84.08   84.08   84.09   84.09   84.09   84.09    84.1    84.1    84.1    84.1
   84.11   84.11   84.11   84.11   81.11      81   80.71   80.48   80.46   80.42
   80.41    80.4   80.35   80.24   80.07   80.62   81.18   81.09    81.7   81.71
    81.7   82.31   83.91   90.41
   90.05    88.6   82.49   81.21   81.18   80.97   79.06   77.99      78   75.41
   74.96   74.73   74.61   74.61   80.06   80.06   80.06   80.07   80.07   80.07
   80.07   80.07   80.08   80.08   80.08   80.08   80.09   80.09   80.09   80.09
    80.1   73.71   73.73   73.73   73.74   74.46   76.06   77.34   77.35   77.41
   77.51   77.43   77.98   78.84   78.81    80.6   81.16   81.07   81.68   81.69
   81.69    82.3    83.9    90.4
  4173.3  4183.3  4228.8  4238.3  4243.8  4277.5  4594.3  4770.9  4821.9    4937
    4957    4967 4972.41 4972.52  4972.6 4972.73 4972.84  4986.2  4986.3  4988.8
  4993.3  4993.4  4995.6  5001.6  5002.7  5006.8  5008.2  5009.5  5015.2  5015.3
 5027.69  5027.8  5028.3 5028.41 5028.52    5047  5087.4  5119.9  5122.4  5142.4
  5174.2  5222.7  5374.6  5744.6    6312    6482    6497    6507    6517  6543.8
    6552    6557    6567  7042.5
   90.06   88.61      84   83.87    83.8   82.48   81.56   81.04    80.9   80.56
   80.58   81.29   81.07   81.07   81.07   84.07   84.07   84.08   84.08   84.08
   84.08   84.08   84.09   84.09   84.09   84.09    84.1    84.1    84.1    84.1
   84.11   84.11   84.11   84.11   81.11      81   80.71   80.48   80.46   80.42
   80.41    80.4   80.35   80.24   80.07   80.62   81.18   81.09    81.7   81.71
    81.7   82.31   83.91   90.41
   89.95    88.5   82.39   81.11   81.08   80.87   78.96   77.89    77.9   75.31
   74.86   74.63   74.51   74.51   79.96   79.96   79.96   79.97   79.97   79.97
   79.97   79.97   79.98   79.98   79.98   79.98   79.99   79.99   79.99   79.99
      80   73.61   73.63   73.63   73.64   74.36   75.96   77.24   77.25   77.31
   77.41   77.33   77.88   78.74   78.71    80.5   81.06   80.97   81.58   81.59
   81.59    82.2    83.8    90.3
Pier Skew, UpSta & Num, DnSta & Num=,4993.3, 2 ,4993.3, 2 , 0 , 0 , 0 ,,
       1       1
   68.89   81.07
       1       1
   68.79   80.97
Pier Skew, UpSta & Num, DnSta & Num=,5008.2, 2 ,5008.2, 2 , 0 , 0 , 0 ,,
       1       1
   68.91   81.09
       1       1
   68.81   80.99
Abutment Skew #Up #Dn=, 2 , 2
 4972.40 4986.30
   80.06   74.25
 4972.40 4986.30
   79.96   74.15
Abutment Skew #Up #Dn=, 2 , 2
 5015.30 5027.89
   73.21   80.10
 5015.30 5027.89
   73.11   80.00
BR Coef= 1 , 1 , 0 ,1.25, 0 ,,,0.8,0,2,0,
Wspro=,,,, 1 ,,,, 0 ,,,, 0 ,,,,-1 ,-1 ,-1 , 0 , 0 , 0 , 0 , 0
BC Design=,, 0 ,, 0 ,,,,,,
BR U #Sta/Elev= 54
  4173.3   90.05  4183.3    88.6  4228.8   82.49  4238.3   81.21  4243.8   81.18
  4277.5   80.97  4594.3   79.06  4770.9   77.99  4821.9      78    4937   75.41
    4957   74.96    4967   74.73 4972.41   74.61 4972.52   74.61  4972.6   74.61
 4972.73    74.6 4972.84    74.6  4986.2    74.3  4986.3   74.25  4988.8   72.89
  4993.3   69.65  4993.4   70.06  4995.6   69.15  5001.6   69.31  5002.7   69.15
  5006.8   69.64  5008.2   70.06  5009.5   72.96  5015.2   73.21  5015.3   73.21
 5027.69    73.7  5027.8   73.71  5028.3   73.73 5028.41   73.73 5028.52   73.74
    5047   74.46  5087.4   76.06  5119.9   77.34  5122.4   77.35  5142.4   77.41
  5174.2   77.51  5222.7   77.43  5374.6   77.98  5744.6   78.84    6312   78.81
    6482    80.6    6497   81.16    6507   81.07    6517   81.68  6543.8   81.69
    6552   81.69    6557    82.3    6567    83.9  7042.5    90.4
BR U #Mann= 6
 4173.30     0.2  4173.3    0.15  4594.3    0.13  4988.8    0.05  5009.5    0.13
  7042.5     0.2
BR U Banks=4988.80,5009.50
BR D #Sta/Elev= 54
  4173.3   89.95  4183.3    88.5  4228.8   82.39  4238.3   81.11  4243.8   81.08
  4277.5   80.87  4594.3   78.96  4770.9   77.89  4821.9    77.9    4937   75.31
    4957   74.86    4967   74.63 4972.41   74.51 4972.52   74.51  4972.6   74.51
 4972.73    74.5 4972.84    74.5  4986.2    74.2  4986.3   74.15  4988.8   72.79
  4993.3   69.55  4993.4   69.96  4995.6   69.05  5001.6   69.21  5002.7   69.05
  5006.8   69.54  5008.2   69.96  5009.5   72.86  5015.2   73.11  5015.3   73.11
 5027.69    73.6  5027.8   73.61  5028.3   73.63 5028.41   73.63 5028.52   73.64
    5047   74.36  5087.4   75.96  5119.9   77.24  5122.4   77.25  5142.4   77.31
  5174.2   77.41  5222.7   77.33  5374.6   77.88  5744.6   78.74    6312   78.71
    6482    80.5    6497   81.06    6507   80.97    6517   81.58  6543.8   81.59
    6552   81.59    6557    82.2    6567    83.8  7042.5    90.3
BR D #Mann= 6
 4173.30     0.2  4173.3    0.15  4594.3    0.13  4988.8    0.05  5009.5    0.13
  7042.5     0.2
BR D Banks=4988.80,5009.50

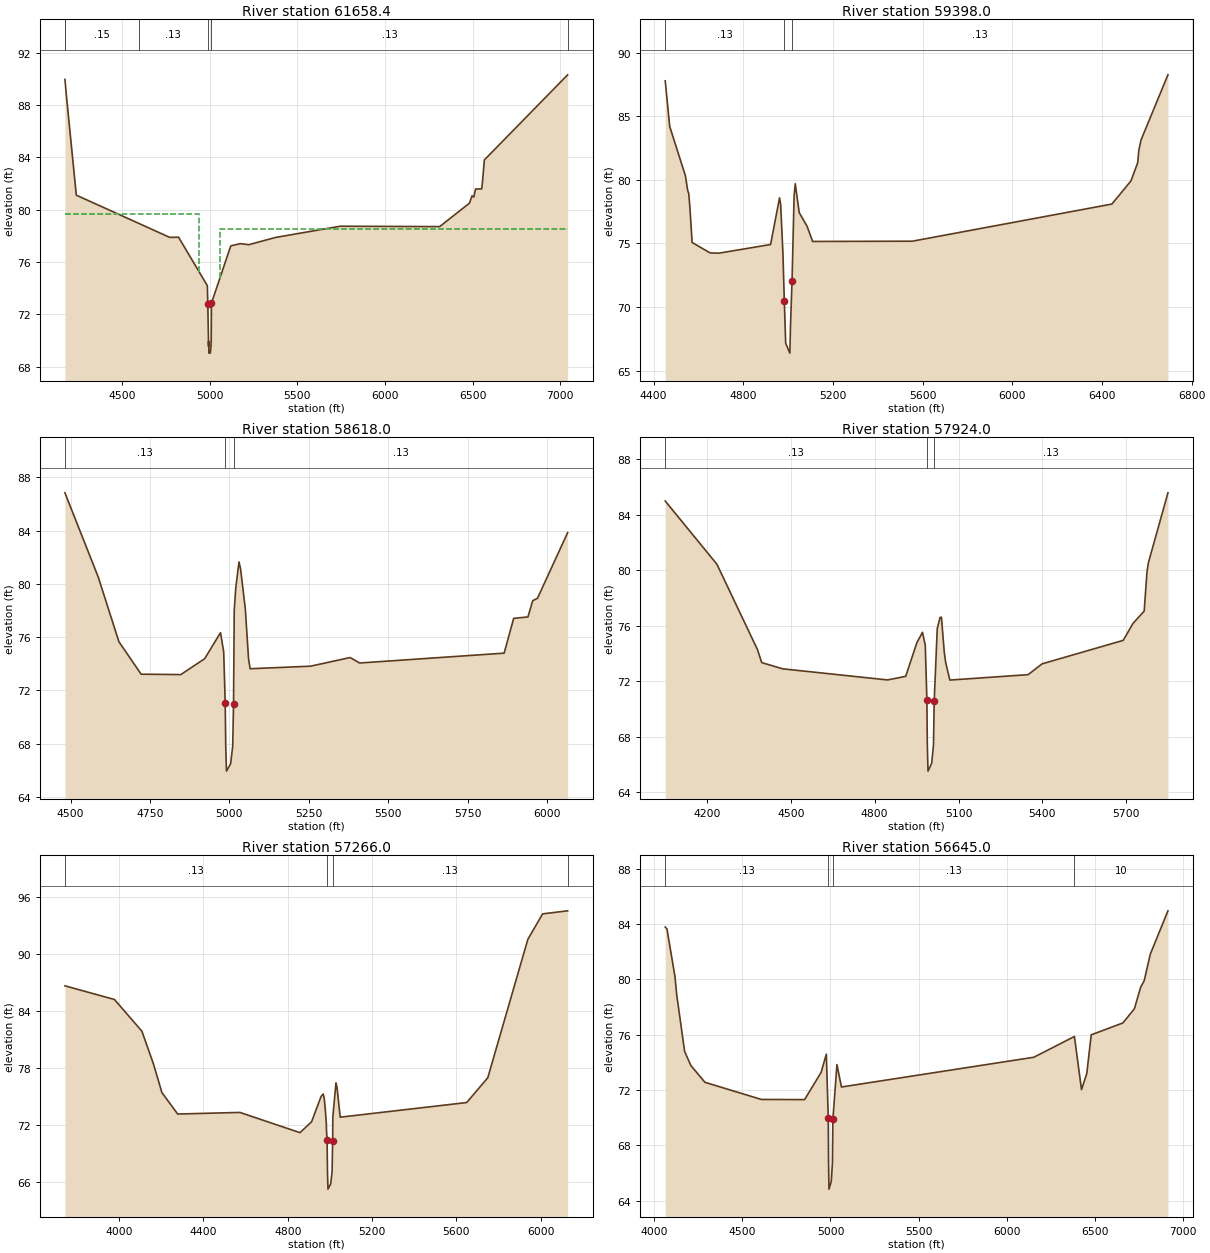
Type RM Length L Ch R = 1 ,61658.4,2260.35,2260.35,2260.35
BEGIN DESCRIPTION:
Downstream Section of Bridge/Culvert/Weir
END DESCRIPTION:
#Sta/Elev= 30
  4173.3   89.95  4183.3    88.5  4238.3   81.11  4594.3   78.96  4770.9   77.89
  4821.9    77.9  4986.2    74.2  4988.8   72.79  4993.3   69.55  4993.4   69.96
  4995.6   69.05  5001.6   69.21  5002.7   69.05  5006.8   69.54  5008.2   69.96
  5009.5   72.86  5119.9   77.24  5174.2   77.41  5222.7   77.33  5374.6   77.88
  5744.6   78.74    6312   78.71    6482    80.5    6497   81.06    6507   80.97
    6517   81.58    6552   81.59    6557    82.2    6567    83.8  7042.5    90.3
#Mann= 6 , 1 , 0
 4173.30     0.2       0  4173.3    0.15       0  4594.3    0.13       0
  4988.8    0.05       0  5009.5    0.13       0  7042.5     0.2       0
#XS Ineff= 2 , 0
       0    4940    79.7    5058       0    78.5
Bank Sta=4988.80,5009.50
Exp/Cntr=0.5,0.3

Type RM Length L Ch R = 1 ,59398.0,780,780,780
BEGIN DESCRIPTION:
Cross Section Bear Creek 79.0
END DESCRIPTION:
#Sta/Elev= 30
  4451.5   87.79  4471.5    84.2  4541.5   80.33  4551.5   79.19  4556.5   78.91
  4561.5   77.85  4571.5   75.08  4651.5   74.26  4691.5   74.24  4921.5   74.92
  4961.5   78.59  4966.5   78.05  4976.5   74.28  4982.8   70.47  4988.9   67.16
  5007.4   66.38  5010.4   68.52  5017.2   72.06  5026.5   78.76  5031.5    79.7
  5049.2   77.43  5084.2   76.36  5109.2   75.16  5554.2   75.18  6444.2    78.1
  6529.2   79.92  6559.2   81.35  6564.2   82.31  6574.2   83.14  6694.2   88.26
#Mann= 3 , 1 , 0
 4451.50    0.13       0  4982.8    0.05       0  5017.2    0.13       0
Bank Sta=4982.80,5017.20
Exp/Cntr=0.3,0.1

Type RM Length L Ch R = 1 ,58618.0,694,694,694
BEGIN DESCRIPTION:
Cross Section Bear Creek 78.0
END DESCRIPTION:
#Sta/Elev= 30
  4482.1   86.83  4587.1    80.5  4652.1   75.65  4722.1   73.21  4847.1   73.18
  4922.1   74.37  4972.1   76.33  4982.1   74.89  4986.9   71.06  4988.5    67.9
  4990.9   65.93    5004   66.49  5010.5   67.81  5013.1   70.98  5015.3   78.03
  5020.3   79.73  5030.3   81.64  5035.3   81.11  5050.3   78.09  5060.3   74.39
  5065.3   73.62  5255.3   73.81  5380.3   74.46  5410.3   74.05  5865.3   74.79
  5895.3    77.4  5940.3   77.51  5955.3   78.73  5970.3   78.91  6065.3   83.84
#Mann= 3 , 1 , 0
 4482.10    0.13       0  4986.9    0.05       0  5013.1    0.13       0
Bank Sta=4986.90,5013.10
Exp/Cntr=0.3,0.1

Type RM Length L Ch R = 1 ,57924.0,658,658,658
BEGIN DESCRIPTION:
Cross Section Bear Creek 77.0
END DESCRIPTION:
#Sta/Elev= 30
  4051.2   84.99  4236.2   80.43  4381.2   74.28  4396.2   73.35  4471.2    72.9
  4846.2    72.1  4911.2   72.36  4951.2   74.79  4971.2   75.53  4981.2   74.59
  4986.9   70.66  4988.5    67.5  4990.9   65.53    5004   66.09  5010.5   67.41
  5013.1   70.58    5024    75.8    5034    76.6    5039   76.62    5049   74.12
    5054   73.37    5069   72.09    5349   72.48    5399   73.26    5689   74.95
    5724   76.17    5764   77.06    5774   79.87    5779   80.54    5849   85.58
#Mann= 3 , 1 , 0
 4051.20    0.13       0  4986.9    0.05       0  5013.1    0.13       0
Bank Sta=4986.90,5013.10
Exp/Cntr=0.3,0.1

Type RM Length L Ch R = 1 ,57266.0,621,621,621
BEGIN DESCRIPTION:
Cross Section Bear Creek 76.0
END DESCRIPTION:
#Sta/Elev= 30
  3743.3   86.64  3978.3    85.2  4108.3   81.87  4163.3   78.42  4203.3   75.41
  4278.3   73.15  4573.3   73.32  4858.3   71.19  4913.3   72.34  4958.3      75
  4968.3   75.26  4973.3   74.79  4978.3   73.63  4983.3   72.11    4984   71.41
  4986.9   70.38  4988.5   67.22  4990.9   65.25    5004   65.81  5010.5   67.13
  5013.1    70.3    5014   72.84    5029   76.43    5034   75.94    5049   72.82
    5649   74.36    5749   76.97    5939   91.53    6009   94.21  6127.8   94.53
#Mann= 4 , 1 , 0
 3743.30    0.13       0  4986.9    0.05       0  5013.1    0.13       0
  6127.8     0.2       0
Bank Sta=4986.90,5013.10
Exp/Cntr=0.3,0.1

Type RM Length L Ch R = 1 ,56645.0,710,710,710
BEGIN DESCRIPTION:
Cross Section CCX_L76
Located At: CCX_L76 CNTRL
END DESCRIPTION:
#Sta/Elev= 30
  4063.1   83.78  4073.1   83.63  4118.1   80.22  4128.1    78.9  4173.1   74.79
  4208.1   73.78  4288.1   72.56  4608.1   71.32  4853.1   71.31  4946.6   73.27
  4976.5   74.59  4987.4   69.97    4989   66.81  4991.4   64.84  5004.5    65.4
    5011   66.72  5013.6   69.89  5036.5   73.84  5062.1   72.22  6153.1   74.37
  6382.9   75.87  6423.1   72.03  6453.1    73.2  6478.1   75.99  6658.1   76.85
  6723.1   77.88  6758.1   79.42  6778.1   79.89  6813.1   81.82  6913.1   84.95
#Mann= 4 , 1 , 0
 4063.10    0.13       0  4987.4    0.05       0  5013.6    0.13       0
  6382.9      10       0
Bank Sta=4987.40,5013.60
Exp/Cntr=0.3,0.1

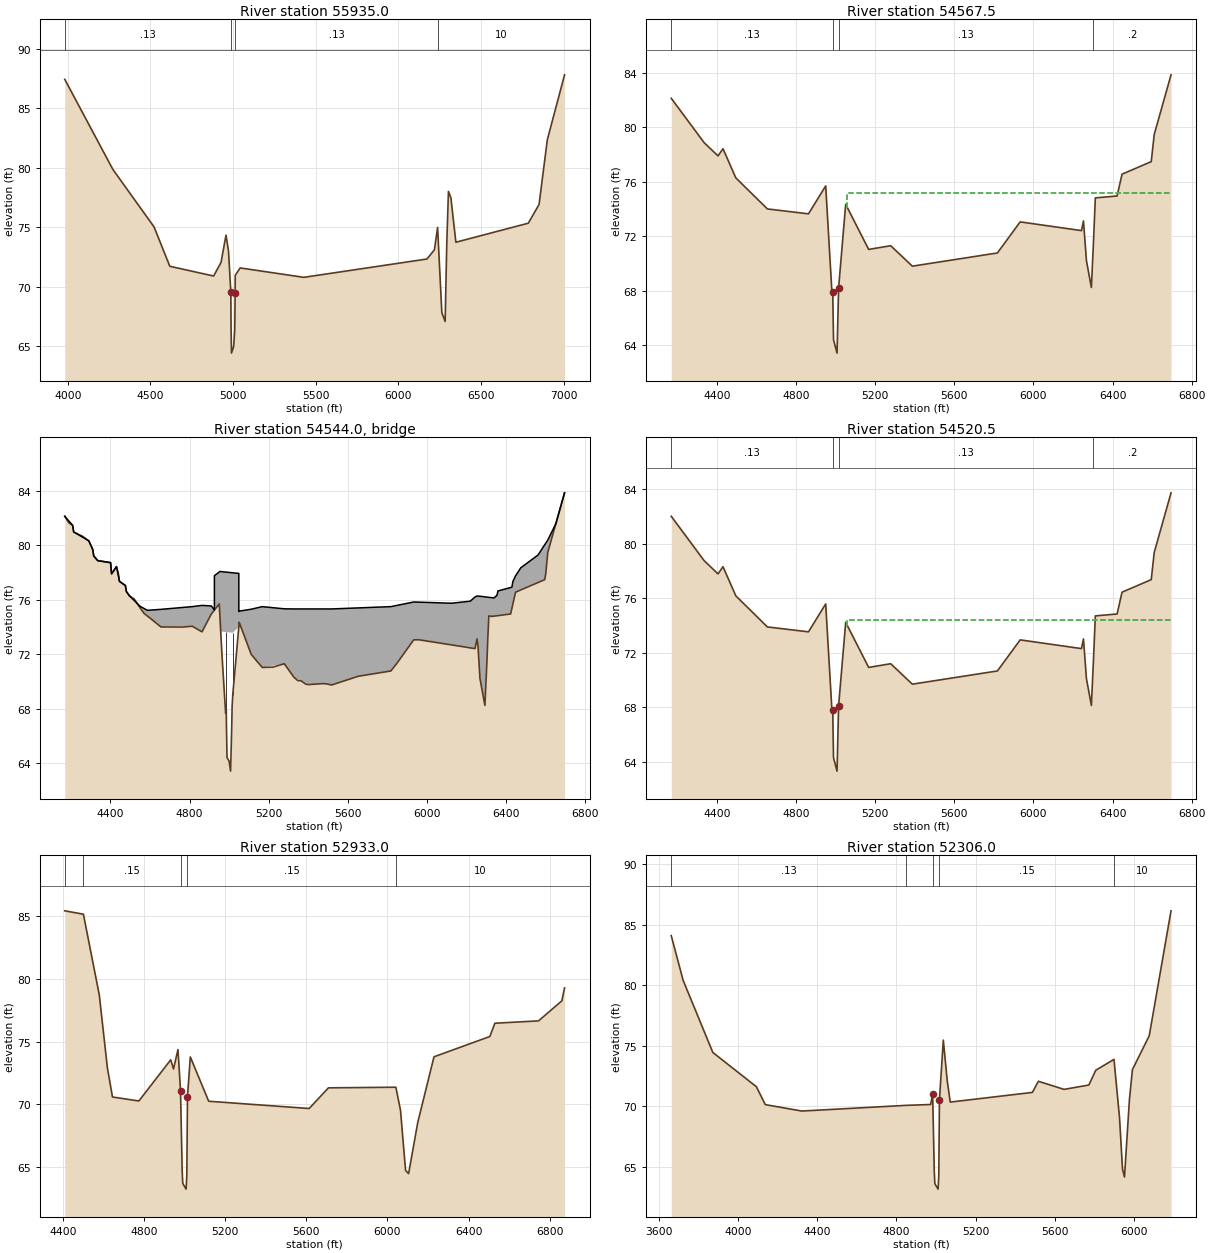
Type RM Length L Ch R = 1 ,55935.0,1367.5,1367.5,1367.5
BEGIN DESCRIPTION:
Cross Section Bear Creek 75.0
END DESCRIPTION:
#Sta/Elev= 30
  3982.3   87.44  4272.8   79.88  4522.8   75.03  4617.8   71.73  4882.8   70.91
  4927.8   72.06  4957.8   74.35  4972.8   73.02  4986.9   69.56  4988.5    66.4
  4990.9   64.43    5004   64.99  5010.5   66.31  5013.1   69.48  5013.6   70.97
  5043.6   71.59  5428.6    70.8  6173.6   72.34  6218.6   73.11    6238   74.99
  6263.6   67.84  6283.6   67.09  6293.6    73.7  6303.6   78.02  6318.6   77.47
  6348.6   73.75  6786.8   75.35  6851.8   76.92  6901.8   82.36  7006.1   87.82
#Mann= 4 , 1 , 0
 3982.30    0.13       0  4986.9    0.05       0  5013.1    0.13       0
    6238      10       0
Bank Sta=4986.90,5013.10
Exp/Cntr=0.5,0.3

Type RM Length L Ch R = 1 ,54567.5,47,47,47
BEGIN DESCRIPTION:
Upstream Section of Bridge/Culvert/Weir
END DESCRIPTION:
#Sta/Elev= 30
  4169.3   82.12  4335.8   78.86  4405.8   77.89  4430.8   78.42  4495.8   76.28
  4655.3      74  4863.1   73.64  4950.1   75.69  4982.5   67.66  4985.7   67.92
  4989.5   64.41  5007.4   63.42  5015.2   68.18  5051.1   74.34  5167.2   71.03
  5278.7    71.3  5388.1    69.8  5818.1   70.77  5933.1   73.05  6243.1   72.41
  6253.1   73.12  6268.1   70.21  6293.1   68.24  6303.6   71.55  6313.1   74.81
  6423.1   74.95  6448.1   76.55  6595.7   77.47  6610.7   79.46  6695.7   83.84
#Mann= 4 , 1 , 0
 4169.30    0.13       0  4985.7   0.047       0  5015.2    0.13       0
  6303.6     0.2       0
#XS Ineff= 2 , 0
       0    4948    75.2    5060       0    75.2
Bank Sta=4985.70,5015.20
Exp/Cntr=0.5,0.3

Type RM Length L Ch R = 3 ,54544.0,,,
BEGIN DESCRIPTION:
OLD JASON ROAD
Structure ID: L_BEACR6
END DESCRIPTION:
Bridge Culvert--1,0,-1,-1, 0
Deck Dist Width WeirC Skew NumUp NumDn MinLoCord MaxHiCord MaxSubmerge Is_Ogee
10,27,2.6,, 60, 60,,,0.95,0,1,1,,
  4169.3  4209.3  4214.3  4290.8  4310.8  4315.8  4335.8  4400.8  4405.8  4430.8
  4445.8  4475.8  4480.8  4495.8  4550.3  4586.9  4655.3  4813.7  4863.1  4909.8
 4925.58 4925.69  4950.1 4953.95 4960.01  4960.1  5018.6 5049.09  5049.2  5051.1
    5112  5167.2  5278.7  5328.1  5403.1  5518.1  5818.1  5933.1  6124.8    6219
  6243.1  6253.1  6258.1  6268.1  6293.1  6313.1    6339    6354    6359  6423.1
  6429.4  6434.4  6448.1  6474.4  6561.8  6595.7  6600.7  6610.7  6651.8  6695.7
   82.12   81.45   80.97   80.32   79.68   79.21   78.87   78.72    77.9   78.43
   77.35   77.04    76.6   76.29   75.51   75.22   75.29   75.49   75.58   75.54
   75.25   77.76   78.03   78.07   78.06   78.06   77.97   77.93   75.13   75.16
    75.3   75.49   75.33   75.32   75.32   75.32   75.49   75.83   75.74   75.89
    76.2   76.27   76.26   76.25   76.21   76.17   76.13   76.32   76.64   76.89
   76.92   77.33   77.75   78.34   79.28   80.04   80.15   80.37   81.58   83.84
   82.12   81.44   80.96   80.31   79.67    79.2   78.86   78.71   77.89   78.42
   77.34   77.03   76.59   76.28   75.39    74.8      74   74.05   73.64   74.94
   75.24   75.24   75.69   74.65      73   73.66   73.57   74.01   74.03   74.34
   71.98   71.03    71.3    70.3   69.77   69.74   70.77   73.05   72.68   72.46
   72.41   73.12   72.59   70.21   68.24   74.81   74.79   74.82   74.83   74.95
   75.35   75.67   76.55   76.71   77.26   77.47    77.9   79.46   81.58   83.84
  4169.3  4209.3  4214.3  4290.8  4310.8  4315.8  4335.8  4400.8  4405.8  4430.8
  4445.8  4475.8  4480.8  4495.8  4550.3  4586.9  4655.3  4813.7  4863.1  4909.8
 4925.58 4925.69  4950.1 4953.95 4960.01  4960.1  5018.6 5049.09  5049.2  5051.1
    5112  5167.2  5278.7  5328.1  5403.1  5518.1  5818.1  5933.1  6124.8    6219
  6243.1  6253.1  6258.1  6268.1  6293.1  6313.1    6339    6354    6359  6423.1
  6429.4  6434.4  6448.1  6474.4  6561.8  6595.7  6600.7  6610.7  6651.8  6695.7
   82.12   81.45   80.97   80.32   79.68   79.21   78.87   78.72    77.9   78.43
   77.35   77.04    76.6   76.29   75.51   75.22   75.29   75.49   75.58   75.54
   75.25   77.76   78.03   78.07   78.06   78.06   77.97   77.93   75.13   75.16
    75.3   75.49   75.33   75.32   75.32   75.32   75.49   75.83   75.74   75.89
    76.2   76.27   76.26   76.25   76.21   76.17   76.13   76.32   76.64   76.89
   76.92   77.33   77.75   78.34   79.28   80.04   80.15   80.37   81.58   83.84
   82.02   81.34   80.86   80.21   79.57    79.1   78.76   78.61   77.79   78.32
   77.24   76.93   76.49   76.18   75.29    74.7    73.9   73.95   73.54   74.84
   75.14   75.14   75.59   74.55    72.9   73.56   73.47   73.91   73.93   74.24
   71.88   70.93    71.2    70.2   69.67   69.64   70.67   72.95   72.58   72.36
   72.31   73.02   72.49   70.11   68.14   74.71   74.69   74.72   74.73   74.85
   75.25   75.57   76.45   76.61   77.16   77.37    77.8   79.36   81.48   83.74
Pier Skew, UpSta & Num, DnSta & Num=,4982.5, 2 ,4982.5, 2 , 0 , 0 , 0 ,,
       1       1
    66.7   74.63
       1       1
    66.6   74.53
Pier Skew, UpSta & Num, DnSta & Num=,5018.6, 2 ,5018.6, 2 , 0 , 0 , 0 ,,
       1       1
   67.91   74.58
       1       1
   67.81   74.48
BR Coef= 1 , 1 , 0 ,1.25, 0 ,,,0.8,0,2,0,
Wspro=,,,, 1 ,,,, 0 ,,,, 0 ,,,,-1 ,-1 ,-1 , 0 , 0 , 0 , 0 , 0
BC Design=,, 0 ,, 0 ,,,,,,
BR U #Sta/Elev= 134
  4169.3   82.12  4189.3   81.65  4204.7   81.49  4209.3   81.44  4214.3   80.96
  4254.7   80.68  4259.3   80.65  4264.7   80.59  4290.8   80.31  4309.7   79.71
  4310.8   79.67  4315.8    79.2  4334.7   78.88  4335.8   78.86  4379.7   78.76
  4384.3   78.75  4400.8   78.71  4405.8   77.89  4424.3   78.28  4430.8   78.42
  4440.8   77.87  4445.8   77.34  4471.9   77.07  4475.8   77.03  4480.8   76.59
  4495.8   76.28  4496.9   76.27  4520.3   76.05  4550.3   75.39  4570.3   74.99
  4586.9    74.8  4611.9   74.51  4655.3      74  4762.9   73.99  4763.2   73.99
  4812.9   74.05  4813.7   74.05  4862.9   73.64  4863.1   73.64  4909.1   74.93
  4909.8   74.94 4925.58   75.24 4925.69   75.24  4925.8   75.24  4950.1   75.69
 4953.73   74.71 4953.84   74.68 4953.95   74.65 4960.01      73  4960.1   72.98
  4960.2   72.95  4963.2   72.14  4982.5   67.66  4985.7   67.92  4986.7   66.62
  4989.5   64.41  4999.8   64.16  5007.4   63.42  5013.2   66.65  5015.2   68.18
  5018.6   69.04 5048.98   73.99 5049.09   74.01  5049.2   74.03  5051.1   74.34
  5057.4    74.1 5057.49   74.09  5057.6   74.09  5057.7   74.08  5110.2   72.05
    5112   71.98  5167.2   71.03  5169.3   71.03  5221.1   71.05  5221.3   71.05
  5278.7    71.3  5280.9   71.26  5328.1    70.3  5348.1   70.06  5363.1   70.05
  5388.1    69.8  5403.1   69.77  5473.1   69.84  5493.1   69.82  5518.1   69.74
  5653.1   70.38  5804.8   70.74  5818.1   70.77  5824.8    70.9  5848.1   71.33
  5864.8   71.67  5884.8   72.07  5933.1   73.05  5958.1   73.06  6059.8   72.83
  6084.8   72.77  6094.8   72.75  6124.8   72.68  6154.8   72.61    6189   72.53
    6204    72.5    6219   72.46  6243.1   72.41    6249   72.83  6253.1   73.12
  6258.1   72.59  6268.1   70.21  6293.1   68.24  6303.1   71.36  6303.6   71.55
  6308.1   73.29  6313.1   74.81  6328.1   74.77    6339   74.79    6354   74.82
    6359   74.83    6404   74.91  6423.1   74.95  6429.4   75.35  6434.4   75.67
  6448.1   76.55  6454.4   76.59  6474.4   76.71  6499.4   76.87  6514.4   76.96
  6516.8   76.98  6561.8   77.26  6595.7   77.47  6600.7    77.9  6610.7   79.46
  6626.8   80.29  6641.8   81.06  6651.8   81.58  6695.7   83.84
BR U #Mann= 4
 4169.30    0.13  4985.7   0.047  5015.2    0.13  6303.6     0.2
BR U Banks=4985.70,5015.20
BR D #Sta/Elev= 134
  4169.3   82.02  4189.3   81.55  4204.7   81.39  4209.3   81.34  4214.3   80.86
  4254.7   80.58  4259.3   80.55  4264.7   80.49  4290.8   80.21  4309.7   79.61
  4310.8   79.57  4315.8    79.1  4334.7   78.78  4335.8   78.76  4379.7   78.66
  4384.3   78.65  4400.8   78.61  4405.8   77.79  4424.3   78.18  4430.8   78.32
  4440.8   77.77  4445.8   77.24  4471.9   76.97  4475.8   76.93  4480.8   76.49
  4495.8   76.18  4496.9   76.17  4520.3   75.95  4550.3   75.29  4570.3   74.89
  4586.9    74.7  4611.9   74.41  4655.3    73.9  4762.9   73.89  4763.2   73.89
  4812.9   73.95  4813.7   73.95  4862.9   73.54  4863.1   73.54  4909.1   74.83
  4909.8   74.84 4925.58   75.14 4925.69   75.14  4925.8   75.14  4950.1   75.59
 4953.73   74.61 4953.84   74.58 4953.95   74.55 4960.01    72.9  4960.1   72.88
  4960.2   72.85  4963.2   72.04  4982.5   67.56  4985.7   67.82  4986.7   66.52
  4989.5   64.31  4999.8   64.06  5007.4   63.32  5013.2   66.55  5015.2   68.08
  5018.6   68.94 5048.98   73.89 5049.09   73.91  5049.2   73.93  5051.1   74.24
  5057.4      74 5057.49   73.99  5057.6   73.99  5057.7   73.98  5110.2   71.95
    5112   71.88  5167.2   70.93  5169.3   70.93  5221.1   70.95  5221.3   70.95
  5278.7    71.2  5280.9   71.16  5328.1    70.2  5348.1   69.96  5363.1   69.95
  5388.1    69.7  5403.1   69.67  5473.1   69.74  5493.1   69.72  5518.1   69.64
  5653.1   70.28  5804.8   70.64  5818.1   70.67  5824.8    70.8  5848.1   71.23
  5864.8   71.57  5884.8   71.97  5933.1   72.95  5958.1   72.96  6059.8   72.73
  6084.8   72.67  6094.8   72.65  6124.8   72.58  6154.8   72.51    6189   72.43
    6204    72.4    6219   72.36  6243.1   72.31    6249   72.73  6253.1   73.02
  6258.1   72.49  6268.1   70.11  6293.1   68.14  6303.1   71.26  6303.6   71.45
  6308.1   73.19  6313.1   74.71  6328.1   74.67    6339   74.69    6354   74.72
    6359   74.73    6404   74.81  6423.1   74.85  6429.4   75.25  6434.4   75.57
  6448.1   76.45  6454.4   76.49  6474.4   76.61  6499.4   76.77  6514.4   76.86
  6516.8   76.88  6561.8   77.16  6595.7   77.37  6600.7    77.8  6610.7   79.36
  6626.8   80.19  6641.8   80.96  6651.8   81.48  6695.7   83.74
BR D #Mann= 4
 4169.30    0.13  4985.7   0.047  5015.2    0.13  6303.6     0.2
BR D Banks=4985.70,5015.20

Type RM Length L Ch R = 1 ,54520.5,1587.5,1587.5,1587.5
BEGIN DESCRIPTION:
Downstream Section of Bridge/Culvert/Weir
END DESCRIPTION:
#Sta/Elev= 30
  4169.3   82.02  4335.8   78.76  4405.8   77.79  4430.8   78.32  4495.8   76.18
  4655.3    73.9  4863.1   73.54  4950.1   75.59  4982.5   67.56  4985.7   67.82
  4989.5   64.31  5007.4   63.32  5015.2   68.08  5051.1   74.24  5167.2   70.93
  5278.7    71.2  5388.1    69.7  5818.1   70.67  5933.1   72.95  6243.1   72.31
  6253.1   73.02  6268.1   70.11  6293.1   68.14  6303.6   71.45  6313.1   74.71
  6423.1   74.85  6448.1   76.45  6595.7   77.37  6610.7   79.36  6695.7   83.74
#Mann= 4 , 1 , 0
 4169.30    0.13       0  4985.7   0.047       0  5015.2    0.13       0
  6303.6     0.2       0
#XS Ineff= 2 , 0
       0    4948    74.4    5060       0    74.4
Bank Sta=4985.70,5015.20
Exp/Cntr=0.5,0.3

Type RM Length L Ch R = 1 ,52933.0,627,627,627
BEGIN DESCRIPTION:
Cross Section CCX_L75
Located At: CCX_L75 CNTRL
END DESCRIPTION:
#Sta/Elev= 30
  4410.2   85.45    4502   85.18  4580.2   78.73  4620.2    72.9  4645.2   70.58
  4775.2   70.26  4932.2   73.55  4945.9   72.82  4967.9   74.37  4980.4   71.08
  4988.7   64.66  4991.6   63.67    5008   63.22  5011.4   64.33  5014.8   70.61
  5028.7   73.78  5119.2   70.24  5614.2   69.66  5709.2   71.31  6041.4   71.36
  6064.2   69.52  6089.2   64.72  6104.2   64.46  6149.2   68.54  6229.2   73.79
  6504.2   75.41  6529.2   76.47  6744.2   76.66  6859.2   78.26  6872.5   79.29
#Mann= 5 , 1 , 0
 4410.20    0.13       0    4502    0.15       0  4980.4   0.047       0
  5014.8    0.15       0  6041.4      10       0
Bank Sta=4980.40,5014.80
Exp/Cntr=0.3,0.1

Type RM Length L Ch R = 1 ,52306.0,709,709,709
BEGIN DESCRIPTION:
Cross Section Bear Creek 72.0
END DESCRIPTION:
#Sta/Elev= 30
  3662.7    84.1  3722.7   80.41  3872.7   74.45  4092.7   71.62  4137.7   70.14
  4322.7   69.61  4848.7   70.08  4972.7   70.15  4982.8   71.02  4991.1    64.6
    4994   63.61  5010.4   63.16  5013.8   64.27  5017.2   70.55  5036.7   75.47
  5056.7   72.09  5071.7   70.35  5486.7   71.15  5516.7   72.07  5646.7    71.4
  5771.7   71.76  5806.7   72.98  5898.6   73.88  5926.7   69.05  5941.7   64.81
  5951.7   64.16  5976.7   70.57  5991.7   73.03  6076.7   75.83  6186.7   86.15
#Mann= 5 , 1 , 0
 3662.70    0.13       0  4848.7    0.15       0  4982.8   0.047       0
  5017.2    0.15       0  5898.6      10       0
Bank Sta=4982.80,5017.20
Exp/Cntr=0.3,0.1