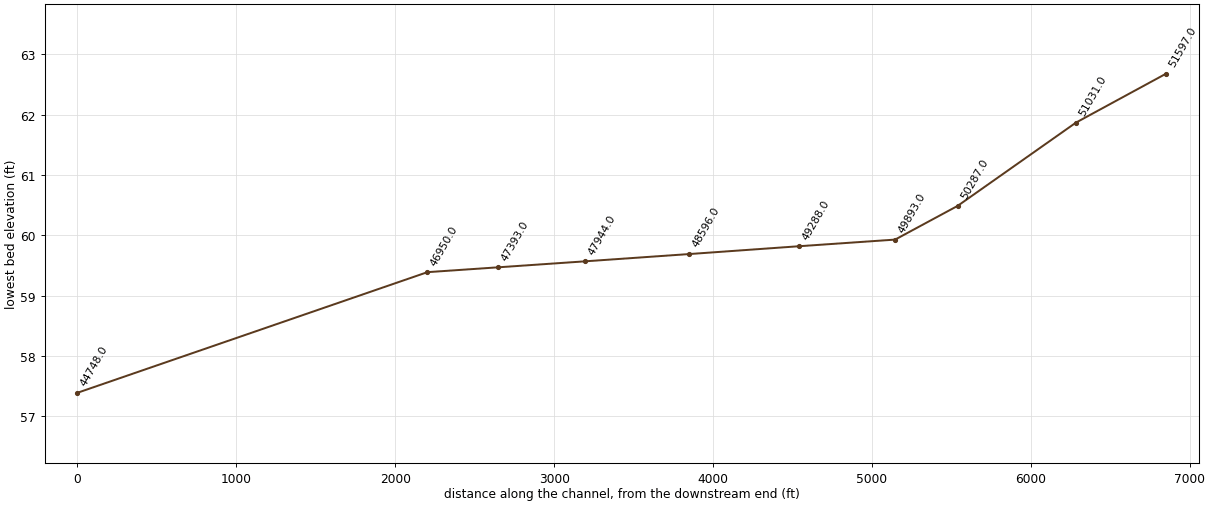
HEC-RAS study 04072003_Bear_Creek.prj: Bear Creek

--- 04072003_Bear_Creek.g01 (geometry) --- (continued)

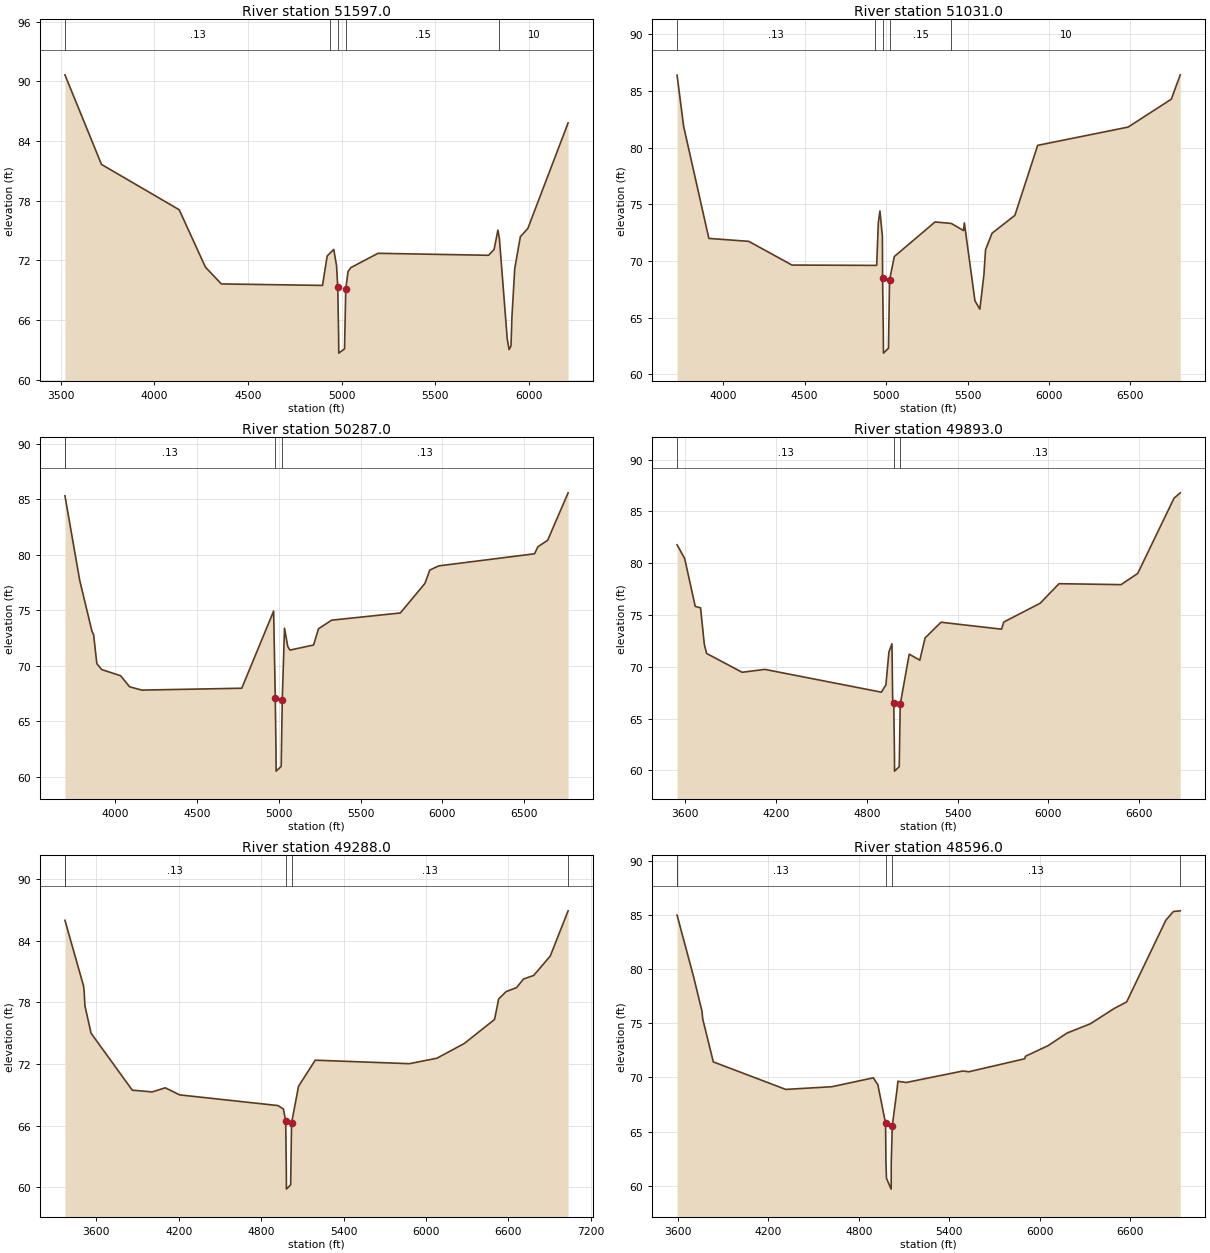
Type RM Length L Ch R = 1 ,51597.0,566,566,566
BEGIN DESCRIPTION:
Cross Section Bear Creek 71.0
END DESCRIPTION:
#Sta/Elev= 30
  3522.1   90.67  3717.1   81.66  4132.1    77.1  4272.1   71.33  4357.1   69.64
  4897.1   69.49  4922.1   72.45  4939.8   72.78  4957.1   73.11  4972.1   71.49
 4978.65   69.29 4983.15   64.52 4983.95   62.68 5014.85   63.11 5021.35   69.12
  5033.5   70.89  5048.5   71.28  5193.5   72.72  5783.5   72.52  5813.5   73.11
  5833.5   75.05  5841.7   74.18  5883.5   64.11  5893.5   63.04  5903.5   63.41
  5908.5   66.32  5923.5   71.19  5953.5   74.39  5993.5   75.22  6208.5   85.84
#Mann= 5 , 1 , 0
 3522.10    0.13       0  4939.8    0.15       0 4978.65   0.047       0
 5021.35    0.15       0  5841.7      10       0
Bank Sta=4978.65,5021.35
Exp/Cntr=0.3,0.1

Type RM Length L Ch R = 1 ,51031.0,744,744,744
BEGIN DESCRIPTION:
Cross Section Bear Creek 70.0
END DESCRIPTION:
#Sta/Elev= 30
  3717.4   86.39  3757.4   81.89  3912.4   71.99  4157.4   71.73  4422.4   69.64
  4932.8   69.61  4942.4   69.62  4952.4   73.36  4962.4   74.41  4977.4   72.16
 4978.65   68.48 4983.15   63.71 4983.95   61.87 5014.85    62.3 5021.35   68.31
  5050.5   70.39  5300.5   73.44  5400.4   73.31  5475.5   72.68  5480.5   73.36
  5545.5   66.49  5575.5   65.75  5600.5   68.78  5610.5   70.99  5650.5   72.45
  5790.5   74.02  5930.5    80.2  6485.5   81.81  6750.5   84.27  6805.5   86.42
#Mann= 5 , 1 , 0
 3717.40    0.13       0  4932.8    0.15       0 4978.65   0.047       0
 5021.35    0.15       0  5400.4      10       0
Bank Sta=4978.65,5021.35
Exp/Cntr=0.3,0.1

Type RM Length L Ch R = 1 ,50287.0,394,394,394
BEGIN DESCRIPTION:
Cross Section CCX_L74
Located At: CCX_L74 CNTRL
END DESCRIPTION:
#Sta/Elev= 30
    3694   85.33    3784   77.72    3859   73.11    3869    72.8    3889   70.18
    3919   69.65    4034    69.1    4089    68.1    4164    67.8  4774.1   67.97
  4968.9   74.93  4978.8    67.1  4983.3   62.33  4984.1   60.49    5015   60.92
  5021.5   66.93  5035.3   73.38  5055.3   71.73    5069   71.41  5212.8   71.87
  5242.8   73.33  5322.8   74.11  5742.8   74.76  5892.8   77.42  5922.8   78.63
  5977.8   79.01  6562.8    80.1  6582.8   80.73  6642.8   81.32  6767.8    85.6
#Mann= 4 , 1 , 0
 3694.00     0.2       0    3694    0.13       0  4978.8   0.047       0
  5021.5    0.13       0
Bank Sta=4978.80,5021.50
Exp/Cntr=0.3,0.1

Type RM Length L Ch R = 1 ,49893.0,605,605,605
BEGIN DESCRIPTION:
Cross Section Bear Creek 69.0
END DESCRIPTION:
#Sta/Elev= 30
  3546.7   81.77  3596.7   80.46  3666.7   75.83  3701.7   75.69  3726.7   72.17
  3741.7   71.29  3976.7   69.47  4126.7   69.75  4896.7   67.55  4926.7   68.25
  4946.7   71.42  4966.7   72.22  4971.7   66.61 4978.65   66.54 4983.15   61.77
 4983.95   59.93 5014.85   60.36 5021.35   66.37  5080.9   71.22  5150.9   70.64
  5185.9   72.79  5290.9    74.3  5690.9   73.63  5705.9   74.32  5945.9   76.13
  6070.9   78.02  6480.9   77.93  6590.9   79.01  6830.9   86.27  6872.1   86.79
#Mann= 3 , 1 , 0
 3546.70    0.13       0 4978.65   0.047       0 5021.35    0.13       0
Bank Sta=4978.65,5021.35
Exp/Cntr=0.3,0.1

Type RM Length L Ch R = 1 ,49288.0,692,692,692
BEGIN DESCRIPTION:
Cross Section Bear Creek 68.0
END DESCRIPTION:
#Sta/Elev= 30
  3372.1   86.01  3507.1   79.63  3512.1   79.05  3517.1    77.7  3562.1   75.01
  3862.1   69.46  4007.1   69.29  4102.1   69.69  4207.1      69  4922.1   67.96
  4962.1   67.62 4978.65   66.43 4983.15   61.66 4983.95   59.82 5014.85   60.25
 5016.55   62.05 5021.35   66.26  5072.1   69.84  5193.7   72.38  5878.7   72.04
  6078.7   72.57  6278.7   74.01  6498.7   76.35  6528.7   78.35  6583.7   79.07
  6658.7   79.45  6708.7   80.28  6783.7   80.64  6903.7   82.52    7034   86.93
#Mann= 5 , 1 , 0
 3372.10     0.2       0  3372.1    0.13       0 4978.65   0.047       0
 5021.35    0.13       0    7034     0.2       0
Bank Sta=4978.65,5021.35
Exp/Cntr=0.3,0.1

Type RM Length L Ch R = 1 ,48596.0,652,652,652
BEGIN DESCRIPTION:
Cross Section Bear Creek 67.0
END DESCRIPTION:
#Sta/Elev= 30
    3597   84.97    3707   79.25    3762    76.1    3767   75.38    3837   71.43
    4317   68.89    4622   69.14    4897   69.96    4927   69.32  4977.9   65.76
  4980.5   62.11  4983.9   60.69    5015   59.69  5015.5   62.15  5022.1    65.5
  5054.6   68.96  5059.6   69.64  5114.6   69.53  5489.6   70.59  5529.6   70.52
  5899.6   71.72  5904.6   71.95  6054.6   72.93  6179.6   74.09  6334.6   74.95
  6494.6   76.38  6574.6   76.96  6834.6   84.51  6884.6   85.31  6929.8   85.37
#Mann= 5 , 1 , 0
 3597.00     0.2       0    3597    0.13       0  4977.9   0.047       0
  5022.1    0.13       0  6929.8     0.2       0
Bank Sta=4977.90,5022.10
Exp/Cntr=0.3,0.1

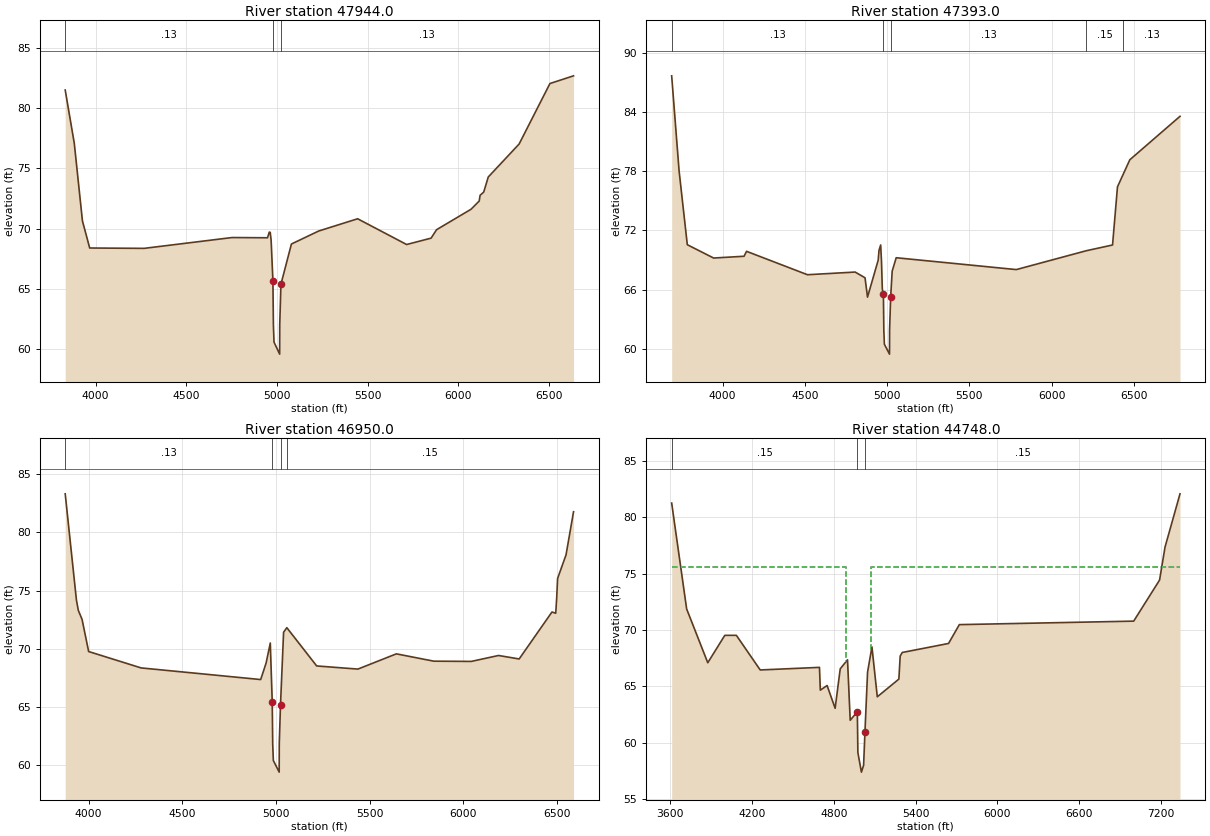
Type RM Length L Ch R = 1 ,47944.0,551,551,551
BEGIN DESCRIPTION:
Cross Section Bear Creek 66.0
END DESCRIPTION:
#Sta/Elev= 30
    3833   81.52    3883    77.1    3928   70.64    3968   68.39    4268   68.36
    4753   69.26    4948   69.24    4958   69.71    4963   69.69    4968   69.05
  4977.9   65.64  4980.5   61.99  4983.9   60.57    5015   59.57  5015.5   62.03
  5022.1   65.38  5079.8   68.72  5229.8    69.8  5444.8   70.82  5714.8   68.68
  5849.8   69.21  5879.8   69.91  6069.8   71.61  6114.8   72.29  6119.8   72.77
  6139.8   73.04  6164.8   74.29  6334.8   77.03  6504.8   82.06  6634.8    82.7
#Mann= 3 , 1 , 0
 3833.00    0.13       0  4977.9   0.047       0  5022.1    0.13       0
Bank Sta=4977.90,5022.10
Exp/Cntr=0.3,0.1

Type RM Length L Ch R = 1 ,47393.0,443,443,443
BEGIN DESCRIPTION:
Cross Section Bear Creek 65.0
END DESCRIPTION:
#Sta/Elev= 30
  3690.9   87.65  3735.9   78.04  3785.9   70.55  3945.9    69.2  4130.9   69.38
  4145.9   69.88  4516.3   67.51  4806.3   67.78  4866.3    67.2  4881.3   65.24
  4946.3   68.99  4951.3   69.99  4961.3   70.52  4966.3   68.86  4971.3   66.06
  4977.9   65.54  4980.5   61.89  4983.9   60.47    5015   59.47  5015.5   61.93
  5022.1   65.28  5031.3   67.88  5055.7   69.23  5785.7   68.03  6211.4   69.94
  6370.7   70.52  6400.7   76.41  6434.7   77.65  6475.7   79.15  6780.7   83.55
#Mann= 5 , 1 , 0
 3690.90    0.13       0  4977.9   0.047       0  5022.1    0.13       0
  6211.4    0.15       0  6434.7    0.13       0
Bank Sta=4977.90,5022.10
Exp/Cntr=0.3,0.1

Type RM Length L Ch R = 1 ,46950.0,2202,2202,2202
BEGIN DESCRIPTION:
Cross Section CCX_L73
Located At: CCX_L73 CNTRL
END DESCRIPTION:
#Sta/Elev= 30
  3875.7   83.32  3935.7   74.17  3945.7    73.3  3965.7   72.52  4000.7   69.76
  4280.7   68.35  4918.3   67.35  4947.1   68.76  4969.6   70.49  4979.9   65.46
  4982.5   61.81  4985.9   60.39    5017   59.39  5017.5   61.85  5024.1    65.2
  5040.5   71.42  5057.8   71.81    5217   68.52    5437   68.25    5642   69.56
    5842   68.93    6042   68.91    6187   69.42    6297   69.12    6472   73.16
    6492   73.05    6497   74.31    6502   76.04    6547   78.07    6587   81.78
#Mann= 4 , 1 , 0
 3875.70    0.13       0  4979.9   0.047       0  5024.1    0.13       0
  5057.8    0.15       0
Bank Sta=4979.90,5024.10
Exp/Cntr=0.5,0.3

Type RM Length L Ch R = 1 ,44748.0,30,30,30
BEGIN DESCRIPTION:
Upstream Section of Bridge/Culvert/Weir
END DESCRIPTION:
#Sta/Elev= 30
  3609.4   81.25  3719.4   71.86  3874.4   67.09  3999.4   69.52  4084.4   69.52
  4259.4   66.45  4694.4   66.68  4700.7   64.66  4750.5   65.07  4809.4   63.05
  4846.8   66.55  4900.3   67.35  4920.1   61.99  4972.4   62.75  4976.4   59.12
  5002.4   57.39  5018.4      58  5028.2   60.92  5047.5   66.26  5079.6    68.5
  5118.9   64.07  5277.3   65.64    5287   67.68    5302      68    5642    68.8
  5721.1   70.47  7001.1   70.78  7191.1   74.42  7231.1   77.34  7341.1   82.07
#Mann= 3 , 1 , 0
 3609.40    0.15       0  4972.4   0.047       0  5028.2    0.15       0
#XS Ineff= 2 , 0
       0    4887    75.6    5076       0    75.6
Bank Sta=4972.40,5028.20
Exp/Cntr=0.5,0.3