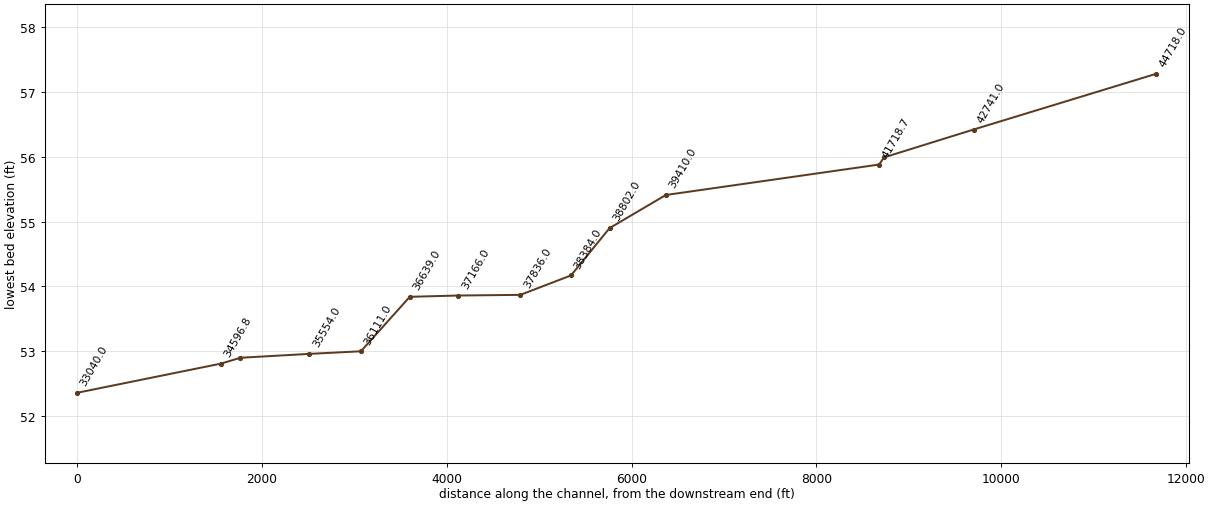
HEC-RAS study 04072003_Bear_Creek.prj: Bear Creek

--- 04072003_Bear_Creek.g01 (geometry) --- (continued)

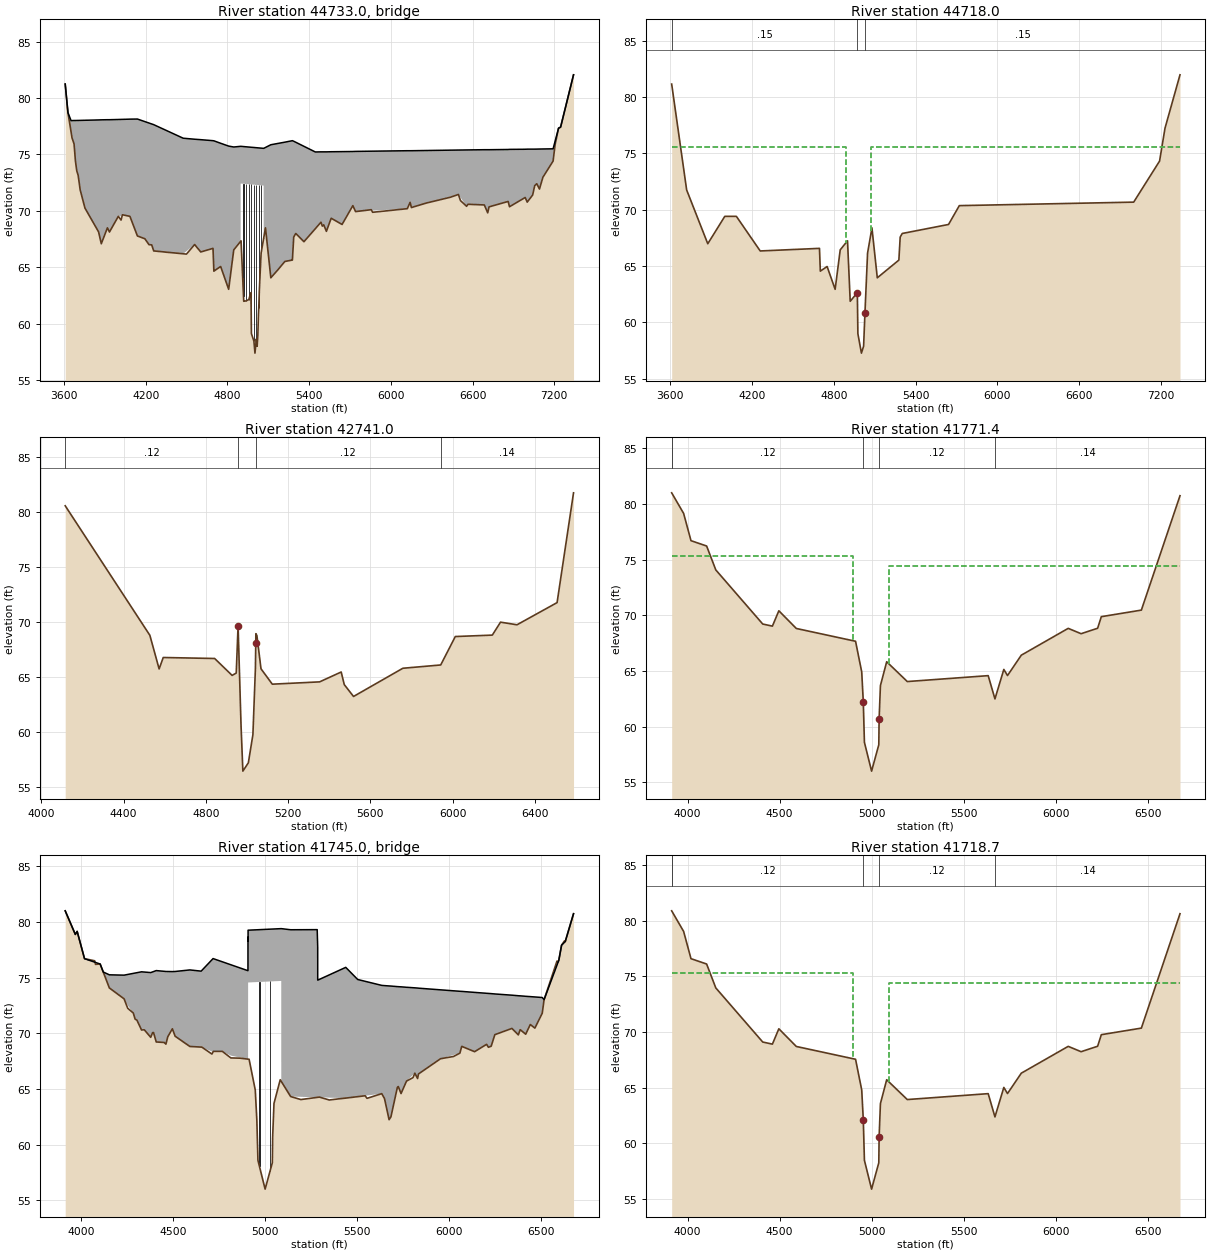
Type RM Length L Ch R = 3 ,44733.0,,,
BEGIN DESCRIPTION:
BEAR CREEK  @ RR
Structure ID: L_beacr5
END DESCRIPTION:
Bridge Culvert--1,0,-1,-1, 0
Deck Dist Width WeirC Skew NumUp NumDn MinLoCord MaxHiCord MaxSubmerge Is_Ogee
10,10,2.6,, 60, 60,,,0.95,0,1,1,,
  3609.4  3629.4  3652.4  3674.4  3684.4  3719.4  3754.4  3854.4  3874.4  3919.4
  3934.4  3999.4  4084.4  4139.4  4259.4  4475.4  4559.4  4604.4  4694.4  4700.7
  4750.5  4809.4  4846.8 4897.31  4897.4 5066.39  5066.5  5079.6  5118.9  5222.3
  5277.3    5287    5302    5362  5445.4    5487    5527    5562    5642  5721.1
  5741.1  6121.1  6141.1  6151.1  6496.1  6556.1  6686.1  6711.1  6721.1  6861.1
  6871.1  6986.1  7001.1  7041.1  7056.1  7091.1  7191.1  7231.1  7246.1  7341.1
   81.24   78.72      78   78.01   78.01   78.02   78.03   78.06   78.07   78.08
   78.08    78.1   78.13   78.14   77.64   76.44   76.35   76.31   76.22   76.21
   75.99   75.74   75.66   75.72   75.72   75.54   75.54   75.62   75.86   76.09
   76.22   76.17   76.08   75.72   75.22   75.23   75.23   75.24   75.25   75.26
   75.27   75.33   75.33   75.33   75.39    75.4   75.42   75.42   75.42   75.44
   75.45   75.46   75.47   75.47   75.47   75.48    75.5   77.33   77.42   82.06
   81.24   78.72      77   75.93   74.42   71.85   70.24   68.13   67.08   68.49
   68.12   69.51   69.51   67.77   66.44   66.19   67.01   66.35   66.67   64.65
   65.06   63.04   66.54    67.3   72.42   72.24   67.58   68.49   64.06   65.51
   65.63   67.67   67.99   67.26   68.41   68.99   68.18   69.34   68.79   70.46
   69.93   70.19   70.75   70.29   71.45    70.4   70.52   69.82   70.35   70.83
   70.36   71.18   70.77    71.4   72.23   71.93   74.41   77.33   77.42   82.06
  3609.4  3629.4  3652.4  3674.4  3684.4  3719.4  3754.4  3854.4  3874.4  3919.4
  3934.4  3999.4  4084.4  4139.4  4259.4  4475.4  4559.4  4604.4  4694.4  4700.7
  4750.5  4809.4  4846.8 4897.31  4897.4 5066.39  5066.5  5079.6  5118.9  5222.3
  5277.3    5287    5302    5362  5445.4    5487    5527    5562    5642  5721.1
  5741.1  6121.1  6141.1  6151.1  6496.1  6556.1  6686.1  6711.1  6721.1  6861.1
  6871.1  6986.1  7001.1  7041.1  7056.1  7091.1  7191.1  7231.1  7246.1  7341.1
   81.24   78.72      78   78.01   78.01   78.02   78.03   78.06   78.07   78.08
   78.08    78.1   78.13   78.14   77.64   76.44   76.35   76.31   76.22   76.21
   75.99   75.74   75.66   75.72   75.72   75.54   75.54   75.62   75.86   76.09
   76.22   76.17   76.08   75.72   75.22   75.23   75.23   75.24   75.25   75.26
   75.27   75.33   75.33   75.33   75.39    75.4   75.42   75.42   75.42   75.44
   75.45   75.46   75.47   75.47   75.47   75.48    75.5   77.33   77.42   82.06
   81.14   78.62    76.9   75.83   74.32   71.75   70.14   68.03   66.98   68.39
   68.02   69.41   69.41   67.67   66.34   66.09   66.91   66.25   66.57   64.55
   64.96   62.94   66.44    67.2   72.32   72.14   67.48   68.39   63.96   65.41
   65.53   67.57   67.89   67.16   68.31   68.89   68.08   69.24   68.69   70.36
   69.83   70.09   70.65   70.19   71.35    70.3   70.42   69.72   70.25   70.73
   70.26   71.08   70.67    71.3   72.13   71.83   74.31   77.23   77.32   81.96
Pier Skew, UpSta & Num, DnSta & Num=,4918.4, 2 ,4918.4, 2 , 0 , 0 , 0 ,,
     1.2     1.2
   61.26    73.4
     1.2     1.2
   61.16    73.3
Pier Skew, UpSta & Num, DnSta & Num=,4936.6, 2 ,4936.6, 2 , 0 , 0 , 0 ,,
     1.2     1.2
   61.01   73.38
     1.2     1.2
   60.91   73.28
Pier Skew, UpSta & Num, DnSta & Num=,4957.3, 2 ,4957.3, 2 , 0 , 0 , 0 ,,
     1.2     1.2
   61.13   73.36
     1.2     1.2
   61.03   73.26
Pier Skew, UpSta & Num, DnSta & Num=,4974.3, 2 ,4974.3, 2 , 0 , 0 , 0 ,,
     1.2     1.2
   59.87   73.34
     1.2     1.2
   59.77   73.24
Pier Skew, UpSta & Num, DnSta & Num=,4994.6, 2 ,4994.6, 2 , 0 , 0 , 0 ,,
     1.2     1.2
   57.37   73.32
     1.2     1.2
   57.27   73.22
Pier Skew, UpSta & Num, DnSta & Num=,5012.8, 2 ,5012.8, 2 , 0 , 0 , 0 ,,
     1.2     1.2
   57.57    73.3
     1.2     1.2
   57.47    73.2
Pier Skew, UpSta & Num, DnSta & Num=,5030.3, 2 ,5030.3, 2 , 0 , 0 , 0 ,,
     1.2     1.2
   60.24   73.28
     1.2     1.2
   60.14   73.18
Pier Skew, UpSta & Num, DnSta & Num=,5047.5, 2 ,5047.5, 2 , 0 , 0 , 0 ,,
     1.2     1.2
    65.1   73.26
     1.2     1.2
      65   73.16
Abutment Skew #Up #Dn=, 2 , 2
 4897.20 4920.10
   72.42   61.98
 4897.20 4920.10
   72.32   61.88
Abutment Skew #Up #Dn=, 2 , 2
 5035.20 5066.59
   63.13   72.24
 5035.20 5066.59
   63.03   72.14
BR Coef= 1 , 1 , 0 ,1.25, 0 ,,,0.8,0,2,0,
Wspro=,,,, 1 ,,,, 0 ,,,, 0 ,,,,-1 ,-1 ,-1 , 0 , 0 , 0 , 0 , 0
BC Design=,, 0 ,, 0 ,,,,,,
BR U #Sta/Elev= 118
  3609.4   81.24  3629.4   78.72  3652.4      77  3659.4   76.47  3674.4   75.93
  3684.4   74.42  3694.4   73.54  3704.4   73.15  3719.4   71.85  3754.4   70.24
  3854.4   68.13  3874.4   67.08  3919.4   68.49  3934.4   68.12  3999.4   69.51
  4019.4   69.18  4029.4   69.65  4084.4   69.51  4139.4   67.77  4194.4   67.52
  4195.4    67.5  4220.4   67.07  4224.4      67  4244.4   66.98  4245.4   66.94
  4259.4   66.44  4270.4   66.43  4330.4   66.36  4350.4   66.33  4380.4    66.3
  4475.4   66.19  4499.4   66.16  4559.4   67.01  4604.4   66.35  4694.4   66.67
  4700.4   64.75  4700.7   64.65  4749.3   65.05  4750.5   65.06    4800   63.36
  4809.4   63.04  4846.8   66.54  4849.8   66.58  4897.2   67.29 4897.31    67.3
  4897.4    67.3  4900.3   67.34  4918.4   62.41    4920   62.01  4920.1   61.98
  4936.6   62.01  4957.3   62.13  4972.4   62.74  4974.3   61.58  4976.4   59.11
  4994.6   58.45  5002.4   57.38  5012.8   58.64  5018.4   57.99  5023.5   58.99
  5028.2   60.91  5030.3   61.37  5035.1    63.1  5035.2   63.13  5047.5   66.25
 5066.39   67.57  5066.5   67.58  5066.6   67.58  5079.6   68.49  5117.3   64.24
  5118.9   64.06  5170.3   64.76  5170.9   64.77  5221.3    65.5  5222.3   65.51
  5276.3   65.63  5277.3   65.63    5287   67.67    5302   67.99    5362   67.26
  5445.4   68.41    5487   68.99    5497   68.64    5507   68.76    5527   68.18
    5562   69.34    5642   68.79  5721.1   70.46  5741.1   69.93  5856.1    70.1
  5866.1   69.87  6121.1   70.19  6141.1   70.75  6151.1   70.29  6261.1   70.69
  6436.1    71.2  6496.1   71.45  6511.1   70.91  6556.1    70.4  6566.1   70.58
  6686.1   70.52  6711.1   69.82  6721.1   70.35  6861.1   70.83  6871.1   70.36
  6986.1   71.18  7001.1   70.77  7041.1    71.4  7056.1   72.23  7071.1    72.4
  7091.1   71.93  7116.1   72.97  7191.1   74.41  7206.1   75.89  7216.4   76.48
  7231.1   77.33  7246.1   77.42  7341.1   82.06
BR U #Mann= 3
 3609.40    0.15  4972.4   0.047  5028.2    0.15
BR U Banks=4972.40,5028.20
BR D #Sta/Elev= 118
  3609.4   81.14  3629.4   78.62  3652.4    76.9  3659.4   76.37  3674.4   75.83
  3684.4   74.32  3694.4   73.44  3704.4   73.05  3719.4   71.75  3754.4   70.14
  3854.4   68.03  3874.4   66.98  3919.4   68.39  3934.4   68.02  3999.4   69.41
  4019.4   69.08  4029.4   69.55  4084.4   69.41  4139.4   67.67  4194.4   67.42
  4195.4    67.4  4220.4   66.97  4224.4    66.9  4244.4   66.88  4245.4   66.84
  4259.4   66.34  4270.4   66.33  4330.4   66.26  4350.4   66.23  4380.4    66.2
  4475.4   66.09  4499.4   66.06  4559.4   66.91  4604.4   66.25  4694.4   66.57
  4700.4   64.65  4700.7   64.55  4749.3   64.95  4750.5   64.96    4800   63.26
  4809.4   62.94  4846.8   66.44  4849.8   66.48  4897.2   67.19 4897.31    67.2
  4897.4    67.2  4900.3   67.24  4918.4   62.31    4920   61.91  4920.1   61.88
  4936.6   61.91  4957.3   62.03  4972.4   62.64  4974.3   61.48  4976.4   59.01
  4994.6   58.35  5002.4   57.28  5012.8   58.54  5018.4   57.89  5023.5   58.89
  5028.2   60.81  5030.3   61.27  5035.1      63  5035.2   63.03  5047.5   66.15
 5066.39   67.47  5066.5   67.48  5066.6   67.48  5079.6   68.39  5117.3   64.14
  5118.9   63.96  5170.3   64.66  5170.9   64.67  5221.3    65.4  5222.3   65.41
  5276.3   65.53  5277.3   65.53    5287   67.57    5302   67.89    5362   67.16
  5445.4   68.31    5487   68.89    5497   68.54    5507   68.66    5527   68.08
    5562   69.24    5642   68.69  5721.1   70.36  5741.1   69.83  5856.1      70
  5866.1   69.77  6121.1   70.09  6141.1   70.65  6151.1   70.19  6261.1   70.59
  6436.1    71.1  6496.1   71.35  6511.1   70.81  6556.1    70.3  6566.1   70.48
  6686.1   70.42  6711.1   69.72  6721.1   70.25  6861.1   70.73  6871.1   70.26
  6986.1   71.08  7001.1   70.67  7041.1    71.3  7056.1   72.13  7071.1    72.3
  7091.1   71.83  7116.1   72.87  7191.1   74.31  7206.1   75.79  7216.4   76.38
  7231.1   77.23  7246.1   77.32  7341.1   81.96
BR D #Mann= 3
 3609.40    0.15  4972.4   0.047  5028.2    0.15
BR D Banks=4972.40,5028.20

Type RM Length L Ch R = 1 ,44718.0,1977,1977,1977
BEGIN DESCRIPTION:
Downstream Section of Bridge/Culvert/Weir
END DESCRIPTION:
#Sta/Elev= 30
  3609.4   81.14  3719.4   71.75  3874.4   66.98  3999.4   69.41  4084.4   69.41
  4259.4   66.34  4694.4   66.57  4700.7   64.55  4750.5   64.96  4809.4   62.94
  4846.8   66.44  4900.3   67.24  4920.1   61.88  4972.4   62.64  4976.4   59.01
  5002.4   57.28  5018.4   57.89  5028.2   60.81  5047.5   66.15  5079.6   68.39
  5118.9   63.96  5277.3   65.53    5287   67.57    5302   67.89    5642   68.69
  5721.1   70.36  7001.1   70.67  7191.1   74.31  7231.1   77.23  7341.1   81.96
#Mann= 3 , 1 , 0
 3609.40    0.15       0  4972.4   0.047       0  5028.2    0.15       0
#XS Ineff= 2 , 0
       0    4887    75.6    5076       0    75.6
Bank Sta=4972.40,5028.20
Exp/Cntr=0.5,0.3

Type RM Length L Ch R = 1 ,42741.0,969.65,969.65,969.65
BEGIN DESCRIPTION:
Cross Section Bear Creek 59.0
END DESCRIPTION:
#Sta/Elev= 30
  4116.2   80.59    4528   68.79    4573   65.73    4593   66.77    4843   66.68
    4928   65.14    4948   65.35    4957   69.66  4971.4   60.58  4980.3   56.42
    5007   57.18  5029.1   59.74  5041.3   65.79    5043    68.1  5043.5   68.94
  5048.5   68.77  5068.5   65.74  5123.5   64.34  5353.5   64.55  5458.5   65.45
  5473.5    64.3  5518.5   63.22  5758.5   65.79  5942.5   66.09  6013.5   68.68
  6193.5   68.81  6233.5   69.99  6313.5   69.75  6508.5   71.77  6588.5   81.77
#Mann= 4 , 1 , 0
 4116.20    0.12       0    4957   0.047       0    5043    0.12       0
  5942.5    0.14       0
Bank Sta=4957.00,5043.00
Exp/Cntr=0.5,0.3

Type RM Length L Ch R = 1 ,41771.4,52.7,52.7,52.7
BEGIN DESCRIPTION:
Upstream Section of Bridge/Culvert/Weir
END DESCRIPTION:
#Sta/Elev= 30
  3913.1      81  3978.1   79.15  4018.1    76.7  4103.1   76.22  4153.1   74.07
  4408.1   69.21  4460.7   69.02  4495.7    70.4  4590.7   68.81  4912.8   67.66
  4946.3    64.9  4954.8   62.23  4960.9   58.58  4999.9   55.99  5039.1   58.36
  5040.8   60.67    5048   63.68    5082   65.82    5194   64.04  5633.8   64.57
  5670.5   62.48  5718.8   65.13  5738.8   64.58  5813.8   66.41  6068.8   68.82
  6138.8   68.34  6228.8   68.83  6248.8   69.87  6466.5   70.46  6676.5   80.74
#Mann= 5 , 1 , 0
 3913.10     0.2       0  3913.1    0.12       0  4954.8   0.047       0
  5040.8    0.12       0  5670.5    0.14       0
#XS Ineff= 2 , 0
       0    4897    75.3    5095       0    74.4
Bank Sta=4954.80,5040.80
Exp/Cntr=0.5,0.3

Type RM Length L Ch R = 3 ,41745.0,,,
BEGIN DESCRIPTION:
WEST WASHINGTON ST
Structure ID: L_BEACR4
END DESCRIPTION:
Bridge Culvert--1,0,-1,-1, 0
Deck Dist Width WeirC Skew NumUp NumDn MinLoCord MaxHiCord MaxSubmerge Is_Ogee
10,32.7,2.6,, 60, 60,,,0.95,0,1,1,,
  3913.1  3968.1  3978.1  4018.1  4103.1  4120.1  4153.1  4233.1  4328.1  4378.1
  4393.1  4408.1  4460.7  4495.7  4510.7  4590.7  4652.1  4716.9 4906.55 4906.66
 4907.09  4907.2 4907.31  4907.4 5087.59  5087.7  5138.6    5283 5285.71 5285.82
  5438.2  5503.2  5633.8  5648.8  5673.8  5683.8  5718.8  5738.8  5768.8  5813.8
  5828.8  5833.8  5953.8  6058.8  6068.8  6138.8  6228.8  6248.8  6341.5  6376.5
  6386.5  6416.5  6441.5  6466.5  6506.5  6516.5  6596.5  6611.5  6631.5  6676.5
      81   78.88   79.15    76.7   76.22    75.5   75.25   75.22   75.52   75.45
   75.54   75.63   75.55   75.54   75.55   75.69   75.58   76.71   75.62   78.62
   78.28   79.26   79.26   79.26    79.4    79.4    79.3   79.31   77.77   74.77
   75.92   74.83    74.3   74.28   74.25   74.24   74.19   74.17   74.13   74.08
   74.06   74.05    73.9   73.77   73.76   73.67   73.56   73.53   73.42   73.37
   73.36   73.32   73.29   73.26   73.21   73.02   76.56   77.91   78.24   80.74
      81   78.88   79.15    76.7   76.22   75.49   74.07   73.09   70.29   69.63
   70.06   69.21   69.02    70.4   69.73   68.81   68.75   68.32   67.67   67.67
   67.67   67.67   67.67   74.56    74.7   65.67   64.31   64.24   64.24   64.24
   64.17    64.3   64.57   64.13   62.23   62.48   65.13   64.58    65.7   66.41
   65.93   66.34   67.71   68.21   68.82   68.34   68.83   69.87   70.43   69.85
   70.32   69.91   70.78   70.46    71.8   73.02   76.56   77.91   78.24   80.74
  3913.1  3968.1  3978.1  4018.1  4103.1  4120.1  4153.1  4233.1  4328.1  4378.1
  4393.1  4408.1  4460.7  4495.7  4510.7  4590.7  4652.1  4716.9 4906.55 4906.66
 4907.09  4907.2 4907.31  4907.4 5087.59  5087.7  5138.6    5283 5285.71 5285.82
  5438.2  5503.2  5633.8  5648.8  5673.8  5683.8  5718.8  5738.8  5768.8  5813.8
  5828.8  5833.8  5953.8  6058.8  6068.8  6138.8  6228.8  6248.8  6341.5  6376.5
  6386.5  6416.5  6441.5  6466.5  6506.5  6516.5  6596.5  6611.5  6631.5  6676.5
      81   78.88   79.15    76.7   76.22    75.5   75.25   75.22   75.52   75.45
   75.54   75.63   75.55   75.54   75.55   75.69   75.58   76.71   75.62   78.62
   78.28   79.26   79.26   79.26    79.4    79.4    79.3   79.31   77.77   74.77
   75.92   74.83    74.3   74.28   74.25   74.24   74.19   74.17   74.13   74.08
   74.06   74.05    73.9   73.77   73.76   73.67   73.56   73.53   73.42   73.37
   73.36   73.32   73.29   73.26   73.21   73.02   76.56   77.91   78.24   80.74
    80.9   78.78   79.05    76.6   76.12   75.39   73.97   72.99   70.19   69.53
   69.96   69.11   68.92    70.3   69.63   68.71   68.65   68.22   67.57   67.57
   67.57   67.57   67.57   74.46    74.6   65.57   64.21   64.14   64.14   64.14
   64.07    64.2   64.47   64.03   62.13   62.38   65.03   64.48    65.6   66.31
   65.83   66.24   67.61   68.11   68.72   68.24   68.73   69.77   70.33   69.75
   70.22   69.81   70.68   70.36    71.7   72.92   76.46   77.81   78.14   80.64
Pier Skew, UpSta & Num, DnSta & Num=,4969.2, 2 ,4969.2, 2 , 0 , 0 , 0 ,,
     1.5     1.5
   56.98   75.61
     1.5     1.5
   56.88   75.51
Pier Skew, UpSta & Num, DnSta & Num=,5026.9, 2 ,5026.9, 2 , 0 , 0 , 0 ,,
     1.5     1.5
   56.58   75.65
     1.5     1.5
   56.48   75.55
Abutment Skew #Up #Dn=, 2 , 2
 4907.20 4946.30
   74.56   64.90
 4907.20 4946.30
   74.46   64.80
Abutment Skew #Up #Dn=, 2 , 2
 5048.10 5087.79
   63.69   74.70
 5048.10 5087.79
   63.59   74.60
BR Coef= 1 , 1 , 0 ,1.25, 0 ,,,0.8,0,2,0,
Wspro=,,,, 1 ,,,, 0 ,,,, 0 ,,,,-1 ,-1 ,-1 , 0 , 0 , 0 , 0 , 0
BC Design=,, 0 ,, 0 ,,,,,,
BR U #Sta/Elev= 131
  3913.1      81  3968.1   78.88  3978.1   79.15  4018.1    76.7  4073.1   76.51
  4078.1   76.19  4103.1   76.22  4120.1   75.49  4153.1   74.07  4195.1   73.56
  4233.1   73.09  4235.1   73.01  4250.1   72.37  4253.1   72.24  4283.1   71.82
  4285.1   71.71  4293.1   71.27  4303.1   71.17  4328.1   70.29    4337    70.3
  4343.1   70.31    4347   70.23    4372   69.75  4378.1   69.63  4388.1   70.05
  4393.1   70.06  4408.1   69.21    4412   69.21  4450.7   69.17  4460.7   69.02
  4470.7   69.68    4482   70.01  4495.7    70.4  4507.1   69.89  4510.7   69.73
  4522.1    69.6  4562.1   69.14  4587.1   68.85  4590.7   68.81  4652.1   68.75
  4655.7   68.75  4662.1   68.68  4710.7   68.13  4716.9   68.32  4718.5   68.37
  4765.9   68.37  4767.2   68.37  4813.7   67.78  4815.4   67.78  4859.9   67.76
  4861.3   67.76 4906.55   67.67 4906.66   67.67 4906.77   67.67 4906.87   67.67
 4906.98   67.67 4907.09   67.67  4907.2   67.67 4907.31   67.67  4907.4   67.67
  4912.8   67.66  4946.2   64.91  4946.3    64.9  4954.8   62.23  4960.9   58.58
  4999.9   55.99  5039.1   58.36  5040.8   60.67    5048   63.68  5048.1   63.69
    5082   65.82 5087.59   65.67  5087.7   65.67  5087.8   65.67  5136.5   64.37
  5138.6   64.31  5184.8   64.08    5194   64.04  5234.1   64.13  5246.7   64.16
    5283   64.24  5285.6   64.24 5285.71   64.24 5285.82   64.24    5295   64.26
  5348.8      64  5398.2    64.1  5438.2   64.17  5503.2    64.3  5543.2   64.38
  5543.8   64.38  5553.8   64.15  5610.4   64.45  5633.8   64.57  5648.8   64.13
  5670.5   62.48  5673.8   62.23  5683.8   62.48  5718.8   65.13  5723.8   65.21
  5738.8   64.58  5768.8    65.7  5803.8   66.01  5813.8   66.41  5828.8   65.93
  5833.8   66.34  5953.8   67.71  6023.8   67.91  6058.8   68.21  6068.8   68.82
  6138.8   68.34  6203.8      69  6213.8   68.74  6228.8   68.83  6248.8   69.87
  6341.5   70.43  6376.5   69.85  6386.5   70.32  6416.5   69.91  6441.5   70.78
  6466.5   70.46  6506.5    71.8  6515.1   72.85  6516.5   73.02  6586.5   76.48
  6591.5   76.38  6596.5   76.56  6611.5   77.91  6626.5   78.28  6631.5   78.24
  6676.5   80.74
BR U #Mann= 5
 3913.10     0.2  3913.1    0.12  4954.8   0.047  5040.8    0.12  5670.5    0.14
BR U Banks=4954.80,5040.80
BR D #Sta/Elev= 131
  3913.1    80.9  3968.1   78.78  3978.1   79.05  4018.1    76.6  4073.1   76.41
  4078.1   76.09  4103.1   76.12  4120.1   75.39  4153.1   73.97  4195.1   73.46
  4233.1   72.99  4235.1   72.91  4250.1   72.27  4253.1   72.14  4283.1   71.72
  4285.1   71.61  4293.1   71.17  4303.1   71.07  4328.1   70.19    4337    70.2
  4343.1   70.21    4347   70.13    4372   69.65  4378.1   69.53  4388.1   69.95
  4393.1   69.96  4408.1   69.11    4412   69.11  4450.7   69.07  4460.7   68.92
  4470.7   69.58    4482   69.91  4495.7    70.3  4507.1   69.79  4510.7   69.63
  4522.1    69.5  4562.1   69.04  4587.1   68.75  4590.7   68.71  4652.1   68.65
  4655.7   68.65  4662.1   68.58  4710.7   68.03  4716.9   68.22  4718.5   68.27
  4765.9   68.27  4767.2   68.27  4813.7   67.68  4815.4   67.68  4859.9   67.66
  4861.3   67.66 4906.55   67.57 4906.66   67.57 4906.77   67.57 4906.87   67.57
 4906.98   67.57 4907.09   67.57  4907.2   67.57 4907.31   67.57  4907.4   67.57
  4912.8   67.56  4946.2   64.81  4946.3    64.8  4954.8   62.13  4960.9   58.48
  4999.9   55.89  5039.1   58.26  5040.8   60.57    5048   63.58  5048.1   63.59
    5082   65.72 5087.59   65.57  5087.7   65.57  5087.8   65.57  5136.5   64.27
  5138.6   64.21  5184.8   63.98    5194   63.94  5234.1   64.03  5246.7   64.06
    5283   64.14  5285.6   64.14 5285.71   64.14 5285.82   64.14    5295   64.16
  5348.8    63.9  5398.2      64  5438.2   64.07  5503.2    64.2  5543.2   64.28
  5543.8   64.28  5553.8   64.05  5610.4   64.35  5633.8   64.47  5648.8   64.03
  5670.5   62.38  5673.8   62.13  5683.8   62.38  5718.8   65.03  5723.8   65.11
  5738.8   64.48  5768.8    65.6  5803.8   65.91  5813.8   66.31  5828.8   65.83
  5833.8   66.24  5953.8   67.61  6023.8   67.81  6058.8   68.11  6068.8   68.72
  6138.8   68.24  6203.8    68.9  6213.8   68.64  6228.8   68.73  6248.8   69.77
  6341.5   70.33  6376.5   69.75  6386.5   70.22  6416.5   69.81  6441.5   70.68
  6466.5   70.36  6506.5    71.7  6515.1   72.75  6516.5   72.92  6586.5   76.38
  6591.5   76.28  6596.5   76.46  6611.5   77.81  6626.5   78.18  6631.5   78.14
  6676.5   80.64
BR D #Mann= 5
 3913.10     0.2  3913.1    0.12  4954.8   0.047  5040.8    0.12  5670.5    0.14
BR D Banks=4954.80,5040.80

Type RM Length L Ch R = 1 ,41718.7,2308.65,2308.65,2308.65
BEGIN DESCRIPTION:
Downstream Section of Bridge/Culvert/Weir
END DESCRIPTION:
#Sta/Elev= 30
  3913.1   80.89  3978.1   79.04  4018.1   76.59  4103.1   76.11  4153.1   73.96
  4408.1    69.1  4460.7   68.91  4495.7   70.29  4590.7    68.7  4912.8   67.55
  4946.3   64.79  4954.8   62.12  4960.9   58.47  4999.9   55.88  5039.1   58.25
  5040.8   60.56    5048   63.57    5082   65.71    5194   63.93  5633.8   64.46
  5670.5   62.37  5718.8   65.02  5738.8   64.47  5813.8    66.3  6068.8   68.71
  6138.8   68.23  6228.8   68.72  6248.8   69.76  6466.5   70.35  6676.5   80.63
#Mann= 5 , 1 , 0
 3913.10     0.2       0  3913.1    0.12       0  4954.8   0.047       0
  5040.8    0.12       0  5670.5    0.14       0
#XS Ineff= 2 , 0
       0    4897    75.3    5095       0    74.4
Bank Sta=4954.80,5040.80
Exp/Cntr=0.5,0.3

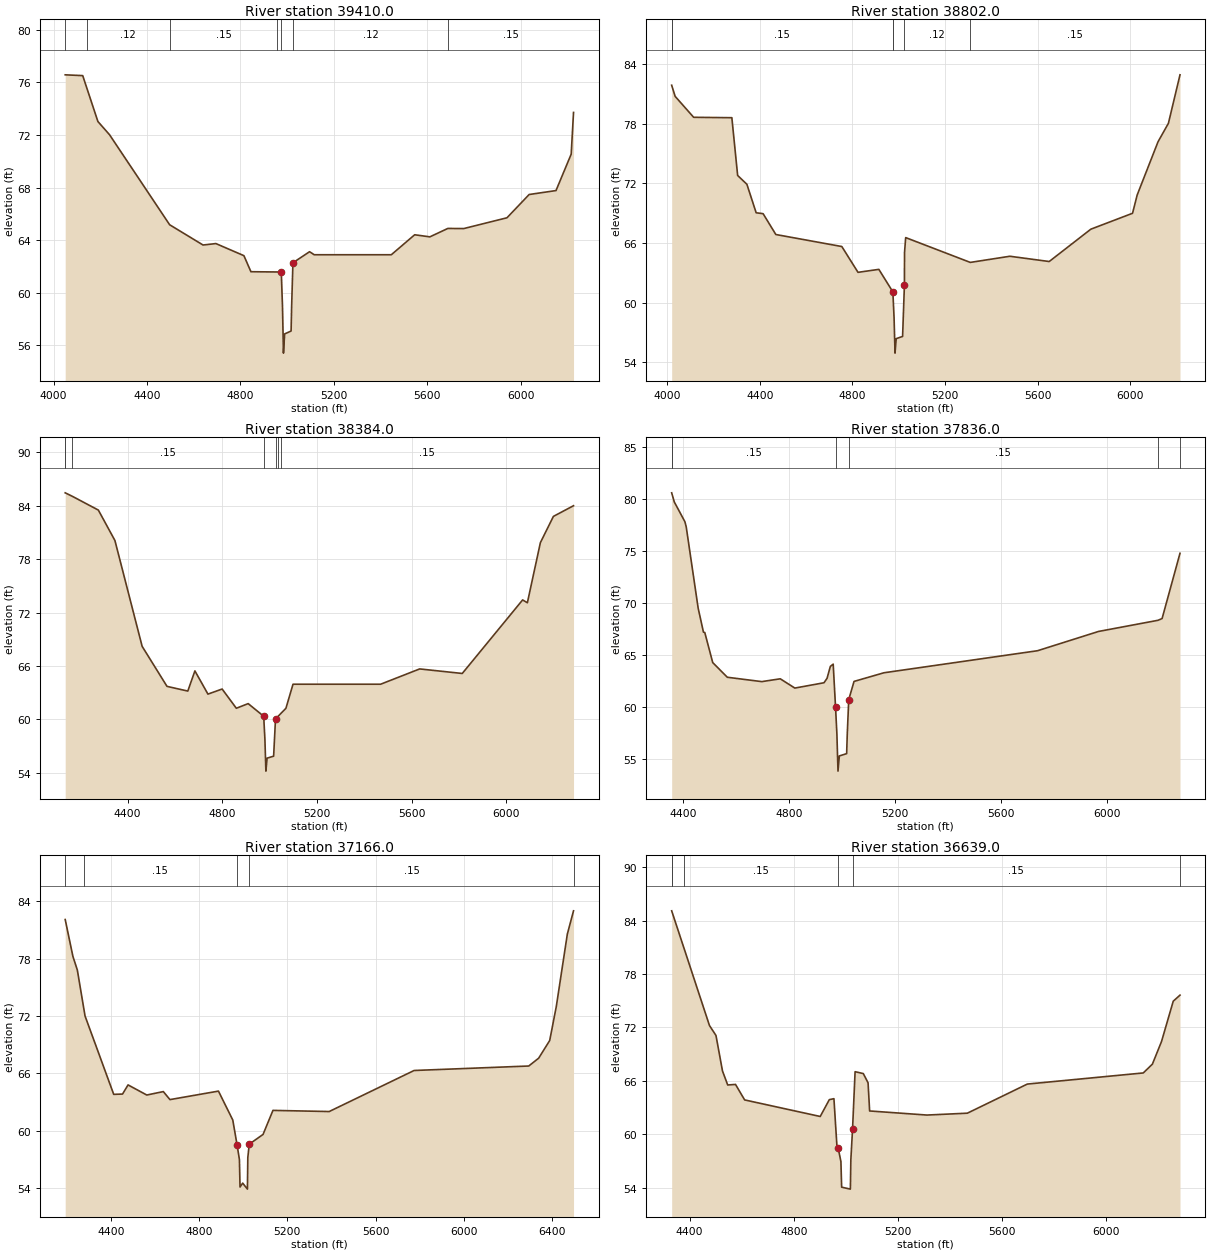
Type RM Length L Ch R = 1 ,39410.0,608,608,608
BEGIN DESCRIPTION:
Cross Section Bear Creek 53.0
END DESCRIPTION:
#Sta/Elev= 30
  4050.1   76.57  4125.1   76.51  4143.1   75.54  4190.1   73.02  4240.1   72.01
  4497.2   65.17  4640.1   63.63  4695.1   63.74  4815.1   62.82  4845.1    61.6
  4957.5   61.58 4975.05   61.58 4980.25   58.96 4984.35   55.41 4989.45   56.87
 5017.05   57.09 5019.35   58.95 5024.95   62.28  5096.1   63.12  5116.1   62.89
  5446.1   62.89  5546.1   64.41  5611.1   64.25  5688.1   64.89  5756.1   64.88
  5941.1    65.7  6036.1   67.47  6151.1   67.77  6216.1   70.54  6226.1   73.71
#Mann= 7 , 1 , 0
 4050.10     0.1       0  4143.1    0.12       0  4497.2    0.15       0
  4957.5    0.12       0 4975.05    0.05       0 5024.95    0.12       0
  5688.1    0.15       0
Bank Sta=4975.05,5024.95
Exp/Cntr=0.3,0.1

Type RM Length L Ch R = 1 ,38802.0,418,418,418
BEGIN DESCRIPTION:
Cross Section Bear Creek 52.0
END DESCRIPTION:
#Sta/Elev= 30
  4019.5   81.89  4034.5   80.77  4114.5   78.66  4279.5   78.62  4304.5    72.8
  4344.5   71.91  4384.5   69.04  4414.5   68.95  4469.5   66.85  4754.5   65.64
  4824.5   63.04  4914.5   63.34    4975   61.07 4975.05   61.07 4980.25   58.45
 4984.35    54.9 4989.45   56.36 5017.05   56.58 5024.95   61.77  5025.4   65.02
  5030.4   66.54  5309.5   64.04  5480.4   64.66  5650.4   64.13  5830.4   67.39
  6010.4   68.99  6030.4   70.83  6120.4   76.19  6165.4   78.06  6215.4   82.94
#Mann= 6 , 1 , 0
 4019.50     0.2       0  4019.5    0.15       0    4975    0.12       0
 4975.05    0.05       0 5024.95    0.12       0  5309.5    0.15       0
Bank Sta=4975.05,5024.95
Exp/Cntr=0.3,0.1

Type RM Length L Ch R = 1 ,38384.0,548,548,548
BEGIN DESCRIPTION:
Cross Section Bear Creek 51.0
END DESCRIPTION:
#Sta/Elev= 30
  4136.6   85.46  4166.6   85.07  4276.6   83.52  4346.6    80.1  4461.6    68.2
  4566.6    63.7  4654.5   63.17  4684.5   65.44  4739.5   62.83  4799.5    63.4
  4859.5   61.24  4909.5   61.76 4975.05   60.34 4980.25   57.72 4984.35   54.17
 4989.45   55.63 5017.05   55.85 5024.95   60.04  5037.6   60.38  5046.7   60.63
  5068.9   61.23  5098.9   63.94  5468.9   63.94  5633.9   65.66  5813.9   65.15
  6068.9   73.42  6088.9    73.1  6143.9   79.86  6198.9   82.81  6283.9   84.01
#Mann= 7 , 1 , 0
 4136.60     0.2       0  4136.6    0.14       0  4166.6    0.15       0
 4975.05    0.05       0 5024.95    0.15       0  5037.6    0.12       0
  5046.7    0.15       0
Bank Sta=4975.05,5024.95
Exp/Cntr=0.3,0.1

Type RM Length L Ch R = 1 ,37836.0,670,670,670
BEGIN DESCRIPTION:
Cross Section CCX_L72
Located At: CCX_L72 CTRL
END DESCRIPTION:
#Sta/Elev= 30
  4356.6   80.61  4366.6   79.73  4406.6   77.83  4411.6   77.33  4456.6   69.53
  4476.6   67.22  4481.6   67.19  4511.6    64.3  4566.6   62.89  4696.6   62.47
  4766.6   62.74  4821.6   61.85  4931.6   62.36  4943.3   62.79  4955.6   63.93
  4966.4   64.15  4975.2   60.04  4980.4   57.42  4984.5   53.87  4989.6   55.33
  5017.2   55.55  5019.5   57.41  5025.1   60.74  5045.1   62.49  5158.1   63.32
  5738.1   65.44  5968.1   67.29  6192.3   68.36  6208.1   68.53  6275.7    74.8
#Mann= 6 , 1 , 0
 4356.60     0.2       0  4356.6    0.15       0  4975.2    0.05       0
  5025.1    0.15       0  6192.3     0.1       0  6275.7     0.2       0
Bank Sta=4975.20,5025.10
Exp/Cntr=0.3,0.1

Type RM Length L Ch R = 1 ,37166.0,527,527,527
BEGIN DESCRIPTION:
Cross Section Bear Creek 50.0
END DESCRIPTION:
#Sta/Elev= 30
  4192.8   82.11  4227.8   78.24  4247.8   76.82  4276.1   72.92  4282.8      72
  4412.8   63.79  4452.8   63.82  4477.8   64.78  4562.8   63.72  4637.8   64.08
  4667.8   63.24  4887.8   64.13  4952.8    61.1 4972.55   58.45 4982.85   56.96
 4985.65   54.08 4997.75   54.49 5019.15   53.86 5020.95   57.16 5027.45   58.57
    5090   59.59    5135   62.11    5390   61.99    5775   66.29    6295   66.76
    6340   67.58    6390   69.43    6420      73    6470   80.58  6498.1   83.02
#Mann= 5 , 1 , 0
 4192.80    0.14       0  4276.1    0.15       0 4972.55    0.05       0
 5027.45    0.15       0  6498.1     0.2       0
Bank Sta=4972.55,5027.45
Exp/Cntr=0.3,0.1

Type RM Length L Ch R = 1 ,36639.0,528,528,528
BEGIN DESCRIPTION:
Cross Section CCX_L71
Located At: CCX_L71 CNTRL
END DESCRIPTION:
#Sta/Elev= 30
  4331.6    85.1  4380.5   80.76  4476.6   72.22  4501.6    71.1  4526.6   67.11
  4546.6   65.54  4576.6    65.6  4611.6   63.86  4901.6      62  4936.5   63.89
  4954.2      64  4965.5   58.78  4970.7   58.43    4981   56.94  4983.8   54.06
  5017.3   53.84  5019.1   57.14  5025.6   60.55  5035.4   67.03  5066.9   66.82
  5085.2   65.78  5091.2   62.62  5311.2   62.16  5466.2   62.37  5696.2   65.64
  6141.2   66.89  6176.2   67.88  6211.2   70.42  6256.2   74.95  6282.1   75.63
#Mann= 6 , 1 , 0
 4331.60     0.2       0  4331.6    0.14       0  4380.5    0.15       0
  4970.7    0.05       0  5025.6    0.15       0  6282.1     0.2       0
Bank Sta=4970.70,5025.60
Exp/Cntr=0.3,0.1

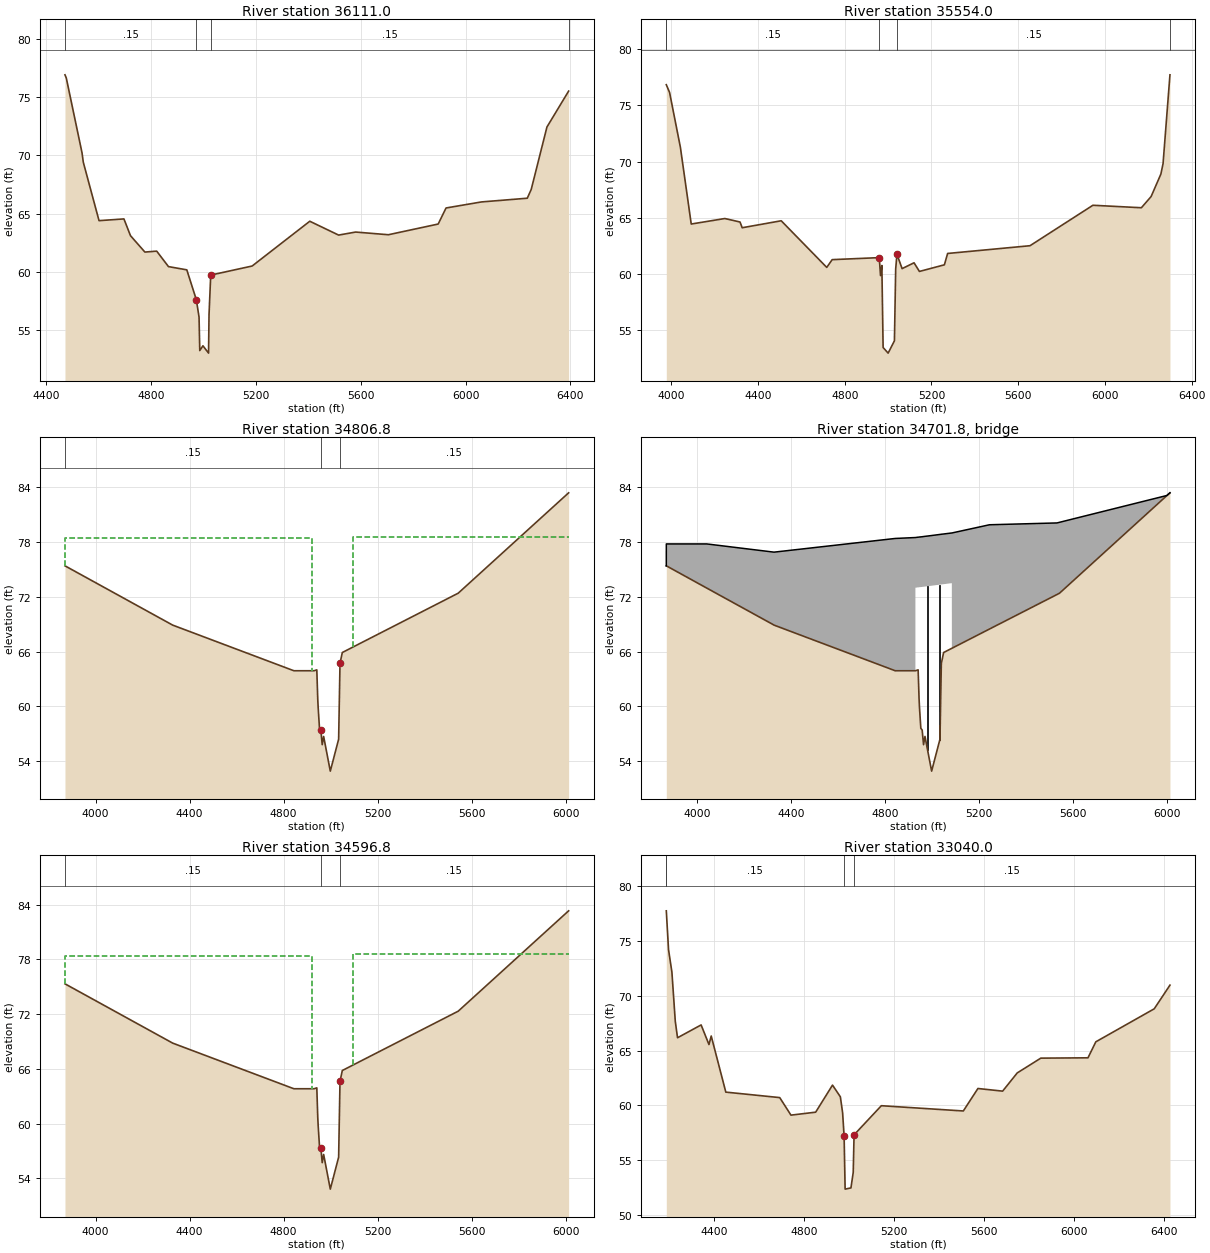
Type RM Length L Ch R = 1 ,36111.0,557,557,557
BEGIN DESCRIPTION:
Cross Section Bear Creek 49.0
END DESCRIPTION:
#Sta/Elev= 30
  4471.2   76.93  4476.2   76.66  4536.2   70.23  4541.2   69.41  4601.2   64.39
  4696.2   64.54  4721.2    63.1  4776.2   61.69  4821.2   61.77  4866.2   60.44
  4936.2   60.16 4972.55   57.59 4982.85    56.1 4985.65   53.22 4997.75   53.63
 5019.15      53 5020.95    56.3 5027.45   59.71  5185.5   60.49  5405.5   64.34
  5515.5   63.15  5580.5   63.41  5705.5   63.18  5895.5    64.1  5925.5   65.48
  6060.5      66  6235.5   66.32  6250.5   67.07  6310.5   72.44  6393.3   75.53
#Mann= 4 , 1 , 0
 4471.20    0.15       0 4972.55    0.05       0 5027.45    0.15       0
  6393.3     0.2       0
Bank Sta=4972.55,5027.45
Exp/Cntr=0.3,0.1

Type RM Length L Ch R = 1 ,35554.0,747.2,747.2,747.2
BEGIN DESCRIPTION:
Cross Section Bear Creek 48.0
END DESCRIPTION:
#Sta/Elev= 30
    3977   76.85    3992   76.17    4042   71.28    4092   64.45    4247   64.94
    4317   64.63    4327   64.12    4507   64.74    4717   60.59    4742   61.28
 4959.25   61.46 4965.05   59.86 4971.15   60.76 4976.95   53.46 5000.15   52.96
 5029.15   54.06 5034.95   60.46 5040.75   61.76  5064.5   60.48  5119.5      61
  5144.5   60.23  5259.5   60.82  5274.5   61.83  5654.5   62.52  5944.5   66.12
  6168.1    65.9  6213.1    66.9  6258.1    68.9  6268.1   69.83  6299.9   77.73
#Mann= 5 , 1 , 0
 3977.00     0.2       0    3977    0.15       0 4959.25    0.05       0
 5040.75    0.15       0  6299.9     0.2       0
Bank Sta=4959.25,5040.75
Exp/Cntr=0.5,0.3

Type RM Length L Ch R = 1 ,34806.8,210,210,210
BEGIN DESCRIPTION:
Upstream Section of Bridge/Culvert/Weir
END DESCRIPTION:
#Sta/Elev= 17
  3869.9    75.4  4328.4    68.9    4844    63.9  4930.1    63.9  4941.5      64
  4945.5    60.8  4947.2    59.9  4952.9    57.6  4958.7    57.4  4964.5    55.8
  4970.6    56.7  4998.9    52.9  5034.4    56.4  5040.2    64.7    5050    65.9
 5543.16    72.4 6013.02    83.4
#Mann= 3 , 1 , 0
 3869.90    0.15       0  4958.7    0.05       0  5040.2    0.15       0
#XS Ineff= 2 , 0
       0    4920    78.4    5095       0    78.6
Bank Sta=4958.70,5040.20
Exp/Cntr=0.5,0.3

Type RM Length L Ch R = 3 ,34701.8,,,
BEGIN DESCRIPTION:
US 70 (New DOT Crossing)
END DESCRIPTION:
Bridge Culvert--1,0,-1,-1, 0
Deck Dist Width WeirC Skew NumUp NumDn MinLoCord MaxHiCord MaxSubmerge Is_Ogee
10,190,2.6,,34,34,,,0.95,0,1,1,,
  3869.9    3870    4042    4328  4328.4    4844  4844.1  4929.7  4929.8 4929.91
    4930  4930.1  4941.5    4942  4945.5  4947.2  4952.9  4958.7  4964.5  4970.6
  4998.9  5034.4  5040.2    5050    5075  5084.7  5084.8 5084.89    5085    5245
    5532 5543.16    6000 6013.02
    75.4    77.8    77.8    76.9    76.9    78.4    78.4    78.5    78.5    78.5
    78.5    78.5   78.54   78.54   78.55   78.56   78.57   78.59   78.61   78.63
   78.72   78.84   78.86   78.89   78.97      79      79      79      79    79.9
    80.1   80.17   83.11    83.4
    75.4    75.4   72.96   68.91    68.9    63.9    63.9    63.9    63.9    63.9
      73      73   73.04   73.04   73.05   73.06   73.07   73.09   73.11   73.13
   73.22   73.34   73.36   73.39   73.47    73.5    73.5    73.5   66.36   68.47
   72.25    72.4    83.1    83.4
  3869.9    3870    4042    4328  4328.4    4844  4844.1  4929.7  4929.8 4929.91
    4930  4930.1  4941.5    4942  4945.5  4947.2  4952.9  4958.7  4964.5  4970.6
  4998.9  5034.4  5040.2    5050    5075  5084.7  5084.8 5084.89    5085    5245
    5532 5543.16    6000 6013.02
    75.4    77.8    77.8    76.9    76.9    78.4    78.4    78.5    78.5    78.5
    78.5    78.5   78.54   78.54   78.55   78.56   78.57   78.59   78.61   78.63
   78.72   78.84   78.86   78.89   78.97      79      79      79      79    79.9
    80.1   80.17   83.11    83.4
    75.3    75.3   72.86   68.81    68.8    63.8    63.8    63.8    63.8    63.8
    72.9    72.9   72.94   72.94   72.95   72.96   72.97   72.99   73.01   73.03
   73.12   73.24   73.26   73.29   73.37    73.4    73.4    73.4   66.26   68.37
   72.15    72.3      83    83.3
Pier Skew, UpSta & Num, DnSta & Num=,4982.0, 2 ,4982.0, 2 , 0 , 0 , 0 ,,
       2       2
   54.03   74.17
       2       2
   53.93   74.07
Pier Skew, UpSta & Num, DnSta & Num=,5033.0, 2 ,5033.0, 2 , 0 , 0 , 0 ,,
       2       2
   55.16   74.34
       2       2
   55.06   74.24
Abutment Skew #Up #Dn=, 2 , 2
 4929.80 4942.00
   73.00   63.60
 4929.80 4942.00
   72.90   63.50
Abutment Skew #Up #Dn=, 2 , 2
 5075.00 5085.09
   66.23   73.50
 5075.00 5085.09
   66.13   73.40
BR Coef= 1 , 1 , 0 ,1.25, 0 ,,,0.8,0,2,0,
Wspro=,,,, 1 ,,,, 0 ,,,, 0 ,,,,-1 ,-1 ,-1 , 0 , 0 , 0 , 0 , 0
BC Design=,, 0 ,, 0 ,,,,,,
BR U #Sta/Elev= 34
  3869.9    75.4    3870    75.4    4042   72.96    4328   68.91  4328.4    68.9
    4844    63.9  4844.1    63.9  4929.7    63.9  4929.8    63.9 4929.91    63.9
    4930    63.9  4930.1    63.9  4941.5      64    4942    63.6  4945.5    60.8
  4947.2    59.9  4952.9    57.6  4958.7    57.4  4964.5    55.8  4970.6    56.7
  4998.9    52.9  5034.4    56.4  5040.2    64.7    5050    65.9    5075   66.23
  5084.7   66.36  5084.8   66.36 5084.89   66.36    5085   66.36    5245   68.47
    5532   72.25 5543.16    72.4    6000    83.1 6013.02    83.4
BR U #Mann= 3
 3869.90    0.15  4958.7    0.05  5040.2    0.15
BR U Banks=4958.70,5040.20
BR D #Sta/Elev= 34
  3869.9    75.3    3870    75.3    4042   72.86    4328   68.81  4328.4    68.8
    4844    63.8  4844.1    63.8  4929.7    63.8  4929.8    63.8 4929.91    63.8
    4930    63.8  4930.1    63.8  4941.5    63.9    4942    63.5  4945.5    60.7
  4947.2    59.8  4952.9    57.5  4958.7    57.3  4964.5    55.7  4970.6    56.6
  4998.9    52.8  5034.4    56.3  5040.2    64.6    5050    65.8    5075   66.13
  5084.7   66.26  5084.8   66.26 5084.89   66.26    5085   66.26    5245   68.37
    5532   72.15 5543.16    72.3    6000      83 6013.02    83.3
BR D #Mann= 3
 3869.90    0.15  4958.7    0.05  5040.2    0.15
BR D Banks=4958.70,5040.20

Type RM Length L Ch R = 1 ,34596.8,1556.8,1556.8,1556.8
BEGIN DESCRIPTION:
Downstream Section of Bridge/Culvert/Weir
END DESCRIPTION:
#Sta/Elev= 17
  3869.9   75.31  4328.4   68.81    4844   63.81  4930.1   63.81  4941.5   63.91
  4945.5   60.71  4947.2   59.81  4952.9   57.51  4958.7   57.31  4964.5   55.71
  4970.6   56.61  4998.9   52.81  5034.4   56.31  5040.2   64.61    5050   65.81
 5543.16   72.31 6013.02   83.31
#Mann= 3 , 1 , 0
 3869.90    0.15       0  4958.7    0.05       0  5040.2    0.15       0
#XS Ineff= 2 , 0
       0    4920    78.4    5095       0    78.6
Bank Sta=4958.70,5040.20
Exp/Cntr=0.5,0.3

Type RM Length L Ch R = 1 ,33040.0,516,516,516
BEGIN DESCRIPTION:
Cross Section Bear Creek 43.0
END DESCRIPTION:
#Sta/Elev= 30
  4186.2   77.75  4196.2    74.2  4211.2   72.15  4226.2   67.67  4236.2   66.17
  4341.2   67.34  4376.2   65.55  4386.2   66.33  4451.2   61.21  4691.2   60.71
  4741.2   59.11  4851.2   59.38  4926.2   61.85  4961.2   60.78  4971.2   59.32
 4977.85   57.19 4982.35   52.36 5008.25   52.47 5018.45   53.89 5022.15   57.31
  5143.6   59.97  5508.6   59.49  5573.6   61.54  5683.6    61.3  5748.6   62.96
  5853.6   64.31  6063.6   64.34  6098.6    65.8  6358.6   68.81  6428.6   70.97
#Mann= 4 , 1 , 0
 4186.20     0.2       0  4186.2    0.15       0 4977.85   0.045       0
 5022.15    0.15       0
Bank Sta=4977.85,5022.15
Exp/Cntr=0.3,0.1