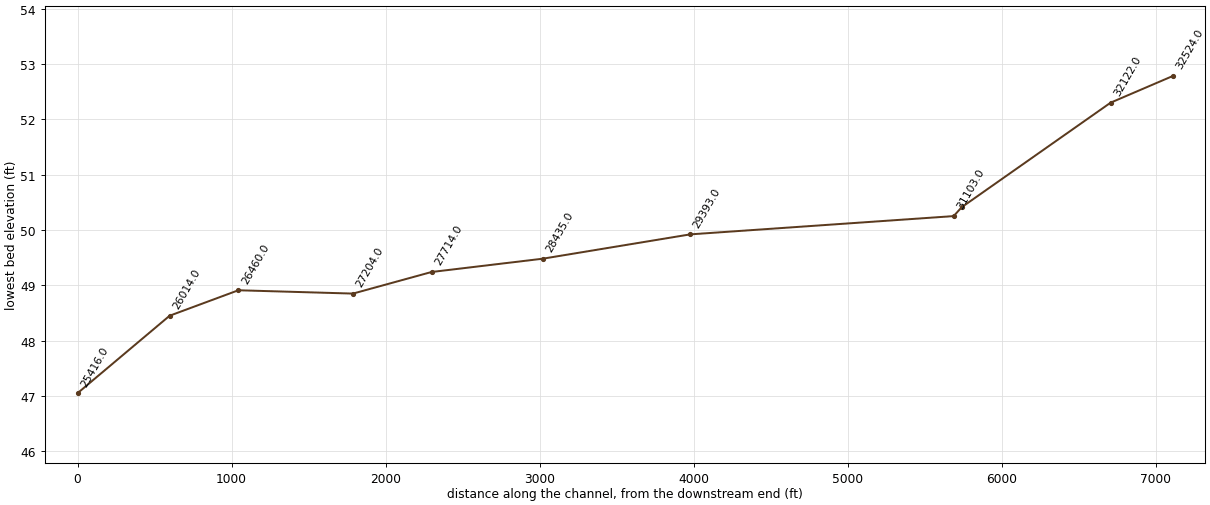
HEC-RAS study 04072003_Bear_Creek.prj: Bear Creek

--- 04072003_Bear_Creek.g01 (geometry) --- (continued)

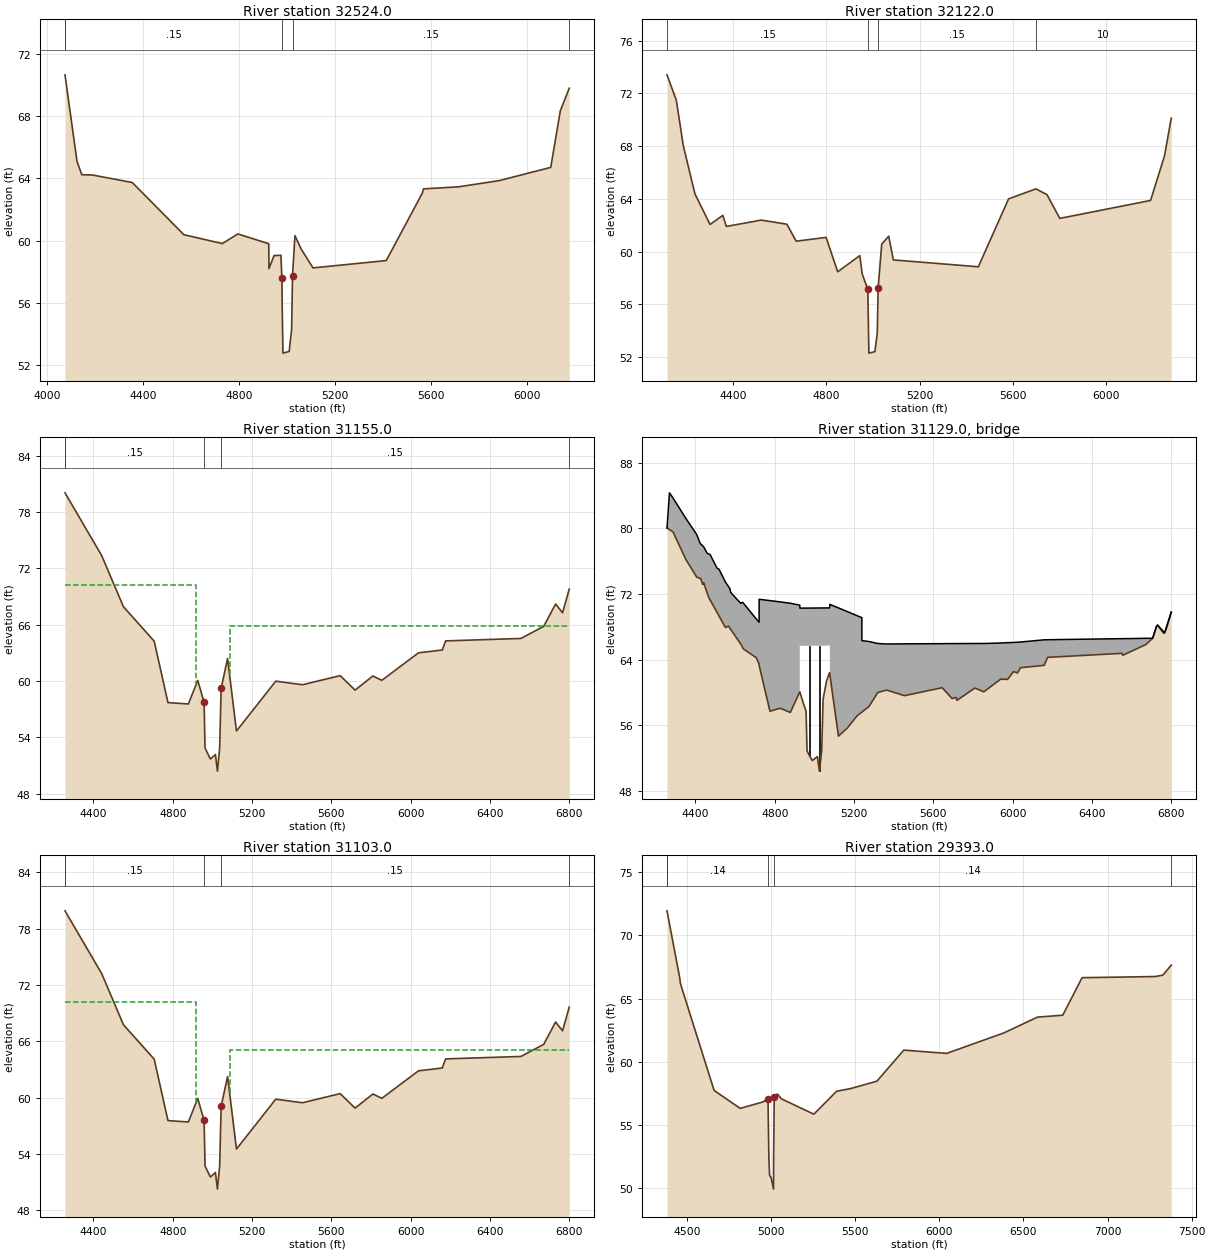
Type RM Length L Ch R = 1 ,32524.0,402,402,402
BEGIN DESCRIPTION:
Cross Section CCX_L70
Located At: CCX_L70 CTRL
END DESCRIPTION:
#Sta/Elev= 30
  4075.2   70.64  4125.2   65.08  4145.2   64.23  4190.2   64.21  4355.2   63.73
  4570.2   60.38  4730.2   59.81  4795.2   60.43  4923.7    59.8  4924.5    58.2
  4945.8   59.04  4974.3   59.06  4978.3   57.61  4979.9   55.55  4982.8   52.78
  5008.7   52.89  5018.9   54.31  5020.1   55.49  5022.6   57.73  5032.7   60.32
    5059   59.45  5107.9   58.25  5412.9   58.72  5562.9   63.04  5567.9   63.32
  5712.9   63.45  5882.9   63.85  6097.9    64.7  6137.9   68.34    6175   69.78
#Mann= 5 , 1 , 0
 4075.20     0.2       0  4075.2    0.15       0  4978.3   0.045       0
  5022.6    0.15       0    6175     0.2       0
Bank Sta=4978.30,5022.60
Exp/Cntr=0.3,0.1

Type RM Length L Ch R = 1 ,32122.0,967,967,967
BEGIN DESCRIPTION:
Cross Section Bear Creek 42.0
END DESCRIPTION:
#Sta/Elev= 30
  4115.1   73.41  4155.1   71.49  4185.1   68.04  4235.1   64.38  4300.1   62.06
  4355.1   62.75  4370.1   61.91  4520.1   62.39  4630.1   62.08  4670.1   60.79
  4798.5   61.08  4848.5   58.47  4943.5    59.7  4953.5   58.32 4977.85   57.13
 4982.35    52.3 5008.25   52.41 5018.45   53.83 5022.15   57.25  5037.6   60.57
  5067.6   61.17  5087.6   59.37  5452.6   58.85  5582.6      64  5700.1   64.76
  5747.6   64.32  5802.6   62.52  6192.6   63.88  6252.6   67.28  6281.4   70.13
#Mann= 4 , 1 , 0
 4115.10    0.15       0 4977.85   0.045       0 5022.15    0.15       0
  5700.1      10       0
Bank Sta=4977.85,5022.15
Exp/Cntr=0.5,0.3

Type RM Length L Ch R = 1 ,31155.0,52,52,52
BEGIN DESCRIPTION:
Upstream Section of Bridge/Culvert/Weir
END DESCRIPTION:
#Sta/Elev= 30
  4256.7   80.05  4441.7   73.37  4551.7   67.91  4706.7   64.25  4776.1   57.71
  4878.9   57.56  4926.4   60.07  4958.4   57.72  4963.1   52.88    4990    51.7
  5015.5   52.18  5025.7   50.41    5037   52.91  5044.4   59.22  5076.8   62.41
  5121.7   54.68  5319.9   59.99  5454.9   59.61  5644.9   60.58  5719.9   59.04
  5809.9   60.54  5854.9   60.08  6039.9   63.01  6159.9   63.31  6176.6   64.28
  6556.6   64.54  6671.6   65.83  6731.6   68.21  6766.6   67.27  6800.5    69.8
#Mann= 5 , 1 , 0
 4256.70     0.2       0  4256.7    0.15       0  4958.4   0.045       0
  5044.4    0.15       0  6800.5     0.2       0
#XS Ineff= 2 , 0
       0    4916    70.2    5087       0    65.9
Bank Sta=4958.40,5044.40
Exp/Cntr=0.5,0.3

Type RM Length L Ch R = 3 ,31129.0,,,
BEGIN DESCRIPTION:
HWY 903
Structure ID: L_BEACR3
END DESCRIPTION:
Bridge Culvert--1,0,-1,-1, 0
Deck Dist Width WeirC Skew NumUp NumDn MinLoCord MaxHiCord MaxSubmerge Is_Ogee
10,32,2.6,, 60, 60,,,0.95,0,1,1,,
  4256.7  4269.2  4286.7  4351.7  4406.7  4424.2  4436.7  4441.7  4459.2  4466.7
  4474.2  4509.2  4519.2  4551.7  4566.7  4573.6  4578.6  4628.6  4638.6  4706.7
 4721.38 4721.49  4721.6  4776.1  4828.1  4878.9 4926.61  4926.7 4926.99 5077.07
 5078.29  5078.4  5121.7 5239.77 5239.88    5276  5319.9  5361.3  5454.9  5644.9
  5694.9  5714.9  5719.9  5809.9  5854.9  5939.9  5974.9  6004.9  6024.9  6039.9
  6159.9  6176.6  6551.6  6556.6  6671.6  6706.6  6726.6  6731.6  6766.6  6800.5
   80.04   84.33   83.71   81.22   79.24   78.15   77.87   77.75   76.96   76.88
   76.81   75.14   75.01   73.44   72.91   72.66   72.17   70.86   70.98   68.96
   68.55   71.35   71.35   71.19   71.03   70.87   70.63   70.54   70.27    70.3
   70.69   70.73    70.3   69.11   66.31    66.2   65.96    65.9   65.92   65.94
   65.95   65.95   65.95   65.96   65.96   66.02   66.06   66.09   66.12   66.14
   66.41   66.42   66.55   66.55   66.59    66.6   68.08    68.2   67.26   69.79
   80.04   79.85   79.58   76.21   74.05    73.9   73.17   73.36   72.13    71.6
   71.27   69.75   69.31    67.9   68.09   67.84   67.67   65.89   65.46   64.24
   63.45   63.44   63.44    57.7   58.07   57.55   60.04   65.94   65.67    65.7
   66.09   62.12   54.67    57.6    57.6   58.29   59.98   60.26    59.6   60.57
   59.25   59.37   59.03   60.53   60.07   61.61   61.59   62.54   62.37      63
    63.3   64.27   64.76   64.53   65.82   66.59   68.08    68.2   67.26   69.79
  4256.7  4269.2  4286.7  4351.7  4406.7  4424.2  4436.7  4441.7  4459.2  4466.7
  4474.2  4509.2  4519.2  4551.7  4566.7  4573.6  4578.6  4628.6  4638.6  4706.7
 4721.38 4721.49  4721.6  4776.1  4828.1  4878.9 4926.61  4926.7 4926.99 5077.07
 5078.29  5078.4  5121.7 5239.77 5239.88    5276  5319.9  5361.3  5454.9  5644.9
  5694.9  5714.9  5719.9  5809.9  5854.9  5939.9  5974.9  6004.9  6024.9  6039.9
  6159.9  6176.6  6551.6  6556.6  6671.6  6706.6  6726.6  6731.6  6766.6  6800.5
   80.04   84.33   83.71   81.22   79.24   78.15   77.87   77.75   76.96   76.88
   76.81   75.14   75.01   73.44   72.91   72.66   72.17   70.86   70.98   68.96
   68.55   71.35   71.35   71.19   71.03   70.87   70.63   70.54   70.27    70.3
   70.69   70.73    70.3   69.11   66.31    66.2   65.96    65.9   65.92   65.94
   65.95   65.95   65.95   65.96   65.96   66.02   66.06   66.09   66.12   66.14
   66.41   66.42   66.55   66.55   66.59    66.6   68.08    68.2   67.26   69.79
   79.94   79.75   79.48   76.11   73.95    73.8   73.07   73.26   72.03    71.5
   71.17   69.65   69.21    67.8   67.99   67.74   67.57   65.79   65.36   64.14
   63.35   63.34   63.34    57.6   57.97   57.45   59.94   65.84   65.57    65.6
   65.99   62.02   54.57    57.5    57.5   58.19   59.88   60.16    59.5   60.47
   59.15   59.27   58.93   60.43   59.97   61.51   61.49   62.44   62.27    62.9
    63.2   64.17   64.66   64.43   65.72   66.49   67.98    68.1   67.16   69.69
Pier Skew, UpSta & Num, DnSta & Num=,4975.7, 2 ,4975.7, 2 , 0 , 0 , 0 ,,
     1.4     1.4
   51.24   66.68
     1.4     1.4
   51.14   66.58
Pier Skew, UpSta & Num, DnSta & Num=,5025.7, 2 ,5025.7, 2 , 0 , 0 , 0 ,,
     1.4     1.4
   49.52   66.69
     1.4     1.4
   49.42   66.59
Abutment Skew #Up #Dn=, 2 , 2
 4926.50 4952.40
   65.94   58.09
 4926.50 4952.40
   65.84   57.99
Abutment Skew #Up #Dn=, 2 , 2
 5061.50 5078.49
   61.39   66.09
 5061.50 5078.49
   61.29   65.99
BR Coef= 1 , 1 , 0 ,1.25, 0 ,,,0.8,0,2,0,
Wspro=,,,, 1 ,,,, 0 ,,,, 0 ,,,,-1 ,-1 ,-1 , 0 , 0 , 0 , 0 , 0
BC Design=,, 0 ,, 0 ,,,,,,
BR U #Sta/Elev= 107
  4256.7   80.04  4269.2   79.85  4286.7   79.58  4319.2    77.9  4324.2   77.64
  4351.7   76.21  4404.2   74.15  4406.7   74.05  4424.2    73.9  4426.7   73.88
  4436.7   73.17  4441.7   73.36  4449.2   72.83  4459.2   72.13  4466.7    71.6
  4474.2   71.27  4509.2   69.75  4519.2   69.31  4543.6   68.25  4551.7    67.9
  4566.7   68.09  4573.6   67.84  4578.6   67.67  4628.6   65.89  4631.7   65.78
  4638.6   65.46  4641.7   65.31  4673.6   64.78  4706.7   64.24 4721.38   63.45
 4721.49   63.44  4721.6   63.44  4721.7   63.43  4722.4    63.2  4776.1    57.7
  4828.1   58.07  4878.9   57.55  4926.4   60.06  4926.5   60.05 4926.61   60.04
  4926.7   60.04 4926.99   60.02  4927.1   60.01 4927.21      60  4952.3    58.1
  4952.4   58.09  4958.4   57.71  4963.1   52.87  4975.7   52.27    4990   51.69
  5015.5   52.17  5025.7    50.4    5037    52.9  5044.4   59.21  5061.4   61.38
  5061.5   61.39  5076.8    62.4 5076.85   62.39 5076.96   62.37 5077.07   62.35
 5078.29   62.14  5078.4   62.12  5078.5   62.11  5121.7   54.67  5166.2   55.65
    5216   57.15 5239.66    57.6 5239.77    57.6 5239.88    57.6  5251.3   57.82
    5276   58.29  5291.3   58.88  5316.3   59.84  5319.9   59.98  5361.3   60.26
  5364.9   60.28  5386.3   60.12  5454.9    59.6  5644.9   60.57  5694.9   59.25
  5714.9   59.37  5719.9   59.03  5809.9   60.53  5854.9   60.07  5902.4   60.93
  5939.9   61.61  5974.9   61.59  6004.9   62.54  6024.9   62.37  6039.9      63
  6042.1   63.01  6082.1   63.11  6133.2   63.23  6159.9    63.3  6166.6    63.7
  6176.6   64.27  6551.6   64.76  6556.6   64.53  6671.6   65.82  6706.6   66.59
  6707.2   66.63  6726.6   68.08  6731.6    68.2  6761.6   67.22  6766.6   67.26
  6776.6   67.83  6800.5   69.79
BR U #Mann= 5
 4256.70     0.2  4256.7    0.15  4958.4   0.045  5044.4    0.15  6800.5     0.2
BR U Banks=4958.40,5044.40
BR D #Sta/Elev= 107
  4256.7   79.94  4269.2   79.75  4286.7   79.48  4319.2    77.8  4324.2   77.54
  4351.7   76.11  4404.2   74.05  4406.7   73.95  4424.2    73.8  4426.7   73.78
  4436.7   73.07  4441.7   73.26  4449.2   72.73  4459.2   72.03  4466.7    71.5
  4474.2   71.17  4509.2   69.65  4519.2   69.21  4543.6   68.15  4551.7    67.8
  4566.7   67.99  4573.6   67.74  4578.6   67.57  4628.6   65.79  4631.7   65.68
  4638.6   65.36  4641.7   65.21  4673.6   64.68  4706.7   64.14 4721.38   63.35
 4721.49   63.34  4721.6   63.34  4721.7   63.33  4722.4    63.1  4776.1    57.6
  4828.1   57.97  4878.9   57.45  4926.4   59.96  4926.5   59.95 4926.61   59.94
  4926.7   59.94 4926.99   59.92  4927.1   59.91 4927.21    59.9  4952.3      58
  4952.4   57.99  4958.4   57.61  4963.1   52.77  4975.7   52.17    4990   51.59
  5015.5   52.07  5025.7    50.3    5037    52.8  5044.4   59.11  5061.4   61.28
  5061.5   61.29  5076.8    62.3 5076.85   62.29 5076.96   62.27 5077.07   62.25
 5078.29   62.04  5078.4   62.02  5078.5   62.01  5121.7   54.57  5166.2   55.55
    5216   57.05 5239.66    57.5 5239.77    57.5 5239.88    57.5  5251.3   57.72
    5276   58.19  5291.3   58.78  5316.3   59.74  5319.9   59.88  5361.3   60.16
  5364.9   60.18  5386.3   60.02  5454.9    59.5  5644.9   60.47  5694.9   59.15
  5714.9   59.27  5719.9   58.93  5809.9   60.43  5854.9   59.97  5902.4   60.83
  5939.9   61.51  5974.9   61.49  6004.9   62.44  6024.9   62.27  6039.9    62.9
  6042.1   62.91  6082.1   63.01  6133.2   63.13  6159.9    63.2  6166.6    63.6
  6176.6   64.17  6551.6   64.66  6556.6   64.43  6671.6   65.72  6706.6   66.49
  6707.2   66.53  6726.6   67.98  6731.6    68.1  6761.6   67.12  6766.6   67.16
  6776.6   67.73  6800.5   69.69
BR D #Mann= 5
 4256.70     0.2  4256.7    0.15  4958.4   0.045  5044.4    0.15  6800.5     0.2
BR D Banks=4958.40,5044.40

Type RM Length L Ch R = 1 ,31103.0,1710,1710,1710
BEGIN DESCRIPTION:
Downstream Section of Bridge/Culvert/Weir
END DESCRIPTION:
#Sta/Elev= 30
  4256.7   79.89  4441.7   73.21  4551.7   67.75  4706.7   64.09  4776.1   57.55
  4878.9    57.4  4926.4   59.91  4958.4   57.56  4963.1   52.72    4990   51.54
  5015.5   52.02  5025.7   50.25    5037   52.75  5044.4   59.06  5076.8   62.25
  5121.7   54.52  5319.9   59.83  5454.9   59.45  5644.9   60.42  5719.9   58.88
  5809.9   60.38  5854.9   59.92  6039.9   62.85  6159.9   63.15  6176.6   64.12
  6556.6   64.38  6671.6   65.67  6731.6   68.05  6766.6   67.11  6800.5   69.64
#Mann= 5 , 1 , 0
 4256.70     0.2       0  4256.7    0.15       0  4958.4   0.045       0
  5044.4    0.15       0  6800.5     0.2       0
#XS Ineff= 2 , 0
       0    4916    70.2    5087       0    65.1
Bank Sta=4958.40,5044.40
Exp/Cntr=0.5,0.3

Type RM Length L Ch R = 1 ,29393.0,958,958,958
BEGIN DESCRIPTION:
Cross Section CCX_L69
Located At: CCX_L69 CNTRL
END DESCRIPTION:
#Sta/Elev= 30
  4380.2   71.94  4455.2   66.69  4460.2   66.18  4660.2   57.73  4815.2   56.31
  4943.5   56.79  4959.3   56.88  4980.9   57.08  4985.8   52.49    4990   51.02
  4999.3   50.82  5013.6   49.92  5014.3   52.52  5017.7    57.2    5036   57.45
    5061   57.06  5253.4   55.85  5388.4   57.66  5473.4   57.88  5628.4   58.46
  5788.4   60.92  5963.4   60.74  6043.4   60.66  6383.4   62.28  6583.4   63.53
  6733.4   63.68  6848.4   66.65  7283.4   66.74  7328.4   66.85  7378.7   67.64
#Mann= 5 , 1 , 0
 4380.20     0.2       0  4380.2    0.14       0  4980.9   0.045       0
  5017.7    0.14       0  7378.7     0.2       0
Bank Sta=4980.90,5017.70
Exp/Cntr=0.3,0.1

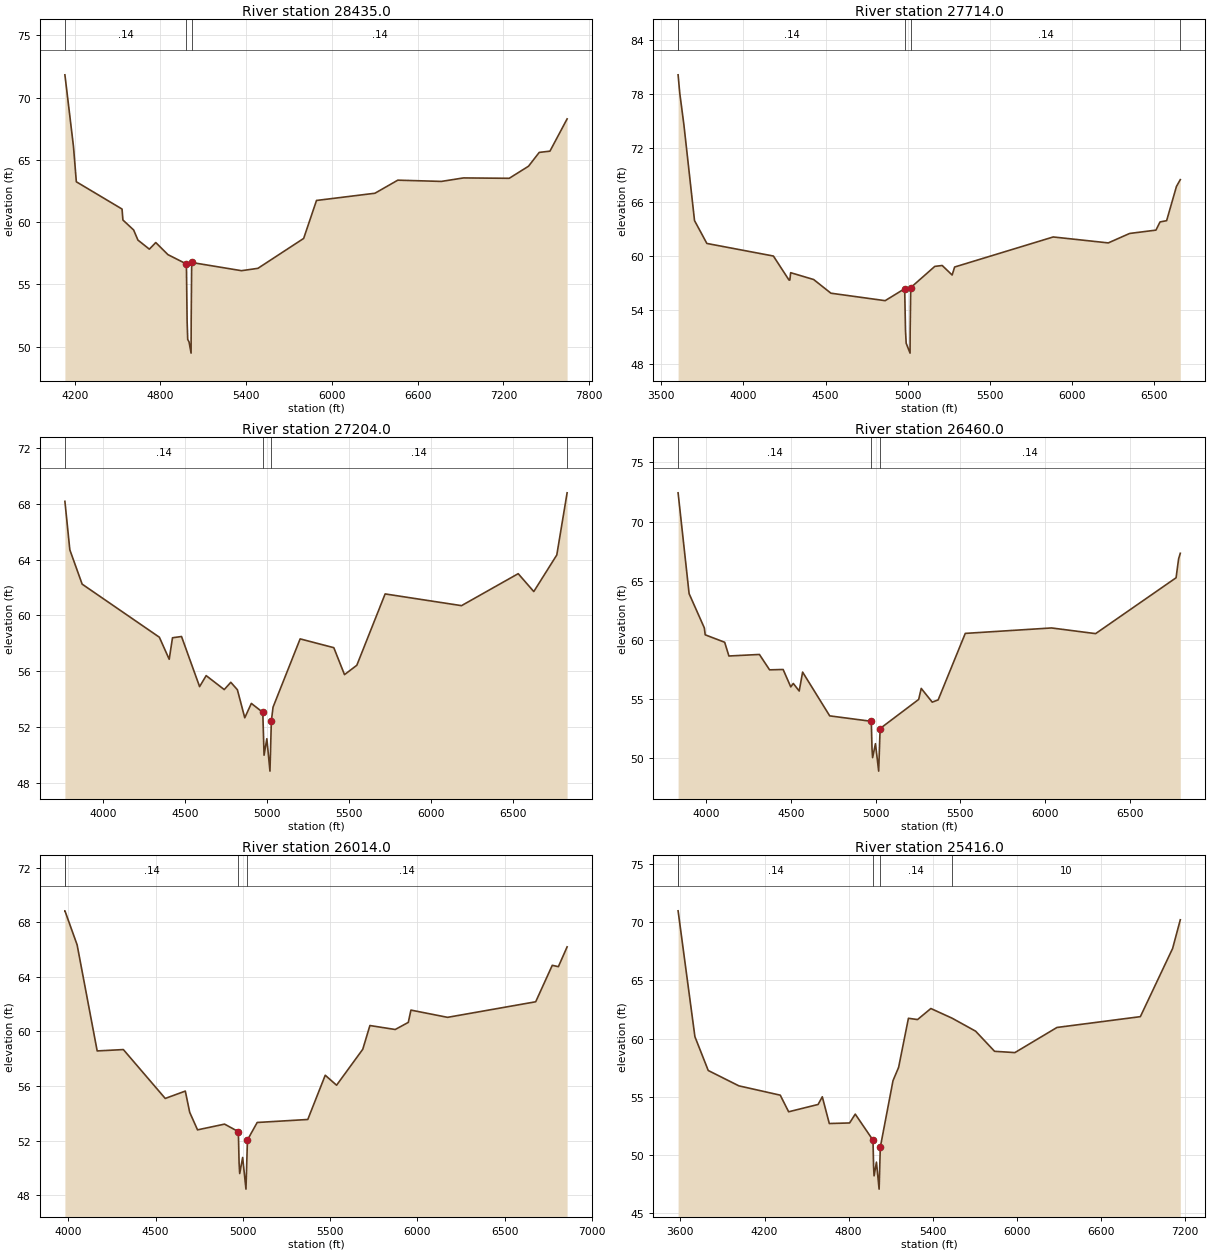
Type RM Length L Ch R = 1 ,28435.0,721,721,721
BEGIN DESCRIPTION:
Cross Section Bear Creek 38.0
END DESCRIPTION:
#Sta/Elev= 30
  4131.1   71.83  4191.1   66.08  4211.1   63.24  4531.1   61.05  4537.2   60.17
  4612.2   59.37  4642.2   58.56  4722.2   57.83  4767.2   58.36  4852.2   57.39
  4981.6   56.64  4986.5   52.05  4990.7   50.58    5000   50.38  5014.3   49.48
    5015   52.08  5018.4   56.76  5367.2    56.1  5482.2   56.29  5802.2   58.69
  5892.2   61.74  6301.1   62.32  6461.1   63.37  6766.1   63.27  6921.1   63.55
  7241.1   63.52  7376.1   64.49  7451.1    65.6  7526.1    65.7  7646.2   68.29
#Mann= 3 , 1 , 0
 4131.10    0.14       0  4981.6   0.045       0  5018.4    0.14       0
Bank Sta=4981.60,5018.40
Exp/Cntr=0.3,0.1

Type RM Length L Ch R = 1 ,27714.0,510,510,510
BEGIN DESCRIPTION:
Cross Section Bear Creek 37.0
END DESCRIPTION:
#Sta/Elev= 30
  3602.8   80.17  3612.8   78.15  3637.8   74.67  3702.8   63.97  3777.8   61.43
  4182.8   60.03  4277.8   57.36  4282.8   57.36  4287.8   58.18  4427.8   57.42
  4532.8    55.9  4862.8   55.07  4981.6    56.4  4986.5   51.81  4990.7   50.34
  5014.3   49.24    5015   51.84  5018.4   56.52  5164.9   58.88  5209.9   58.98
  5270.5   57.92  5285.5   58.81  5885.5   62.15  6220.5   61.49  6350.5   62.54
  6510.5   62.91  6535.5   63.82  6575.5   63.96  6635.5   67.77  6658.8   68.52
#Mann= 5 , 1 , 0
 3602.80     0.2       0  3602.8    0.14       0  4981.6   0.045       0
  5018.4    0.14       0  6658.8     0.2       0
Bank Sta=4981.60,5018.40
Exp/Cntr=0.3,0.1

Type RM Length L Ch R = 1 ,27204.0,744,744,744
BEGIN DESCRIPTION:
Cross Section Bear Creek 36.0
END DESCRIPTION:
#Sta/Elev= 30
  3769.2   68.17  3799.2    64.7  3874.2   62.24  4344.2   58.44  4404.2   56.86
  4424.2    58.4  4479.2   58.49  4589.2    54.9  4629.2   55.69  4739.2   54.69
  4779.2   55.21  4819.2   54.68  4864.2   52.67  4904.2    53.7 4973.95   53.06
 4981.65   49.99 4998.55   51.17 5017.55   48.85 5026.05   52.45  5036.3   53.43
  5201.3   58.32  5406.3   57.69  5471.3   55.76  5546.3   56.43  5718.7   61.54
  6183.7    60.7  6528.7   62.99  6623.7   61.71  6763.7   64.33  6826.5   68.78
#Mann= 4 , 1 , 0
 3769.20    0.14       0 4973.95   0.045       0 5026.05    0.14       0
  6826.5     0.2       0
Bank Sta=4973.95,5026.05
Exp/Cntr=0.3,0.1

Type RM Length L Ch R = 1 ,26460.0,446,446,446
BEGIN DESCRIPTION:
Cross Section Bear Creek 35.0
END DESCRIPTION:
#Sta/Elev= 30
  3833.5   72.43  3898.5   63.91  3988.5   61.01  3993.5   60.43  4108.5    59.8
  4133.5   58.64  4313.5   58.77  4373.5   57.47  4453.5    57.5  4498.5   56.03
  4513.5   56.32  4548.5   55.68  4568.5   57.28  4728.5   53.58 4973.95   53.12
 4978.15   50.83 4981.65   50.05 4998.55   51.23 5017.55   48.91 5026.05   52.51
  5253.7   54.97  5268.7    55.9  5333.7   54.74  5368.7   54.93  5528.7   60.55
    6038   61.01    6298   60.53    6773   65.25    6788   66.85    6798   67.32
#Mann= 3 , 1 , 0
 3833.50    0.14       0 4973.95   0.045       0 5026.05    0.14       0
Bank Sta=4973.95,5026.05
Exp/Cntr=0.3,0.1

Type RM Length L Ch R = 1 ,26014.0,598,598,598
BEGIN DESCRIPTION:
Cross Section Bear Creek 34.0
END DESCRIPTION:
#Sta/Elev= 30
    3980   68.83  3980.1   68.83    4050   66.34    4165   58.57    4315   58.67
    4555   55.09    4670   55.63    4695   54.08    4740   52.79    4895   53.21
 4973.95   52.66 4978.15   50.37 4981.65   49.59 4998.55   50.77 5017.55   48.45
 5026.05   52.05  5081.8   53.33  5371.8   53.55  5471.8   56.79  5536.8   56.06
  5686.8   58.69  5727.8   60.43  5872.8   60.14  5947.8   60.66  5962.8   61.56
  6172.8   61.03  6677.8   62.17  6772.8   64.84  6807.8   64.74  6857.8   66.19
#Mann= 4 , 1 , 0
 3980.00     0.2       0  3980.1    0.14       0 4973.95   0.045       0
 5026.05    0.14       0
Bank Sta=4973.95,5026.05
Exp/Cntr=0.3,0.1

Type RM Length L Ch R = 1 ,25416.0,503,503,503
BEGIN DESCRIPTION:
Cross Section Bear Creek 33.0
END DESCRIPTION:
#Sta/Elev= 30
  3583.5   70.98  3703.5   60.16  3798.5   57.25  4017.2   55.93  4312.2   55.13
  4372.2    53.7  4582.2   54.33  4612.2   54.99  4662.2   52.69  4807.2   52.74
  4847.2    53.5 4973.95   51.26 4978.15   48.97 4981.65   48.19 4998.55   49.37
 5017.55   47.05 5026.05   50.65  5116.7   56.38  5156.7   57.52  5226.7   61.74
  5291.7   61.63  5386.7   62.58  5537.9   61.75  5706.2   60.63  5841.2    58.9
  5986.2   58.79  6286.2   60.95  6881.2   61.88  7111.2   67.74  7166.2   70.21
#Mann= 5 , 1 , 0
 3583.50     0.2       0  3583.5    0.14       0 4973.95   0.045       0
 5026.05    0.14       0  5537.9      10       0
Bank Sta=4973.95,5026.05
Exp/Cntr=0.3,0.1