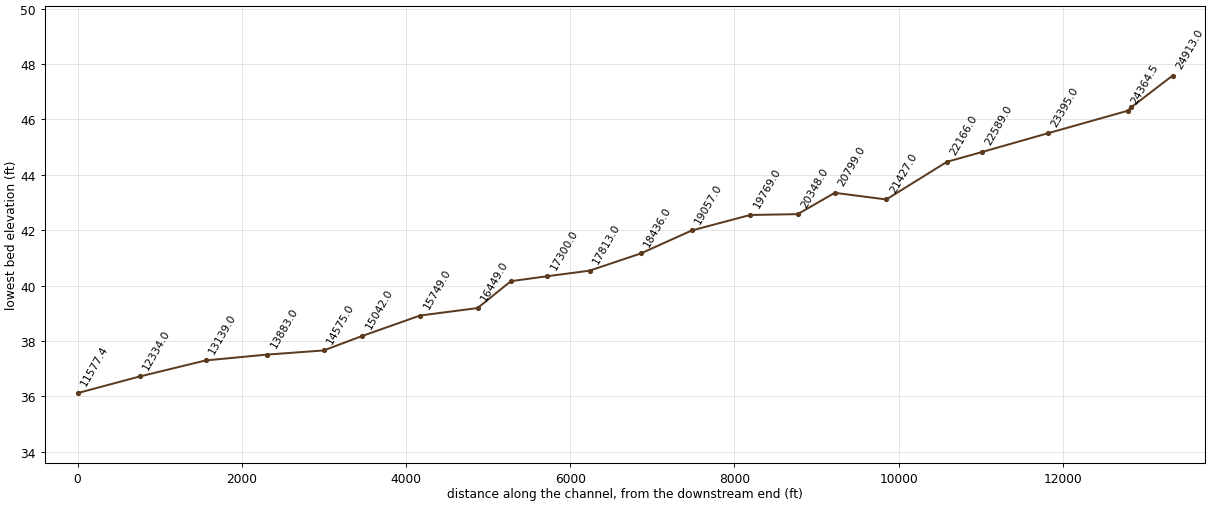
HEC-RAS study 04072003_Bear_Creek.prj: Bear Creek

--- 04072003_Bear_Creek.g01 (geometry) --- (continued)

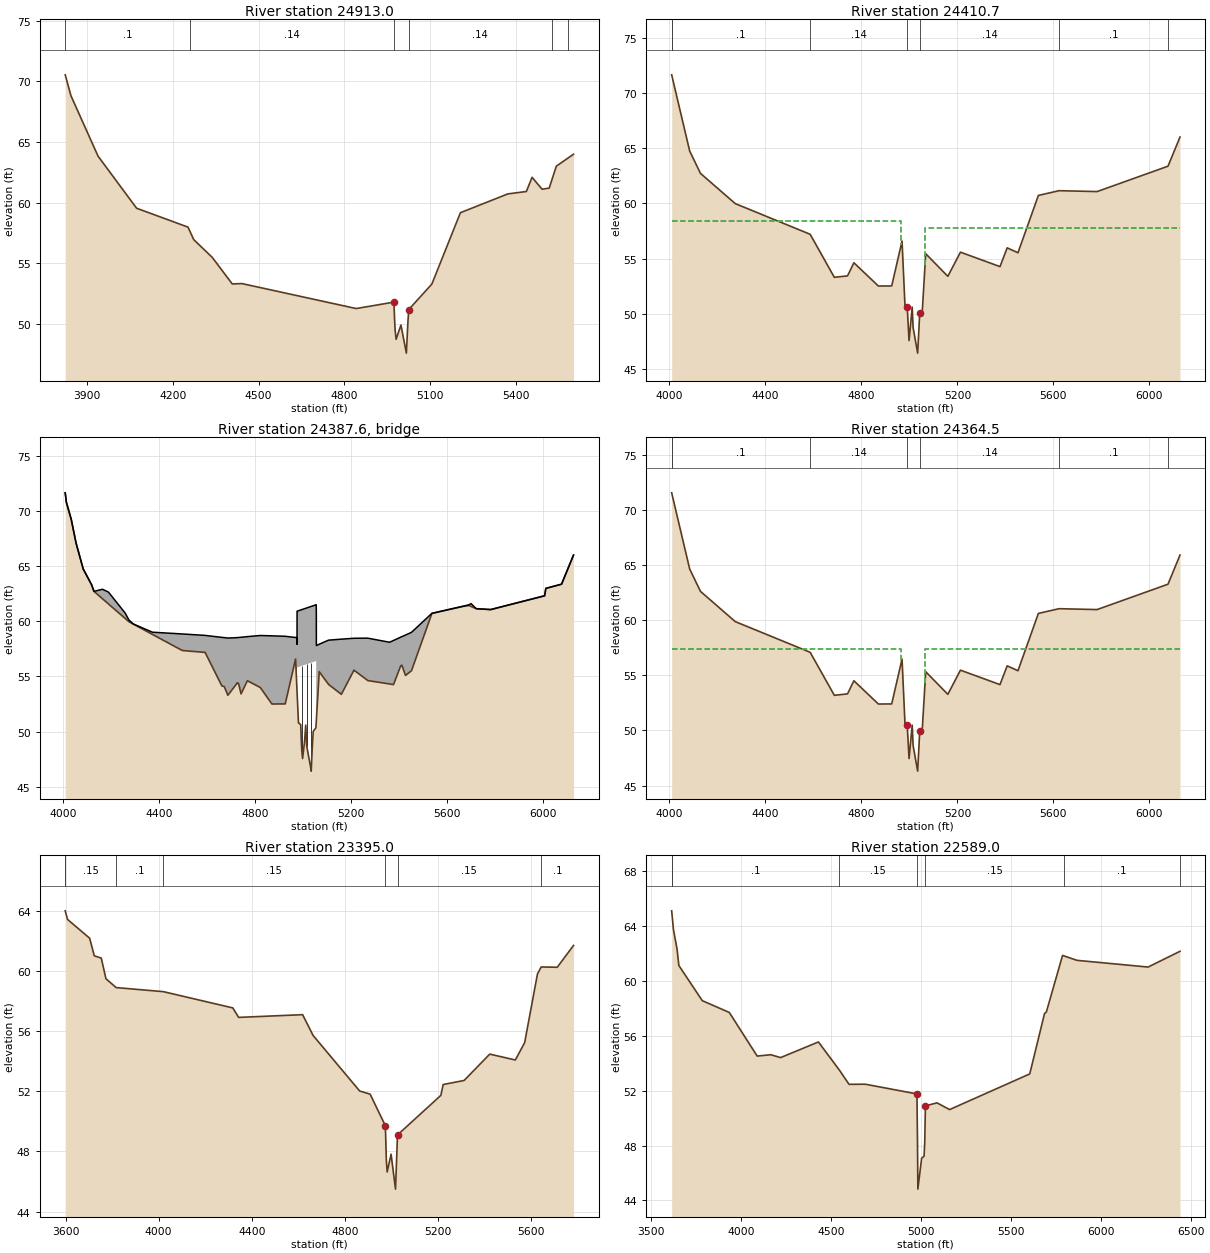
Type RM Length L Ch R = 1 ,24913.0,502.3,502.3,502.3
BEGIN DESCRIPTION:
Cross Section Bear Creek 32.0
END DESCRIPTION:
#Sta/Elev= 30
  3822.9   70.55  3842.9   68.83  3937.9   63.84  4072.9   59.54  4252.9   57.98
  4261.3   57.55  4272.9   56.95  4337.9   55.48  4407.9   53.29  4441.8   53.32
  4841.8   51.26 4973.95   51.79 4976.35   50.32 4978.15    49.5 4981.65   48.72
 4998.55    49.9 5017.55   47.58 5023.15   50.23 5026.05   51.18  5106.8   53.28
  5206.8   59.17  5372.7   60.72  5437.7   60.92  5457.7   62.09  5492.7   61.11
  5517.7    61.2  5526.9   61.87  5542.7   63.01  5584.7    63.7  5602.9      64
#Mann= 6 , 1 , 0
 3822.90     0.1       0  4261.3    0.14       0 4973.95   0.045       0
 5026.05    0.14       0  5526.9     0.1       0  5584.7     0.2       0
Bank Sta=4973.95,5026.05
Exp/Cntr=0.5,0.3

Type RM Length L Ch R = 1 ,24410.7,46.2,46.2,46.2
BEGIN DESCRIPTION:
Upstream Section of Bridge/Culvert/Weir
END DESCRIPTION:
#Sta/Elev= 30
  4009.1   71.66  4084.1   64.76  4129.1   62.73  4274.1   59.99  4586.3   57.21
  4687.1   53.31  4742.1   53.44  4768.6   54.63  4870.7   52.52  4926.2   52.53
  4969.3    56.6  4981.4   50.81  4990.8   50.65  4998.5   47.58  5011.6   50.61
  5015.4   48.76  5034.4   46.44  5042.9   50.04    5054   50.36  5067.9   55.45
  5160.2    53.4  5212.7   55.59  5377.5   54.28  5407.5   55.98  5452.5   55.54
  5537.5   60.73  5623.7   61.16  5782.3   61.08  6077.8   63.38  6127.8   66.02
#Mann= 7 , 1 , 0
 4009.10     0.2       0  4009.1     0.1       0  4586.3    0.14       0
  4990.8   0.045       0  5042.9    0.14       0  5623.7     0.1       0
  6077.8     0.2       0
#XS Ineff= 2 , 0
       0    4965    58.4    5065       0    57.8
Bank Sta=4990.80,5042.90
Exp/Cntr=0.5,0.3

Type RM Length L Ch R = 3 ,24387.6,,,
BEGIN DESCRIPTION:
MAYS STORE RD
Structure ID: L_BEACR2
END DESCRIPTION:
Bridge Culvert--1,0,-1,-1, 0
Deck Dist Width WeirC Skew NumUp NumDn MinLoCord MaxHiCord MaxSubmerge Is_Ogee
10,26.2,2.6,, 57, 57,,,0.95,0,1,1,,
  4009.1  4014.1  4034.1  4054.1  4084.1  4119.1  4129.1  4164.5  4189.5  4259.5
  4274.1  4292.5  4372.5  4497.1  4592.1  4662.1  4672.1  4687.1  4727.1  4732.1
  4742.1  4768.6  4822.1  4870.7  4926.2  4969.3  4974.9 4975.01  4975.1 4975.33
 4975.44 5055.19  5055.3 5055.69  5055.8 5055.91  5067.9  5106.7  5160.2  5212.7
  5270.3  5360.8  5377.5  5407.5  5412.5  5427.5  5452.5  5537.5  5667.3  5692.3
  5700.8  5722.3  5782.3  6007.3  6012.3  6077.8  6127.8
   71.64   70.77   69.25   67.11   64.74   63.31   62.71    62.9   62.64   60.73
   60.13   59.76   59.01   58.85   58.72   58.54   58.52   58.48   58.52   58.53
   58.55   58.61   58.71   58.68   58.64   58.53   58.51   58.36   58.23   57.91
   60.91    61.5    61.5    60.8    60.8    57.8   57.92   58.29   58.38   58.46
   58.47    58.1   58.26   58.56   58.61   58.75      59   60.72   61.36    61.5
    61.6   61.14   61.06   62.31   62.98   63.36      66
   71.64   70.77   69.25   67.11   64.74   63.31   62.71   62.04   61.57   60.25
   59.97   59.75   58.81   57.35   57.18   54.14   54.08   53.29   54.43   54.32
   53.42   54.61      54    52.5   52.51   56.58    53.9   53.85   56.13   55.81
   55.81    56.4   50.82   50.96      51   51.04   55.43   54.28   53.38   55.57
   54.63   54.32   54.26   55.96   56.01   55.09   55.52   60.71   61.35   61.42
   61.34   61.14   61.06   62.31   62.98   63.36      66
  4009.1  4014.1  4034.1  4054.1  4084.1  4119.1  4129.1  4164.5  4189.5  4259.5
  4274.1  4292.5  4372.5  4497.1  4592.1  4662.1  4672.1  4687.1  4727.1  4732.1
  4742.1  4768.6  4822.1  4870.7  4926.2  4969.3  4974.9 4975.01  4975.1 4975.33
 4975.44 5055.19  5055.3 5055.69  5055.8 5055.91  5067.9  5106.7  5160.2  5212.7
  5270.3  5360.8  5377.5  5407.5  5412.5  5427.5  5452.5  5537.5  5667.3  5692.3
  5700.8  5722.3  5782.3  6007.3  6012.3  6077.8  6127.8
   71.64   70.77   69.25   67.11   64.74   63.31   62.71    62.9   62.64   60.73
   60.13   59.76   59.01   58.85   58.72   58.54   58.52   58.48   58.52   58.53
   58.55   58.61   58.71   58.68   58.64   58.53   58.51   58.36   58.23   57.91
   60.91    61.5    61.5    60.8    60.8    57.8   57.92   58.29   58.38   58.46
   58.47    58.1   58.26   58.56   58.61   58.75      59   60.72   61.36    61.5
    61.6   61.14   61.06   62.31   62.98   63.36      66
   71.54   70.67   69.15   67.01   64.64   63.21   62.61   61.94   61.47   60.15
   59.87   59.65   58.71   57.25   57.08   54.04   53.98   53.19   54.33   54.22
   53.32   54.51    53.9    52.4   52.41   56.48    53.8   53.75   56.03   55.71
   55.71    56.3   50.72   50.86    50.9   50.94   55.33   54.18   53.28   55.47
   54.53   54.22   54.16   55.86   55.91   54.99   55.42   60.61   61.25   61.32
   61.24   61.04   60.96   62.21   62.88   63.26    65.9
Pier Skew, UpSta & Num, DnSta & Num=,4995.0, 2 ,4995.0, 2 , 0 , 0 , 0 ,,
       1       1
   47.23   56.95
       1       1
   47.13   56.85
Pier Skew, UpSta & Num, DnSta & Num=,5015.4, 2 ,5015.4, 2 , 0 , 0 , 0 ,,
       1       1
   47.68    57.1
       1       1
   47.58      57
Pier Skew, UpSta & Num, DnSta & Num=,5034.4, 2 ,5034.4, 2 , 0 , 0 , 0 ,,
       1       1
   45.49   57.25
       1       1
   45.39   57.15
Abutment Skew #Up #Dn=, 2 , 2
 4974.90 4981.50
   56.13   50.79
 4974.90 4981.50
   56.03   50.69
Abutment Skew #Up #Dn=, 2 , 2
 5054.10 5055.39
   50.38   56.40
 5054.10 5055.39
   50.28   56.30
BR Coef= 1 , 1 , 0 ,1.25, 0 ,,,0.8,0,2,0,
Wspro=,,,, 1 ,,,, 0 ,,,, 0 ,,,,-1 ,-1 ,-1 , 0 , 0 , 0 , 0 , 0
BC Design=,, 0 ,, 0 ,,,,,,
BR U #Sta/Elev= 92
  4009.1   71.64  4014.1   70.77  4034.1   69.25  4054.1   67.11  4084.1   64.74
  4119.1   63.31  4129.1   62.71  4164.5   62.04  4189.5   61.57  4194.5   61.47
  4259.5   60.25  4272.5      60  4274.1   59.97  4292.5   59.75  4372.5   58.81
  4497.1   57.35  4586.3   57.19  4589.5   57.18  4592.1   57.18  4662.1   54.14
  4672.1   54.08  4687.1   53.29  4698.6   53.62  4727.1   54.43  4732.1   54.32
  4742.1   53.42  4761.4   54.29  4768.6   54.61  4817.5   54.05  4822.1      54
  4868.5   52.57  4870.7    52.5  4923.2   52.51  4926.2   52.51  4969.3   56.58
  4974.9    53.9 4975.01   53.85  4975.1    53.8 4975.33   53.69 4975.44   53.64
 4975.55   53.59  4981.4   50.79  4981.5   50.79  4990.8   50.63  4993.2   49.16
    4995   48.34  4998.5   47.56  5006.8   49.13  5011.6   50.59  5014.6    49.3
  5015.4   48.74  5031.3   46.86  5034.4   46.42    5040   49.07  5042.9   50.02
    5054   50.34  5054.1   50.38 5055.19   50.78  5055.3   50.82  5055.4   50.85
 5055.69   50.96  5055.8      51 5055.91   51.04  5067.9   55.43  5106.7   54.28
  5108.4   54.25  5160.2   53.38  5160.9   53.41  5212.7   55.57  5213.1   55.56
  5270.3   54.63  5274.7   54.61  5360.8   54.32  5377.5   54.26  5407.5   55.96
  5412.5   56.01  5427.5   55.09  5452.5   55.52  5537.5   60.71  5607.5   61.06
  5623.7   61.14  5635.8    61.2  5667.3   61.35  5692.3   61.42  5700.8   61.34
  5722.3   61.14  5782.3   61.06  6007.3   62.31  6012.3   62.98  6077.7   63.36
  6077.8   63.36  6127.8      66
BR U #Mann= 7
 4009.10     0.2  4009.1     0.1  4586.3    0.14  4990.8   0.045  5042.9    0.14
  5623.7     0.1  6077.8     0.2
BR U Banks=4990.80,5042.90
BR D #Sta/Elev= 92
  4009.1   71.54  4014.1   70.67  4034.1   69.15  4054.1   67.01  4084.1   64.64
  4119.1   63.21  4129.1   62.61  4164.5   61.94  4189.5   61.47  4194.5   61.37
  4259.5   60.15  4272.5    59.9  4274.1   59.87  4292.5   59.65  4372.5   58.71
  4497.1   57.25  4586.3   57.09  4589.5   57.08  4592.1   57.08  4662.1   54.04
  4672.1   53.98  4687.1   53.19  4698.6   53.52  4727.1   54.33  4732.1   54.22
  4742.1   53.32  4761.4   54.19  4768.6   54.51  4817.5   53.95  4822.1    53.9
  4868.5   52.47  4870.7    52.4  4923.2   52.41  4926.2   52.41  4969.3   56.48
  4974.9    53.8 4975.01   53.75  4975.1    53.7 4975.33   53.59 4975.44   53.54
 4975.55   53.49  4981.4   50.69  4981.5   50.69  4990.8   50.53  4993.2   49.06
    4995   48.24  4998.5   47.46  5006.8   49.03  5011.6   50.49  5014.6    49.2
  5015.4   48.64  5031.3   46.76  5034.4   46.32    5040   48.97  5042.9   49.92
    5054   50.24  5054.1   50.28 5055.19   50.68  5055.3   50.72  5055.4   50.75
 5055.69   50.86  5055.8    50.9 5055.91   50.94  5067.9   55.33  5106.7   54.18
  5108.4   54.15  5160.2   53.28  5160.9   53.31  5212.7   55.47  5213.1   55.46
  5270.3   54.53  5274.7   54.51  5360.8   54.22  5377.5   54.16  5407.5   55.86
  5412.5   55.91  5427.5   54.99  5452.5   55.42  5537.5   60.61  5607.5   60.96
  5623.7   61.04  5635.8    61.1  5667.3   61.25  5692.3   61.32  5700.8   61.24
  5722.3   61.04  5782.3   60.96  6007.3   62.21  6012.3   62.88  6077.7   63.26
  6077.8   63.26  6127.8    65.9
BR D #Mann= 7
 4009.10     0.2  4009.1     0.1  4586.3    0.14  4990.8   0.045  5042.9    0.14
  5623.7     0.1  6077.8     0.2
BR D Banks=4990.80,5042.90

Type RM Length L Ch R = 1 ,24364.5,969.5,969.5,969.5
BEGIN DESCRIPTION:
Downstream Section of Bridge/Culvert/Weir
END DESCRIPTION:
#Sta/Elev= 30
  4009.1   71.53  4084.1   64.63  4129.1    62.6  4274.1   59.86  4586.3   57.08
  4687.1   53.18  4742.1   53.31  4768.6    54.5  4870.7   52.39  4926.2    52.4
  4969.3   56.47  4981.4   50.68  4990.8   50.52  4998.5   47.45  5011.6   50.48
  5015.4   48.63  5034.4   46.31  5042.9   49.91    5054   50.23  5067.9   55.32
  5160.2   53.27  5212.7   55.46  5377.5   54.15  5407.5   55.85  5452.5   55.41
  5537.5    60.6  5623.7   61.03  5782.3   60.95  6077.8   63.25  6127.8   65.89
#Mann= 7 , 1 , 0
 4009.10     0.2       0  4009.1     0.1       0  4586.3    0.14       0
  4990.8   0.045       0  5042.9    0.14       0  5623.7     0.1       0
  6077.8     0.2       0
#XS Ineff= 2 , 0
       0    4965    57.4    5065       0    57.4
Bank Sta=4990.80,5042.90
Exp/Cntr=0.5,0.3

Type RM Length L Ch R = 1 ,23395.0,806,806,806
BEGIN DESCRIPTION:
Cross Section Bear Creek 31.0
END DESCRIPTION:
#Sta/Elev= 30
  3598.5   63.99  3608.5   63.42  3703.5   62.17  3723.5      61  3753.5   60.85
  3773.5   59.48  3817.3   58.89  4020.1   58.62  4318.5   57.54  4343.5   56.91
  4618.5   57.09  4663.5   55.71  4863.5   52.02  4908.5   51.81 4973.95   49.71
 4978.15   47.42 4981.65   46.64 4998.55   47.82 5017.55    45.5 5026.05    49.1
  5212.3   51.73  5222.3   52.45  5312.3   52.72  5422.3   54.47  5532.3   54.08
  5572.3   55.23  5627.3   59.79  5643.2   60.26  5712.3   60.24  5782.3   61.69
#Mann= 7 , 1 , 0
 3598.50     0.2       0  3598.5    0.15       0  3817.3     0.1       0
  4020.1    0.15       0 4973.95   0.045       0 5026.05    0.15       0
  5643.2     0.1       0
Bank Sta=4973.95,5026.05
Exp/Cntr=0.3,0.1

Type RM Length L Ch R = 1 ,22589.0,423,423,423
BEGIN DESCRIPTION:
Cross Section Bear Creek 30.0
END DESCRIPTION:
#Sta/Elev= 30
  3614.4   65.11  3624.4   63.74  3644.4   62.31  3654.4   61.12  3784.4   58.56
  3934.4    57.7  4089.4   54.52  4164.4   54.62  4219.4   54.41  4429.4   55.55
  4546.2   53.49  4599.4   52.46  4689.4   52.47  4976.5   51.76  4979.6    48.2
  4981.6   44.82  5002.6   47.08    5016   47.22  5019.7   48.21  5023.5   50.89
  5087.9   51.11  5157.9   50.62  5602.9   53.22  5685.1   57.63  5695.1   57.73
  5785.1   61.86  5793.9   61.82  5865.1    61.5  6260.1   61.01  6437.3   62.16
#Mann= 7 , 1 , 0
 3614.40     0.2       0  3614.4     0.1       0  4546.2    0.15       0
  4976.5   0.045       0  5023.5    0.15       0  5793.9     0.1       0
  6437.3     0.2       0
Bank Sta=4976.50,5023.50
Exp/Cntr=0.3,0.1

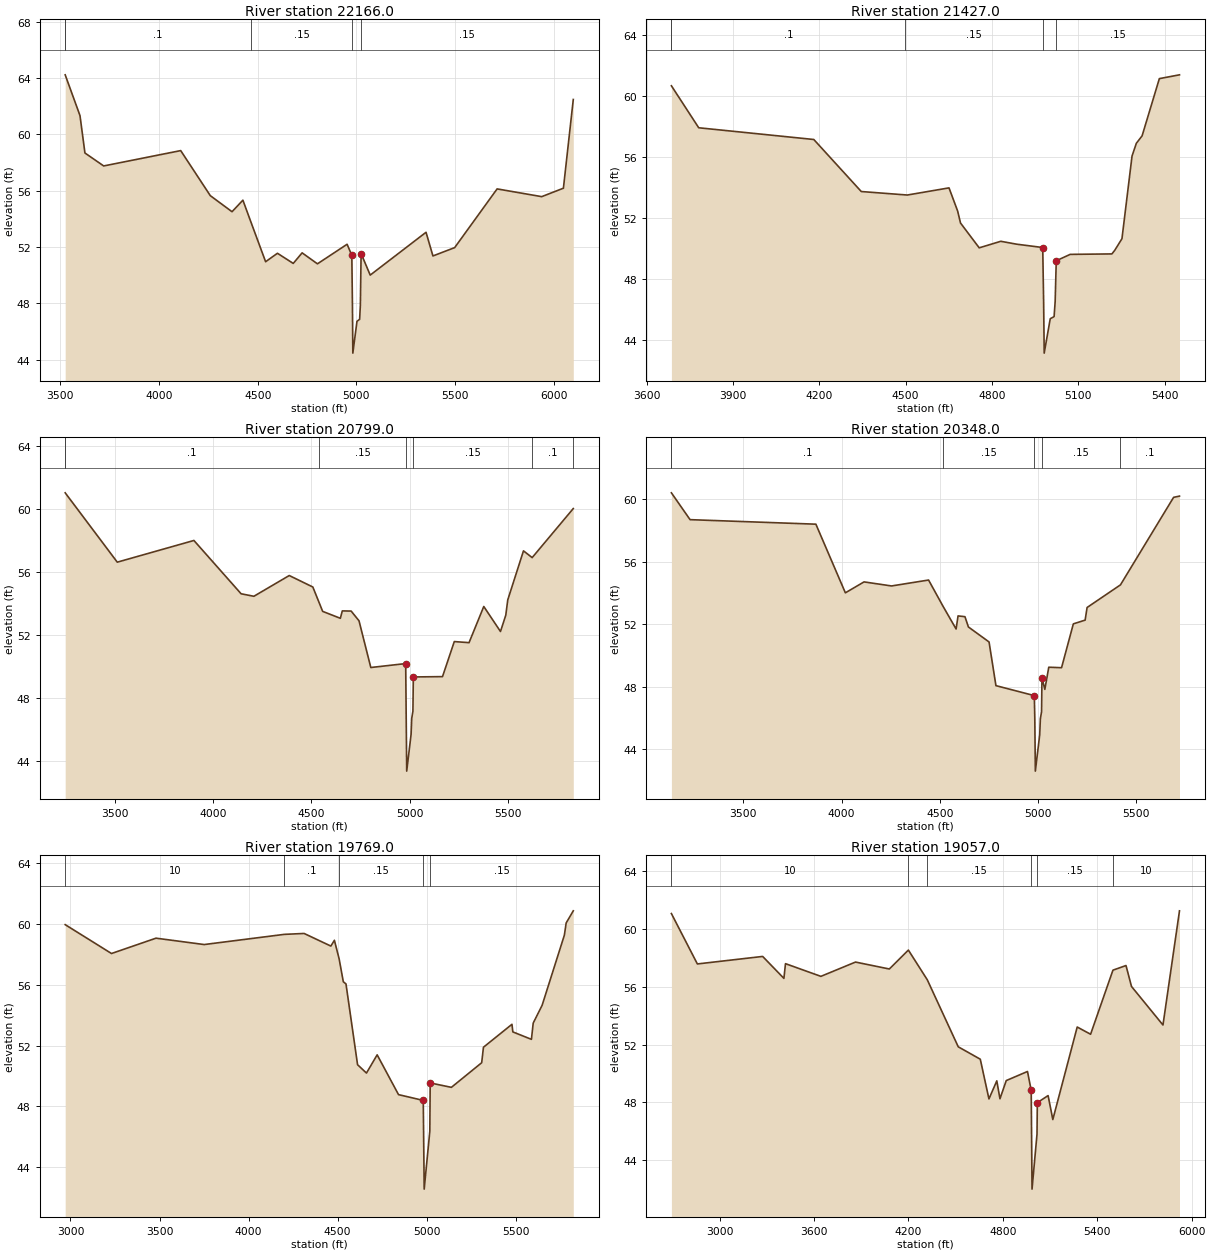
Type RM Length L Ch R = 1 ,22166.0,739,739,739
BEGIN DESCRIPTION:
Cross Section CCX_L68
Located At: CCX_L68 CNTRL
END DESCRIPTION:
#Sta/Elev= 30
  3525.1   64.23  3600.1   61.33  3625.1   58.68  3720.1   57.76  4110.1   58.85
  4260.1   55.65  4370.1   54.51  4425.1   55.33  4467.3   53.72  4540.1   50.96
  4600.1   51.56  4680.1   50.84  4725.1   51.59  4802.6   50.81  4952.9    52.2
  4976.8   51.41  4979.9   47.85  4981.9   44.47  5002.9   46.73  5016.3   46.87
    5020   47.86  5023.8   51.54  5069.9   50.01  5352.6   53.05  5387.6   51.37
  5497.6   51.96  5712.6   56.13  5938.4   55.58  6048.4   56.18  6098.4   62.48
#Mann= 5 , 1 , 0
 3525.10     0.2       0  3525.1     0.1       0  4467.3    0.15       0
  4976.8   0.045       0  5023.8    0.15       0
Bank Sta=4976.80,5023.80
Exp/Cntr=0.3,0.1

Type RM Length L Ch R = 1 ,21427.0,628,628,628
BEGIN DESCRIPTION:
Cross Section Bear Creek 29.0
END DESCRIPTION:
#Sta/Elev= 28
  3685.7   60.68  3780.7   57.92  4180.7   57.15  4345.7   53.73  4499.1   53.51
  4505.7    53.5  4650.7   53.97  4680.7   52.45  4690.7   51.66  4755.7   50.03
  4830.7   50.46  4885.7   50.27  4976.5   50.05  4979.6   46.49  4981.6   43.11
  5002.6   45.37    5016   45.51  5019.7    46.5  5023.5   49.18  5071.9    49.6
  5216.9   49.63  5226.9   49.87  5251.9   50.63  5286.9   56.06  5301.9    56.9
  5321.9   57.39  5381.9   61.15  5451.9    61.4
#Mann= 5 , 1 , 0
 3685.70     0.2       0  3685.7     0.1       0  4499.1    0.15       0
  4976.5   0.045       0  5023.5    0.15       0
Bank Sta=4976.50,5023.50
Exp/Cntr=0.3,0.1

Type RM Length L Ch R = 1 ,20799.0,451,451,451
BEGIN DESCRIPTION:
Cross Section Bear Creek 28.0
END DESCRIPTION:
#Sta/Elev= 30
  3248.1   61.05  3513.1   56.64  3903.1   58.02  4143.1   54.63  4208.1   54.47
  4388.1   55.79  4508.1   55.06  4540.4   54.06  4558.1   53.51  4648.1   53.07
  4658.1   53.54  4703.1   53.53  4743.1   52.91  4803.1   49.94 4980.55   50.19
 4985.75   43.35 5008.05   45.69 5011.25    46.7 5017.35   47.16 5019.45   49.34
  5167.9   49.36  5227.9   51.59  5302.9   51.52  5377.9   53.82  5462.9   52.23
  5489.9   53.27  5499.9   54.24  5579.9   57.36  5624.1   56.93  5833.3   60.05
#Mann= 7 , 1 , 0
 3248.10     0.2       0  3248.1     0.1       0  4540.4    0.15       0
 4980.55   0.045       0 5019.45    0.15       0  5624.1     0.1       0
  5833.3     0.2       0
Bank Sta=4980.55,5019.45
Exp/Cntr=0.3,0.1

Type RM Length L Ch R = 1 ,20348.0,579,579,579
BEGIN DESCRIPTION:
Cross Section Bear Creek 27.0
END DESCRIPTION:
#Sta/Elev= 30
  3134.3   60.42  3229.3    58.7  3869.3   58.41  4019.3   54.01  4114.3   54.71
  4254.3   54.45  4442.6   54.83  4516.5   53.14  4582.6   51.69  4592.6   52.53
  4627.6   52.48  4645.3   51.82  4750.3   50.86  4785.3   48.06 4980.55   47.42
 4983.05   45.92 4985.75   42.58 5008.05   44.92 5011.25   45.93 5017.35   46.39
 5019.45   48.57  5034.1   47.82  5054.1   49.24  5119.1   49.21  5179.1   52.02
  5239.1   52.26  5249.1   53.07  5418.8   54.52  5689.1   60.13  5719.1   60.21
#Mann= 6 , 1 , 0
 3134.30     0.2       0  3134.3     0.1       0  4516.5    0.15       0
 4980.55   0.045       0 5019.45    0.15       0  5418.8     0.1       0
Bank Sta=4980.55,5019.45
Exp/Cntr=0.3,0.1

Type RM Length L Ch R = 1 ,19769.0,712,712,712
BEGIN DESCRIPTION:
Cross Section Bear Creek 26.0
END DESCRIPTION:
#Sta/Elev= 30
  2970.3   59.96  3230.3   58.06  3480.3   59.07  3750.3   58.65  4200.3   59.32
  4311.7   59.38  4461.7   58.55  4481.7   58.93  4508.2   57.71  4531.7    56.2
  4546.7   56.06  4611.7   50.74  4661.7   50.19  4721.7   51.39  4841.7   48.77
 4980.55   48.39 4985.75   42.55 5017.35   46.36 5019.45   49.54  5138.5   49.25
  5308.5   50.87  5318.5   51.89  5478.5    53.4  5483.5    52.9  5587.8   52.41
  5597.8   53.48  5647.8   54.65  5772.8   59.27  5782.8   60.07  5822.8   60.87
#Mann= 5 , 1 , 0
 2970.30      10       0  4200.3     0.1       0  4508.2    0.15       0
 4980.55   0.045       0 5019.45    0.15       0
Bank Sta=4980.55,5019.45
Exp/Cntr=0.3,0.1

Type RM Length L Ch R = 1 ,19057.0,621,621,621
BEGIN DESCRIPTION:
Cross Section Bear Creek 25.0
END DESCRIPTION:
#Sta/Elev= 30
  2693.9   61.08  2858.9   57.59  3273.9   58.11  3408.9   56.59  3418.9   57.61
  3643.9   56.73  3863.9   57.72  4078.9   57.24  4199.9   58.55  4320.3   56.49
  4516.9   51.85  4656.9   50.99  4711.9   48.24  4761.9   49.49  4781.9   48.25
  4821.9   49.51  4956.9   50.14 4980.55   48.83 4985.75   41.99 5017.35    45.8
 5019.45   47.98  5087.9   48.47  5117.9   46.81  5272.9   53.22  5357.9   52.72
    5500   57.16  5582.9   57.48  5617.9   56.03  5817.9   53.36  5922.9   61.27
#Mann= 6 , 1 , 0
 2693.90      10       0  4199.9     0.1       0  4320.3    0.15       0
 4980.55   0.045       0 5019.45    0.15       0    5500      10       0
Bank Sta=4980.55,5019.45
Exp/Cntr=0.3,0.1

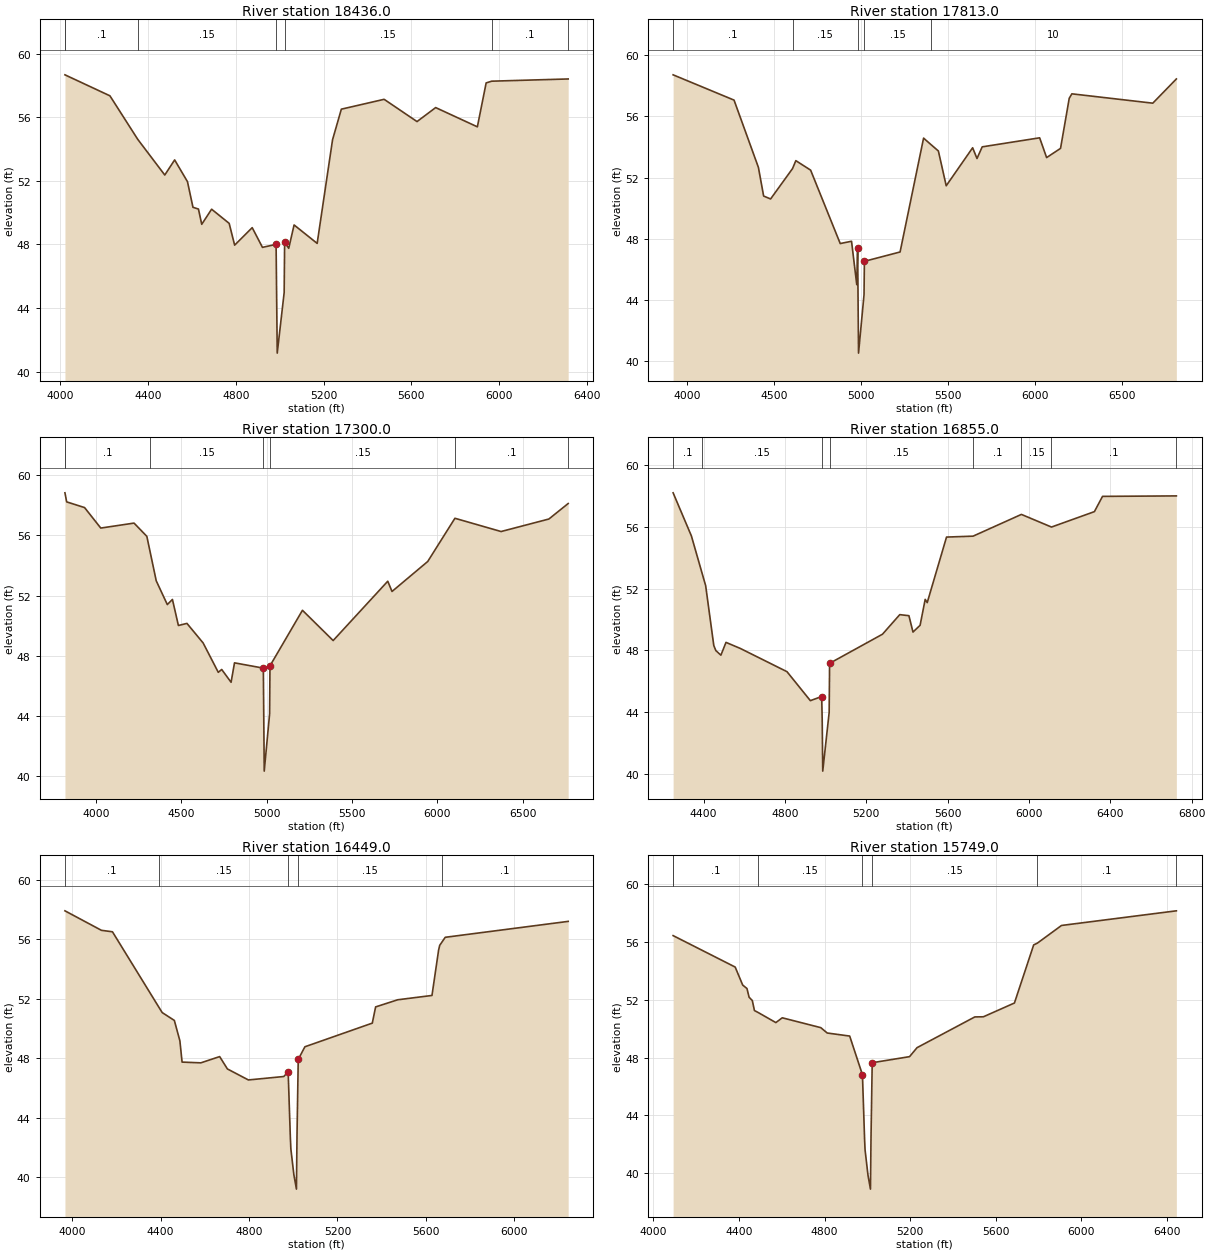
Type RM Length L Ch R = 1 ,18436.0,623,623,623
BEGIN DESCRIPTION:
Cross Section CCX_L23
Located At: CCX_L23 CTRL
END DESCRIPTION:
#Sta/Elev= 30
    4021   58.66    4226   57.34    4353    54.6    4476   52.36    4521   53.31
  4579.5   51.94  4604.5   50.33  4629.5   50.22  4644.5   49.26  4689.5   50.21
  4769.5   49.32  4794.5   47.95  4874.5   49.05  4921.3   47.81  4983.4      48
  4988.6   41.16  5020.2   44.97  5022.3   48.15    5041   47.75  5065.4   49.22
  5170.6   48.06  5240.8   54.58  5280.8    56.5  5475.8   57.12  5625.8   55.72
  5710.8    56.6  5900.8   55.39  5940.8   58.15    5966   58.26  6314.8    58.4
#Mann= 7 , 1 , 0
 4021.00     0.2       0    4021     0.1       0    4353    0.15       0
  4983.4   0.045       0  5022.3    0.15       0    5966     0.1       0
  6314.8     0.2       0
Bank Sta=4983.40,5022.30
Exp/Cntr=0.3,0.1

Type RM Length L Ch R = 1 ,17813.0,513,513,513
BEGIN DESCRIPTION:
Cross Section Bear Creek 24.0
END DESCRIPTION:
#Sta/Elev= 30
  3920.6    58.7  4270.6   57.05  4410.6   52.66  4440.6   50.79  4480.6    50.6
  4606.5   52.58  4625.6    53.1  4710.6   52.48  4880.6   47.69  4945.6   47.84
  4975.6   45.01 4980.55   47.38 4985.75   40.54 5017.35   44.35 5019.45   46.53
  5224.5   47.14  5359.5   54.57  5399.6   54.17  5444.5   53.73  5489.5   51.46
  5641.3   53.94  5666.3   53.24  5696.3      54  6026.3   54.59  6066.3    53.3
  6146.3    53.9  6196.3   57.17  6211.3   57.46  6676.3   56.85  6811.7   58.43
#Mann= 5 , 1 , 0
 3920.60     0.1       0  4606.5    0.15       0 4980.55   0.045       0
 5019.45    0.15       0  5399.6      10       0
Bank Sta=4980.55,5019.45
Exp/Cntr=0.3,0.1

Type RM Length L Ch R = 1 ,17300.0,445,445,445
BEGIN DESCRIPTION:
Cross Section Bear Creek 23.0
END DESCRIPTION:
#Sta/Elev= 30
  3817.7   58.82  3827.7   58.22  3932.7   57.84  4027.7   56.48  4222.7   56.81
  4297.7   55.93  4315.8   54.96  4352.7   52.98  4417.7    51.4  4447.7   51.74
  4482.7   50.01  4532.7   50.15  4627.7   48.85  4716.5    46.9  4736.5   47.09
  4791.5   46.24  4811.5   47.53 4980.55   47.18 4985.75   40.34 5017.35   44.15
 5019.45   47.33  5209.8   51.02  5389.8   49.01  5709.8   52.95  5734.8   52.27
  5944.1   54.26  6103.5   57.13  6374.1   56.25  6654.1   57.08  6767.4   58.11
#Mann= 7 , 1 , 0
 3817.70     0.2       0  3817.7     0.1       0  4315.8    0.15       0
 4980.55   0.045       0 5019.45    0.15       0  6103.5     0.1       0
  6767.4     0.2       0
Bank Sta=4980.55,5019.45
Exp/Cntr=0.3,0.1

Type RM Length L Ch R = 1 ,16855.0,406,406,406
BEGIN DESCRIPTION:
Cross Section Bear Creek 22.0
END DESCRIPTION:
#Sta/Elev= 30
  4249.9   58.21  4339.9   55.41  4390.9   53.06  4409.9   52.19  4449.9   48.31
  4459.9   47.98  4484.9   47.68  4509.9   48.51  4579.9   48.12  4809.9   46.61
  4924.9   44.73 4980.55      45 4983.05    43.5 4985.75   40.16 5017.35   43.97
 5019.45   47.15  5279.6   49.04  5364.6   50.31  5409.6   50.24  5429.6   49.18
  5464.6   49.62  5489.6    51.3  5499.6   51.09  5594.6   55.34  5725.2    55.4
  5962.8   56.81  6110.8   55.99  6321.8   56.99  6361.8   57.98  6724.9   58.01
#Mann= 8 , 1 , 0
 4249.90     0.1       0  4390.9    0.15       0 4980.55   0.045       0
 5019.45    0.15       0  5725.2     0.1       0  5962.8    0.15       0
  6110.8     0.1       0  6724.9     0.2       0
Bank Sta=4980.55,5019.45
Exp/Cntr=0.3,0.1

Type RM Length L Ch R = 1 ,16449.0,700,700,700
BEGIN DESCRIPTION:
Cross Section Bear Creek 21.0
END DESCRIPTION:
#Sta/Elev= 30
  3967.3    57.9  4132.3   56.59  4182.3   56.49  4391.4   51.44  4407.3   51.06
  4462.3   50.53  4487.3   49.16  4497.3   47.73  4582.3   47.68  4667.3    48.1
  4702.3   47.27  4797.3   46.53  4957.3   46.76  4977.2   47.08  4987.1   42.67
  4989.4    41.9  5003.1   40.15  5014.6   39.19  5017.3   42.85  5022.8   47.91
  5052.9   48.76  5357.9   50.35  5372.9   51.44  5472.9   51.92  5627.9   52.21
  5657.9   55.26  5662.9   55.58  5672.6   55.79  5687.9   56.12  6244.2   57.19
#Mann= 5 , 1 , 0
 3967.30     0.1       0  4391.4    0.15       0  4977.2   0.045       0
  5022.8    0.15       0  5672.6     0.1       0
Bank Sta=4977.20,5022.80
Exp/Cntr=0.3,0.1

Type RM Length L Ch R = 1 ,15749.0,707,707,707
BEGIN DESCRIPTION:
Cross Section Bear Creek 20.0
END DESCRIPTION:
#Sta/Elev= 30
  4092.6   56.41  4382.6   54.24  4417.6      53  4437.6   52.76  4447.6   52.16
  4462.6   51.93  4472.6   51.24  4488.1   51.12  4572.6   50.41  4602.6   50.74
  4782.6   50.06  4812.6   49.69  4917.6   49.48  4977.2   46.81  4987.1    42.4
  4989.4   41.63  5003.1   39.88  5014.6   38.92  5017.3   42.58  5022.8   47.64
  5197.3   48.06  5232.3   48.68  5502.3    50.8  5542.3   50.81  5687.3   51.76
  5777.3   55.77  5794.4   55.89  5907.3   57.11  6443.8   58.12  6443.9   58.12
#Mann= 7 , 1 , 0
 4092.60     0.2       0  4092.6     0.1       0  4488.1    0.15       0
  4977.2   0.045       0  5022.8    0.15       0  5794.4     0.1       0
  6443.8     0.2       0
Bank Sta=4977.20,5022.80
Exp/Cntr=0.3,0.1

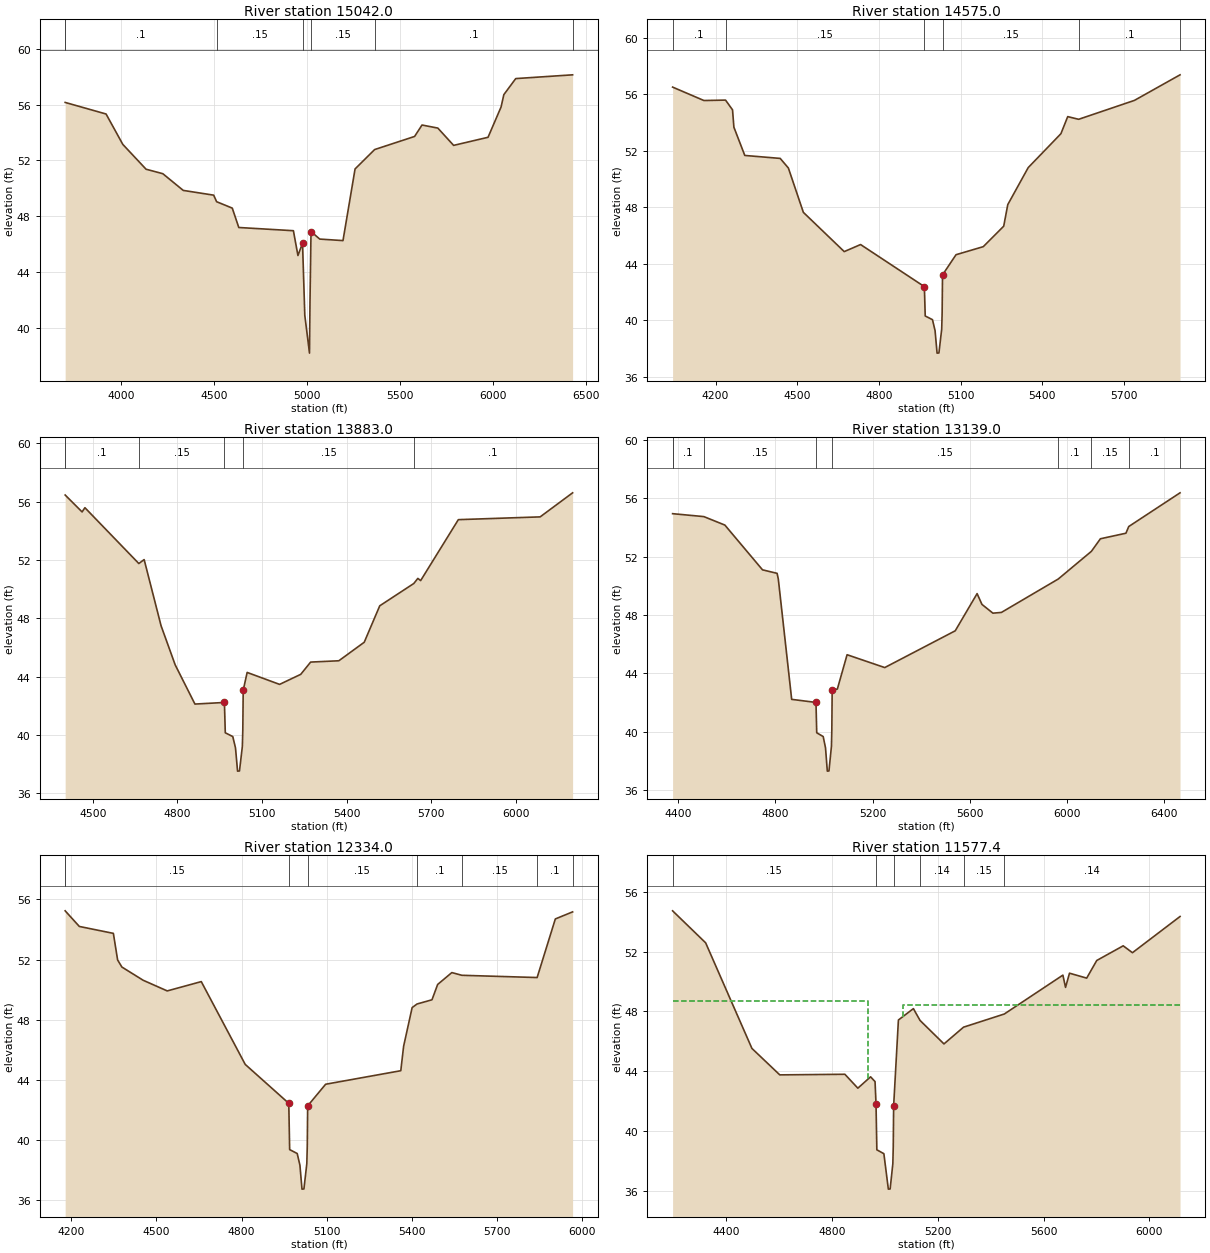
Type RM Length L Ch R = 1 ,15042.0,467,467,467
BEGIN DESCRIPTION:
Cross Section CCX_L67
Located At: CCX_L67 CTRL
END DESCRIPTION:
#Sta/Elev= 30
  3698.6   56.16  3918.6   55.33  4008.6   53.15  4133.6   51.37  4223.6   51.05
  4333.6   49.85  4497.2   49.51    4513   49.04  4597.2   48.58  4632.2   47.19
  4925.9   46.96  4950.3   45.18    4975   46.07  4987.2   40.89  5012.4   38.18
  5015.1   41.84  5020.6    46.9  5067.5   46.36  5192.5   46.25  5257.5   51.39
  5362.7   52.78  5577.5   53.72  5617.5   54.54  5702.5   54.32  5787.5   53.08
  5972.5   53.66  6042.5   55.83  6057.5   56.72  6121.4   57.87  6427.2   58.14
#Mann= 7 , 1 , 0
 3698.60     0.2       0  3698.6     0.1       0    4513    0.15       0
    4975   0.045       0  5020.6    0.15       0  5362.7     0.1       0
  6427.2     0.2       0
Bank Sta=4975.00,5020.60
Exp/Cntr=0.3,0.1

Type RM Length L Ch R = 1 ,14575.0,692,692,692
BEGIN DESCRIPTION:
Cross Section Bear Creek 19.0
END DESCRIPTION:
#Sta/Elev= 30
  4042.5    56.5  4157.5   55.55  4236.8   55.58  4262.5   54.89  4267.5   53.66
  4307.5   51.66  4437.5   51.45  4467.5   50.77  4522.5   47.63  4672.5   44.85
  4732.5   45.35  4966.7   42.37  4969.8   40.29  4996.4   40.03    5006   39.25
  5013.3   37.66  5020.1   37.67  5030.3   39.36  5031.9    40.5  5033.3    43.2
  5082.9   44.63  5182.9    45.2  5257.9   46.65  5272.9   48.18  5347.9    50.8
  5467.9    53.2  5492.9   54.41    5533   54.22  5737.9   55.56  5905.2   57.37
#Mann= 6 , 1 , 0
 4042.50     0.1       0  4236.8    0.15       0  4966.7   0.045       0
  5033.3    0.15       0    5533     0.1       0  5905.2     0.2       0
Bank Sta=4966.70,5033.30
Exp/Cntr=0.3,0.1

Type RM Length L Ch R = 1 ,13883.0,744,744,744
BEGIN DESCRIPTION:
Cross Section Bear Creek 18.0
END DESCRIPTION:
#Sta/Elev= 30
  4402.2   56.45  4462.2   55.29  4472.2   55.58  4663.3   51.75  4682.2   52.02
  4742.2   47.48  4792.2    44.8  4862.2   42.11  4966.7   42.22  4969.8   40.14
  4996.4   39.88    5006    39.1  5013.3   37.51  5020.1   37.52  5030.3   39.21
  5031.9   40.35  5033.3   43.05  5047.3   44.28  5162.3   43.46  5237.3   44.15
  5272.3   44.99  5372.3   45.08  5462.3   46.35  5517.3   48.85    5638   50.38
  5652.3   50.73  5662.3   50.58  5795.9   54.76  6085.9   54.95  6200.9    56.6
#Mann= 6 , 1 , 0
 4402.20     0.2       0  4402.2     0.1       0  4663.3    0.15       0
  4966.7   0.045       0  5033.3    0.15       0    5638     0.1       0
Bank Sta=4966.70,5033.30
Exp/Cntr=0.3,0.1

Type RM Length L Ch R = 1 ,13139.0,805,805,805
BEGIN DESCRIPTION:
Cross Section Bear Creek 17.0
END DESCRIPTION:
#Sta/Elev= 30
  4376.7   54.95  4505.2   54.75  4591.7   54.17  4746.7    51.1  4806.7   50.86
  4811.7   50.47  4866.7   42.22  4966.7   42.01  4969.8   39.93  4996.4   39.67
    5006   38.89  5013.3    37.3  5020.1   37.31  5030.3      39  5031.9   40.14
  5033.3   42.84  5054.7   42.93  5094.7   45.28  5249.7    44.4  5539.7   46.92
  5629.7   49.47  5649.7   48.73  5694.7   48.13  5729.7   48.18  5963.6   50.47
  6100.1   52.37  6137.1   53.23  6242.1   53.61  6253.8   54.07  6464.8   56.38
#Mann= 9 , 1 , 0
 4376.70     0.2       0  4376.7     0.1       0  4505.2    0.15       0
  4966.7   0.045       0  5033.3    0.15       0  5963.6     0.1       0
  6100.1    0.15       0  6253.8     0.1       0  6464.8     0.2       0
Bank Sta=4966.70,5033.30
Exp/Cntr=0.3,0.1

Type RM Length L Ch R = 1 ,12334.0,756.65,756.65,756.65
BEGIN DESCRIPTION:
Cross Section Bear Creek 16.0
END DESCRIPTION:
#Sta/Elev= 30
  4178.1   55.24  4228.1    54.2  4348.1   53.74  4363.1   51.97  4378.1    51.5
  4453.1   50.62  4538.1   49.91  4658.1   50.53  4813.1   45.02  4966.7   42.43
  4969.8   39.35  4996.4   39.09    5006   38.31  5013.3   36.72  5020.1   36.73
  5030.3   38.42  5031.9   39.56  5033.3   42.26  5096.7    43.7  5361.7    44.6
  5371.7   46.23  5401.7    48.8    5419   49.04  5471.7   49.32  5491.7   50.34
  5541.7   51.13  5577.1   50.95  5842.5    50.8  5906.7    54.7  5967.6   55.17
#Mann= 8 , 1 , 0
 4178.10     0.2       0  4178.1    0.15       0  4966.7   0.045       0
  5033.3    0.15       0    5419     0.1       0  5577.1    0.15       0
  5842.5     0.1       0  5967.6     0.2       0
Bank Sta=4966.70,5033.30
Exp/Cntr=0.5,0.3

Type RM Length L Ch R = 1 ,11577.4,40.7,40.7,40.7
BEGIN DESCRIPTION:
Upstream Section of Bridge/Culvert/Weir
END DESCRIPTION:
#Sta/Elev= 30
  4196.5   54.73  4321.5   52.59  4496.5   45.53  4601.9   43.76  4848.1    43.8
  4897.2   42.87  4945.3   43.63  4962.2   43.31  4965.9   41.83    4969   38.75
  4995.6   38.49  5012.5   36.12  5019.3   36.13  5029.5   37.82  5031.1   38.96
  5032.5   41.66  5050.6   47.43  5107.3   48.19  5132.4    47.4  5222.9   45.83
  5296.9   46.95  5451.1   47.83  5672.7   50.43  5682.7   49.61  5697.7   50.56
  5762.7   50.23  5800.8   51.41  5900.8   52.39  5935.8   51.93  6115.8   54.35
#Mann= 6 , 1 , 0
 4196.50    0.15       0  4965.9   0.045       0  5032.5    0.15       0
  5132.4    0.14       0  5296.9    0.15       0  5451.1    0.14       0
#XS Ineff= 2 , 0
       0    4935    48.7    5067       0    48.4
Bank Sta=4965.90,5032.50
Exp/Cntr=0.5,0.3