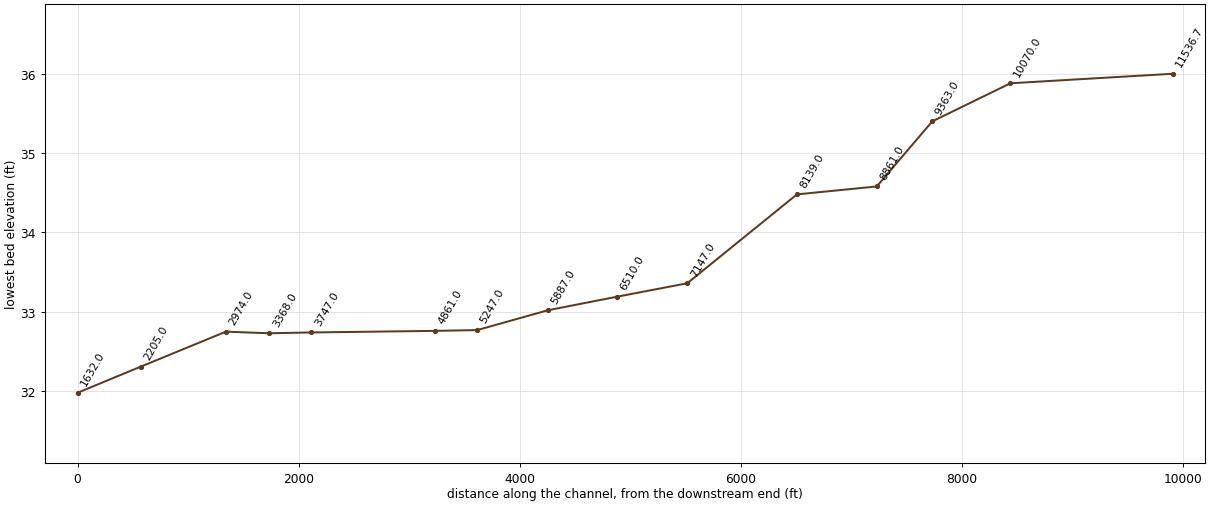
HEC-RAS study 04072003_Bear_Creek.prj: Bear Creek

--- 04072003_Bear_Creek.g01 (geometry) --- (continued)

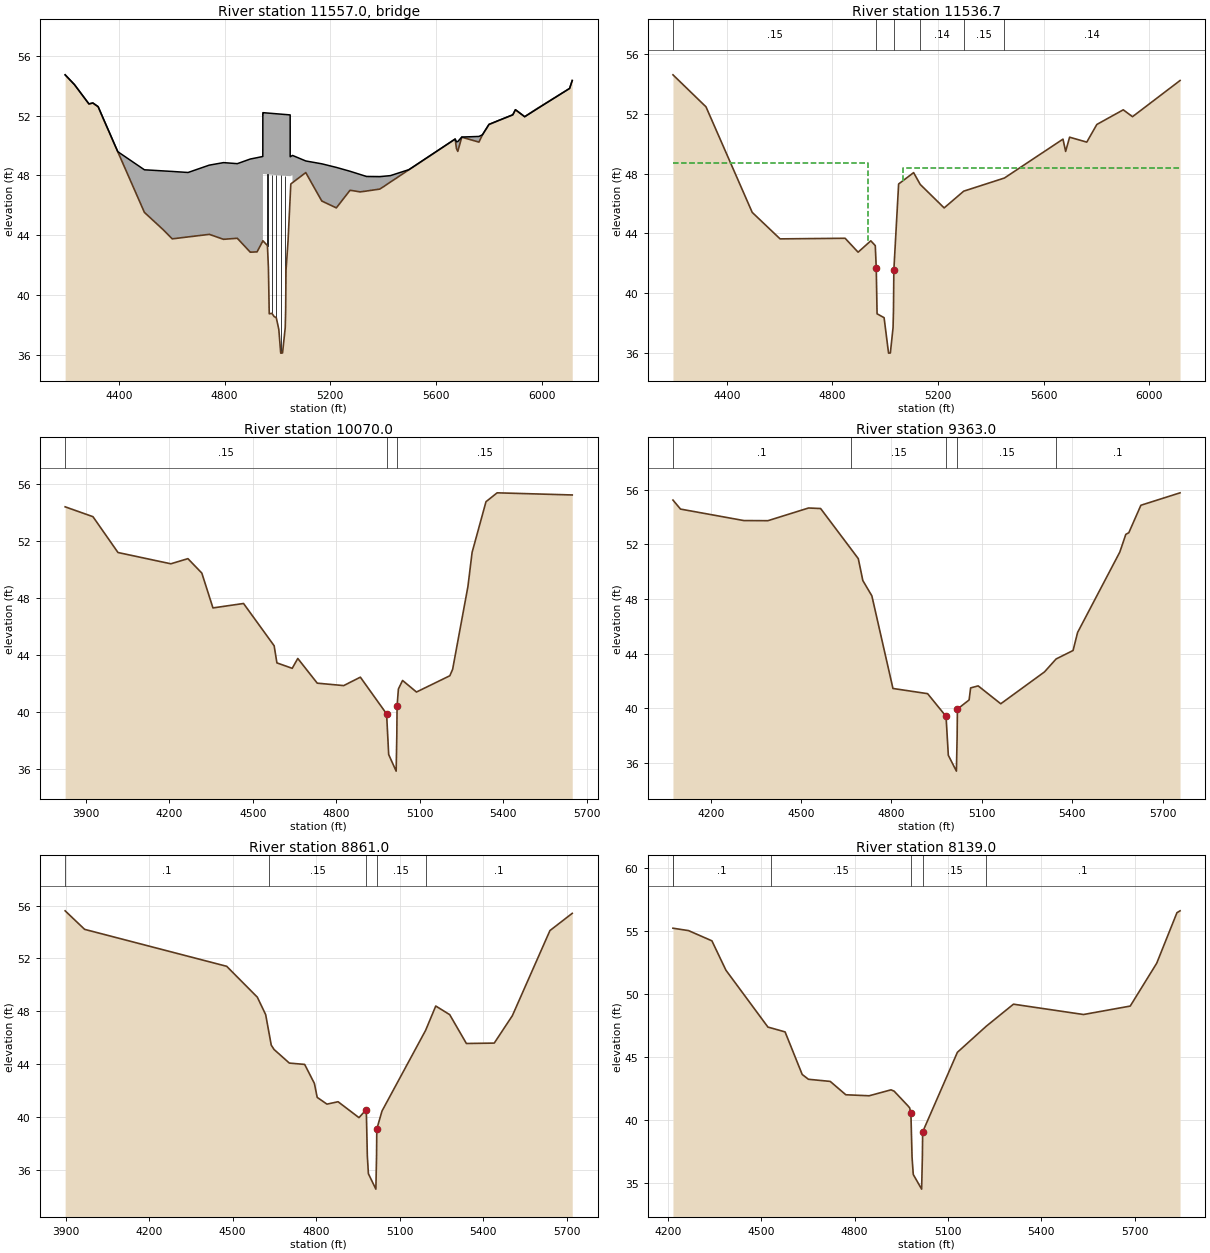
Type RM Length L Ch R = 3 ,11557.0,,,
BEGIN DESCRIPTION:
BEAR CREEK RD
Structure ID: L_BEACR1
END DESCRIPTION:
Bridge Culvert--1,0,-1,-1, 0
Deck Dist Width WeirC Skew NumUp NumDn MinLoCord MaxHiCord MaxSubmerge Is_Ogee
10,20.7,2.6,, 47, 47,,,0.95,0,1,1,,
  4196.5  4231.5  4286.5  4301.5  4321.5  4395.8  4496.5  4601.9  4661.7  4741.7
  4795.9  4848.1  4897.2  4922.9 4944.61 4944.72 4944.83  4944.9  4945.1  4945.2
  4945.3 5048.19  5048.3 5056.99  5057.1  5057.2  5107.3  5167.9  5222.9    5275
  5312.7  5337.6  5387.7  5427.6  5497.6  5672.7  5677.7  5682.7  5697.7  5762.7
  5775.8  5800.8  5890.8  5900.8  5935.8  6105.8  6115.8
   54.72   54.07   52.78   52.84   52.59   49.58   48.37   48.26   48.19   48.68
   48.85   48.78   49.09   49.18   49.26   52.06   52.06   52.19   52.19   52.19
   52.19   52.04   49.24   49.33   49.33   49.33   48.96   48.77   48.53   48.27
   48.06   47.92   47.91   47.98   48.38   50.43   50.24   50.26   50.56    50.6
   50.71   51.41   52.05   52.39   51.92   53.81   54.34
   54.72   54.07   52.77   52.83   52.58   49.57   45.52   43.75   43.88   44.05
   43.72   43.79   42.86   42.88    43.6   43.61   43.61   43.61   43.62   48.09
   48.09   47.94   47.94   48.03   47.51   47.51   48.18   46.28   45.82      47
   46.89   46.95   47.08   47.55   48.37   50.42   49.78    49.6   50.55   50.22
    50.7    51.4   52.04   52.38   51.92   53.81   54.34
  4196.5  4231.5  4286.5  4301.5  4321.5  4395.8  4496.5  4601.9  4661.7  4741.7
  4795.9  4848.1  4897.2  4922.9 4944.61 4944.72 4944.83  4944.9  4945.1  4945.2
  4945.3 5048.19  5048.3 5056.99  5057.1  5057.2  5107.3  5167.9  5222.9    5275
  5312.7  5337.6  5387.7  5427.6  5497.6  5672.7  5677.7  5682.7  5697.7  5762.7
  5775.8  5800.8  5890.8  5900.8  5935.8  6105.8  6115.8
   54.72   54.07   52.78   52.84   52.59   49.58   48.37   48.26   48.19   48.68
   48.85   48.78   49.09   49.18   49.26   52.06   52.06   52.19   52.19   52.19
   52.19   52.04   49.24   49.33   49.33   49.33   48.96   48.77   48.53   48.27
   48.06   47.92   47.91   47.98   48.38   50.43   50.24   50.26   50.56    50.6
   50.71   51.41   52.05   52.39   51.92   53.81   54.34
   54.61   53.96   52.66   52.72   52.47   49.46   45.41   43.64   43.77   43.94
   43.61   43.68   42.75   42.77   43.49    43.5    43.5    43.5   43.51   47.98
   47.98   47.83   47.83   47.92    47.4    47.4   48.07   46.17   45.71   46.89
   46.78   46.84   46.97   47.44   48.26   50.31   49.67   49.49   50.44   50.11
   50.59   51.29   51.93   52.27   51.81    53.7   54.23
Pier Skew, UpSta & Num, DnSta & Num=,4962.2, 2 ,4962.2, 2 , 0 , 0 , 0 ,,
       1       1
    42.1   49.06
       1       1
   41.99   48.95
Pier Skew, UpSta & Num, DnSta & Num=,4979.0, 2 ,4979.0, 2 , 0 , 0 , 0 ,,
       1       1
   37.76   49.04
       1       1
   37.65   48.93
Pier Skew, UpSta & Num, DnSta & Num=,4995.6, 2 ,4995.6, 2 , 0 , 0 , 0 ,,
       1       1
   37.44   49.02
       1       1
   37.33   48.91
Pier Skew, UpSta & Num, DnSta & Num=,5012.5, 2 ,5012.5, 2 , 0 , 0 , 0 ,,
       1       1
   35.11   48.99
       1       1
      35   48.88
Pier Skew, UpSta & Num, DnSta & Num=,5029.5, 2 ,5029.5, 2 , 0 , 0 , 0 ,,
       1       1
   36.73   48.97
       1       1
   36.62   48.86
Abutment Skew #Up #Dn=, 2 , 2
 5040.30 5057.19
   43.66   48.03
 5040.30 5057.19
   43.55   47.92
BR Coef= 1 , 1 , 0 ,1.25, 0 ,,,0.8,0,2,0,
Wspro=,,,, 1 ,,,, 0 ,,,, 0 ,,,,-1 ,-1 ,-1 , 0 , 0 , 0 , 0 , 0
BC Design=,, 0 ,, 0 ,,,,,,
BR U #Sta/Elev= 99
  4196.5   54.72  4231.5   54.07    4241   53.85    4251   53.61    4256   53.49
    4261   53.37  4286.5   52.77  4301.5   52.83    4311   52.71    4321   52.59
  4321.5   52.58    4341   51.77  4341.5   51.75    4351   51.37    4361   50.97
    4366   50.77    4381   50.16  4395.8   49.57  4496.5   45.52  4566.5   44.38
  4601.9   43.75  4661.7   43.88  4741.7   44.05  4742.4   44.05  4795.9   43.72
    4796   43.72    4848   43.79  4848.1   43.79  4896.1   42.88  4897.2   42.86
  4922.9   42.88 4944.61    43.6 4944.72   43.61 4944.83   43.61  4944.9   43.61
 4945.01   43.62  4945.1   43.62  4945.2   43.62  4945.3   43.62  4962.2    43.3
  4965.9   41.82    4969   38.74    4979   38.77  4987.4   38.56  4995.6   38.48
  5005.2    37.7  5012.5   36.11  5019.3   36.12  5029.5   37.81  5031.1   38.95
  5032.5   41.65  5040.2   43.62  5040.3   43.66 5048.08    46.5 5048.19   46.54
  5048.3   46.58  5050.6   47.42 5056.99   47.51  5057.1   47.51  5057.2   47.51
  5107.2   48.18  5107.3   48.18  5132.4   47.39  5167.9   46.28    5168   46.28
  5221.9   45.83  5222.9   45.82  5274.4   46.99    5275      47  5296.9   46.94
  5312.7   46.89  5337.6   46.95  5387.7   47.08  5392.6   47.14  5402.6   47.25
  5427.6   47.55  5451.1   47.82  5462.6   47.96  5497.6   48.37  5513.3   48.55
  5588.3   49.43  5663.3   50.31  5668.3   50.37  5672.7   50.42  5677.7   49.78
  5682.7    49.6  5697.7   50.55  5762.7   50.22  5775.8    50.7  5800.8    51.4
  5808.3   51.45  5838.3   51.67  5890.8   52.04  5900.8   52.38  5910.9   52.25
  5935.8   51.92  5980.8   52.44  6105.8   53.81  6115.8   54.34
BR U #Mann= 6
 4196.50    0.15  4965.9   0.045  5032.5    0.15  5132.4    0.14  5296.9    0.15
  5451.1    0.14
BR U Banks=4965.90,5032.50
BR D #Sta/Elev= 99
  4196.5   54.61  4231.5   53.96    4241   53.74    4251    53.5    4256   53.38
    4261   53.26  4286.5   52.66  4301.5   52.72    4311    52.6    4321   52.48
  4321.5   52.47    4341   51.66  4341.5   51.64    4351   51.26    4361   50.86
    4366   50.66    4381   50.05  4395.8   49.46  4496.5   45.41  4566.5   44.27
  4601.9   43.64  4661.7   43.77  4741.7   43.94  4742.4   43.94  4795.9   43.61
    4796   43.61    4848   43.68  4848.1   43.68  4896.1   42.77  4897.2   42.75
  4922.9   42.77 4944.61   43.49 4944.72    43.5 4944.83    43.5  4944.9    43.5
 4945.01   43.51  4945.1   43.51  4945.2   43.51  4945.3   43.51  4962.2   43.19
  4965.9   41.71    4969   38.63    4979   38.66  4987.4   38.45  4995.6   38.37
  5005.2   37.59  5012.5      36  5019.3   36.01  5029.5    37.7  5031.1   38.84
  5032.5   41.54  5040.2   43.51  5040.3   43.55 5048.08   46.39 5048.19   46.43
  5048.3   46.47  5050.6   47.31 5056.99    47.4  5057.1    47.4  5057.2    47.4
  5107.2   48.07  5107.3   48.07  5132.4   47.28  5167.9   46.17    5168   46.17
  5221.9   45.72  5222.9   45.71  5274.4   46.88    5275   46.89  5296.9   46.83
  5312.7   46.78  5337.6   46.84  5387.7   46.97  5392.6   47.03  5402.6   47.14
  5427.6   47.44  5451.1   47.71  5462.6   47.85  5497.6   48.26  5513.3   48.44
  5588.3   49.32  5663.3    50.2  5668.3   50.26  5672.7   50.31  5677.7   49.67
  5682.7   49.49  5697.7   50.44  5762.7   50.11  5775.8   50.59  5800.8   51.29
  5808.3   51.34  5838.3   51.56  5890.8   51.93  5900.8   52.27  5910.9   52.14
  5935.8   51.81  5980.8   52.33  6105.8    53.7  6115.8   54.23
BR D #Mann= 6
 4196.50    0.15  4965.9   0.045  5032.5    0.15  5132.4    0.14  5296.9    0.15
  5451.1    0.14
BR D Banks=4965.90,5032.50

Type RM Length L Ch R = 1 ,11536.7,1466.65,1466.65,1466.65
BEGIN DESCRIPTION:
Downstream Section of Bridge/Culvert/Weir
END DESCRIPTION:
#Sta/Elev= 30
  4196.5   54.61  4321.5   52.47  4496.5   45.41  4601.9   43.64  4848.1   43.68
  4897.2   42.75  4945.3   43.51  4962.2   43.19  4965.9   41.71    4969   38.63
  4995.6   38.37  5012.5      36  5019.3   36.01  5029.5    37.7  5031.1   38.84
  5032.5   41.54  5050.6   47.31  5107.3   48.07  5132.4   47.28  5222.9   45.71
  5296.9   46.83  5451.1   47.71  5672.7   50.31  5682.7   49.49  5697.7   50.44
  5762.7   50.11  5800.8   51.29  5900.8   52.27  5935.8   51.81  6115.8   54.23
#Mann= 6 , 1 , 0
 4196.50    0.15       0  4965.9   0.045       0  5032.5    0.15       0
  5132.4    0.14       0  5296.9    0.15       0  5451.1    0.14       0
#XS Ineff= 2 , 0
       0    4935    48.7    5067       0    48.4
Bank Sta=4965.90,5032.50
Exp/Cntr=0.5,0.3

Type RM Length L Ch R = 1 ,10070.0,707,707,707
BEGIN DESCRIPTION:
Cross Section Bear Creek 14.0
END DESCRIPTION:
#Sta/Elev= 30
  3825.5   54.39  3925.5    53.7  4015.5   51.19  4205.5    50.4  4266.9   50.76
  4316.9   49.75  4356.9   47.31  4466.9   47.62  4576.9   44.66  4586.9   43.46
  4641.9   43.08  4661.9   43.77  4731.9   42.04  4826.9   41.87  4886.9   42.46
 4981.15   39.89 4988.75   37.04 5015.55   35.88 5017.95    38.4 5018.85   40.42
  5023.6   41.63  5038.6   42.23  5088.6   41.42  5208.6   42.56  5218.6   43.01
  5273.6   48.81  5288.6    51.2  5338.6   54.75  5378.6   55.37  5648.6   55.22
#Mann= 3 , 1 , 0
 3825.50    0.15       0 4981.15   0.045       0 5018.85    0.15       0
Bank Sta=4981.15,5018.85
Exp/Cntr=0.3,0.1

Type RM Length L Ch R = 1 ,9363.0,502,502,502
BEGIN DESCRIPTION:
Cross Section Bear Creek 13.0
END DESCRIPTION:
#Sta/Elev= 30
    4075   55.24    4100   54.58    4310   53.74    4390   53.73    4525   54.66
    4565   54.62  4665.9   51.66    4690   50.95    4705   49.35    4735   48.23
    4805   41.45    4920   41.07 4981.15   39.41 4988.75   36.56 5015.55    35.4
 5017.95   37.92 5018.85   39.94  5057.7   40.61  5062.7   41.49  5087.7   41.64
  5162.7   40.33  5307.7   42.66  5346.4   43.61  5402.7   44.23  5417.7   45.55
  5557.7   51.43  5577.7   52.73  5587.7   52.85  5627.7   54.86  5757.7   55.77
#Mann= 5 , 1 , 0
 4075.00     0.1       0  4665.9    0.15       0 4981.15   0.045       0
 5018.85    0.15       0  5346.4     0.1       0
Bank Sta=4981.15,5018.85
Exp/Cntr=0.3,0.1

Type RM Length L Ch R = 1 ,8861.0,722,722,722
BEGIN DESCRIPTION:
Cross Section CCX_L66
Located At: CCX_L66 CNTRL
END DESCRIPTION:
#Sta/Elev= 30
  3898.5    55.6  3968.5    54.2  4478.5   51.41  4588.5   49.08  4618.5   47.76
  4631.7   46.24  4638.5   45.46  4648.5   45.13  4703.5    44.1  4758.5      44
  4793.5   42.56  4803.5   41.51  4838.5      41  4878.5   41.18  4953.5   39.98
  4979.8   40.59  4983.5   37.09  4987.4   35.74  5014.2   34.58  5016.6    37.1
  5017.5   39.12  5036.2   40.48  5192.7   46.57  5229.2   48.41  5279.2   47.76
  5339.2   45.58  5439.2   45.61  5504.2   47.68  5639.2   54.11  5719.2   55.41
#Mann= 5 , 1 , 0
 3898.50     0.1       0  4631.7    0.15       0  4979.8   0.045       0
  5017.5    0.15       0  5192.7     0.1       0
Bank Sta=4979.80,5017.50
Exp/Cntr=0.3,0.1

Type RM Length L Ch R = 1 ,8139.0,992,992,992
BEGIN DESCRIPTION:
Cross Section Bear Creek 12.0
END DESCRIPTION:
#Sta/Elev= 30
  4217.1   55.19  4267.1      55  4342.1   54.19  4387.1   51.86  4522.1   47.34
  4532.6   47.27  4577.1   46.96  4632.1   43.58  4652.1    43.2  4722.1   43.03
  4772.1   41.97  4847.1   41.89  4917.1   42.36  4927.1   42.26  4972.1   41.08
  4977.1   40.93 4981.15   40.49 4984.85   36.99 4988.75   35.64 5015.55   34.48
 5017.95      37 5018.85   39.02  5130.4   45.34  5222.6    47.4  5310.4   49.16
  5535.4   48.34  5685.4   49.01  5770.4   52.41  5835.4   56.42  5845.4   56.57
#Mann= 6 , 1 , 0
 4217.10     0.2       0  4217.1     0.1       0  4532.6    0.15       0
 4981.15   0.045       0 5018.85    0.15       0  5222.6     0.1       0
Bank Sta=4981.15,5018.85
Exp/Cntr=0.3,0.1

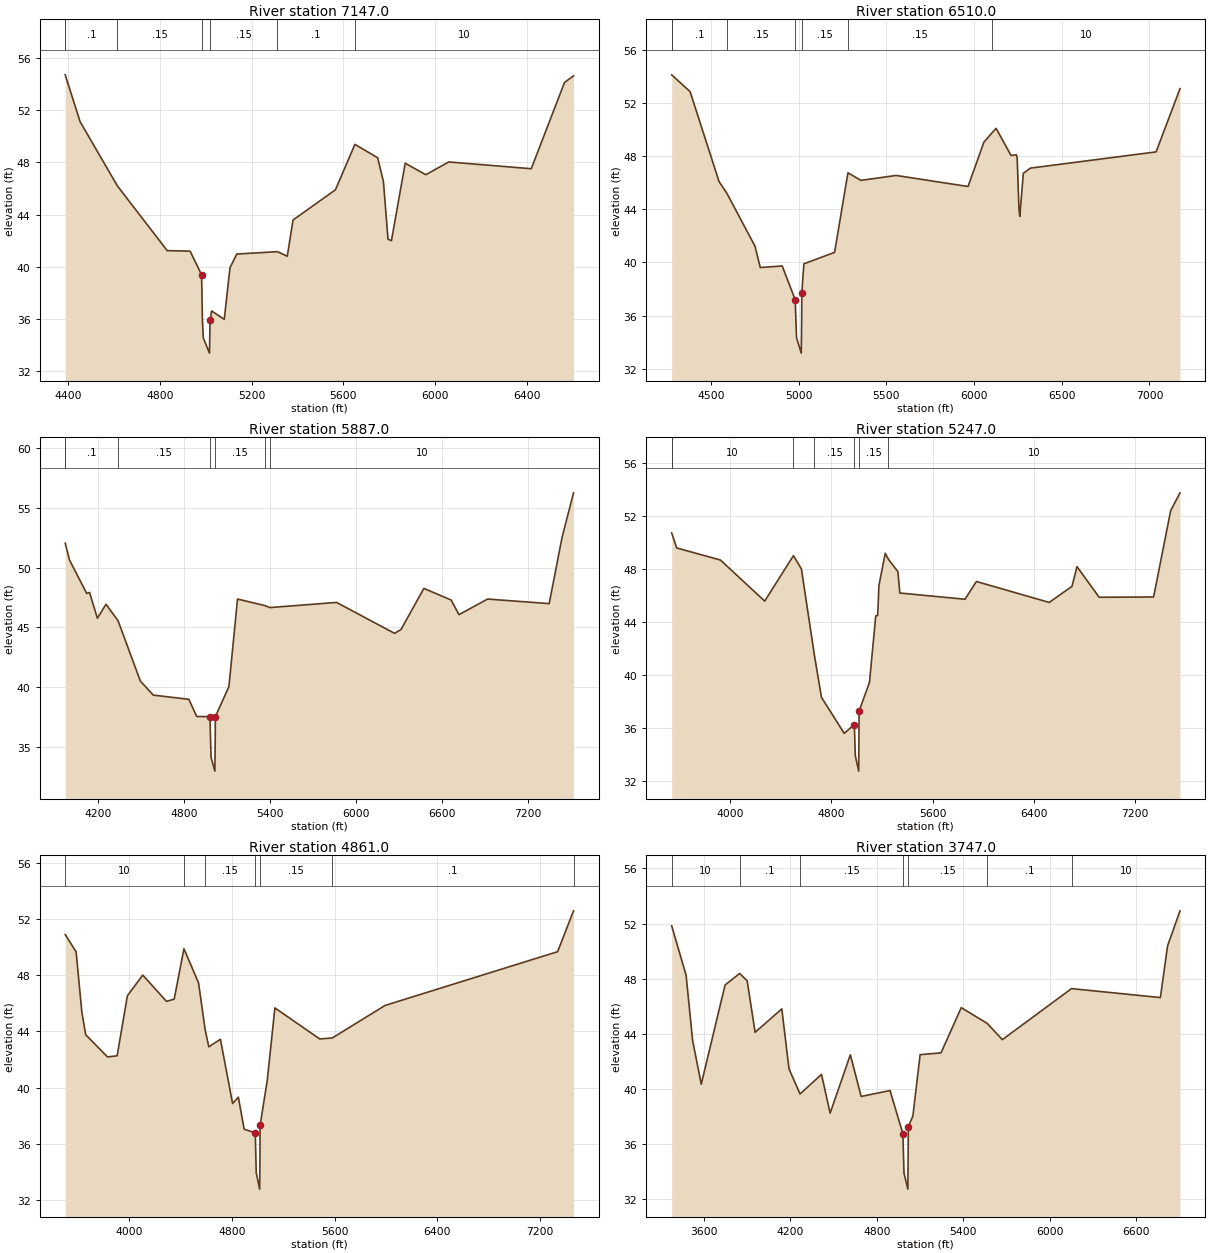
Type RM Length L Ch R = 1 ,7147.0,637,637,637
BEGIN DESCRIPTION:
Cross Section Bear Creek 11.0
END DESCRIPTION:
#Sta/Elev= 30
  4386.1   54.73  4451.1   51.13  4613.9    46.2  4831.1   41.23  4931.1   41.19
 4981.15   39.37 4984.85   35.87 4988.75   34.52 5015.55   33.36 5017.95   35.88
 5018.85    35.9    5025    36.6    5080   35.95    5105   39.92    5135   40.97
  5312.3   41.15    5355    40.8    5380   43.58    5565    45.9  5650.1   49.39
  5749.5   48.36  5774.5   46.53  5794.5    42.1  5809.5      42  5869.5   47.94
  5959.5   47.06  6059.5   48.04  6419.5   47.52  6564.5   54.14  6603.9   54.65
#Mann= 7 , 1 , 0
 4386.10     0.2       0  4386.1     0.1       0  4613.9    0.15       0
 4981.15   0.045       0 5018.85    0.15       0  5312.3     0.1       0
  5650.1      10       0
Bank Sta=4981.15,5018.85
Exp/Cntr=0.3,0.1

Type RM Length L Ch R = 1 ,6510.0,623,623,623
BEGIN DESCRIPTION:
Cross Section Bear Creek 10.0
END DESCRIPTION:
#Sta/Elev= 30
  4277.1    54.1  4382.1   52.84  4547.1   46.08  4591.8    45.2  4752.1   41.22
  4782.1   39.62  4907.1   39.74 4981.15    37.2 4988.75   34.35 5015.55   33.19
 5017.95   35.71 5018.85   37.73  5030.7    39.9  5205.7   40.76  5281.8   46.74
  5355.7   46.17  5556.3   46.54  5966.3   45.71  6056.3   49.03  6100.1    49.7
  6126.3   50.08  6211.3   48.04  6241.3   48.09  6246.3   47.86  6256.3   44.08
  6261.3   43.46  6281.3    46.7  6321.3   47.09  7038.1   48.31  7174.3   53.06
#Mann= 7 , 1 , 0
 4277.10     0.2       0  4277.1     0.1       0  4591.8    0.15       0
 4981.15   0.045       0 5018.85    0.15       0  5281.8    0.15       0
  6100.1      10       0
Bank Sta=4981.15,5018.85
Exp/Cntr=0.3,0.1

Type RM Length L Ch R = 1 ,5887.0,640,640,640
BEGIN DESCRIPTION:
Cross Section Bear Creek 9.0
END DESCRIPTION:
#Sta/Elev= 30
  3970.2   52.03  4000.2   50.63  4120.2   47.84  4140.2   47.92  4195.2   45.77
  4255.2   46.94  4339.4   45.56  4495.2   40.53  4585.2   39.36  4833.7   39.01
  4888.7   37.58 4981.15   37.56 4988.75   34.18 5015.55   33.02 5017.95   35.54
 5018.85   37.56  5113.7   40.07  5173.7   47.37  5363.7   46.83  5400.2   46.66
  5865.6   47.09  6270.6   44.51  6315.6   44.83  6475.6   48.26  6665.6   47.29
  6720.6   46.07  6920.6   47.37  7350.6   46.99  7440.6   52.52  7520.6   56.23
#Mann= 7 , 1 , 0
 3970.20     0.2       0  3970.2     0.1       0  4339.4    0.15       0
 4981.15   0.045       0 5018.85    0.15       0  5363.7     0.1       0
  5400.2      10       0
Bank Sta=4981.15,5018.85
Exp/Cntr=0.3,0.1

Type RM Length L Ch R = 1 ,5247.0,386,386,386
BEGIN DESCRIPTION:
Cross Section Bear Creek 8.0
END DESCRIPTION:
#Sta/Elev= 30
  3537.9   50.74  3577.9   49.61  3922.9    48.7  4272.9    45.6  4499.9   49.03
  4562.9   48.03    4666   41.49  4721.3   38.34  4901.3   35.62 4981.15   36.28
 4988.75   33.93 5015.55   32.77 5018.85   37.31  5100.4   39.46  5150.4   44.49
  5165.4   44.51  5175.4   46.78  5225.4   49.21  5249.9   48.76  5325.4   47.82
  5340.4   46.21  5855.4   45.74  5945.4   47.08  6520.4    45.5  6700.4   46.71
  6740.4    48.2  6915.4   45.89  7345.4   45.91  7480.4   52.43    7554   53.77
#Mann= 7 , 1 , 0
 3537.90     0.2       0  3537.9      10       0  4499.9     0.1       0
    4666    0.15       0 4981.15   0.045       0 5018.85    0.15       0
  5249.9      10       0
Bank Sta=4981.15,5018.85
Exp/Cntr=0.3,0.1

Type RM Length L Ch R = 1 ,4861.0,1114,1114,1114
BEGIN DESCRIPTION:
Cross Section Bear Creek 7.0
END DESCRIPTION:
#Sta/Elev= 30
    3499    50.9    3584   49.67    3629   45.36    3659   43.76    3829   42.18
    3904   42.26    3984   46.54    4104   48.01    4289   46.14    4349    46.3
    4425   49.89    4539   47.45  4590.4   44.11    4619    42.9  4709.4   43.44
  4804.4   38.86  4849.4   39.31  4894.4   37.03 4981.15   36.77 4988.75   33.92
 5015.55   32.76 5017.95   35.28 5018.85    37.3  5074.4   40.49  5134.4   45.67
  5484.4   43.46  5581.6   43.53  5994.3   45.85  7339.3   49.68  7463.2   52.59
#Mann= 7 , 1 , 0
 3499.00      10       0    4425     0.1       0  4590.4    0.15       0
 4981.15   0.045       0 5018.85    0.15       0  5581.6     0.1       0
  7463.2     0.2       0
Bank Sta=4981.15,5018.85
Exp/Cntr=0.3,0.1

Type RM Length L Ch R = 1 ,3747.0,379,379,379
BEGIN DESCRIPTION:
Cross Section Bear Creek 6.0
END DESCRIPTION:
#Sta/Elev= 30
  3378.8   51.83  3478.8   48.25  3523.8   43.53  3583.8   40.35  3748.8   47.54
  3849.8   48.38    3902   47.85    3957   44.11    4142   45.81    4192   41.46
  4268.4   39.64    4417   41.06    4477   38.25    4617   42.48    4692   39.46
    4892   39.89 4981.15   36.75 4988.75    33.9 5015.55   32.74 5018.85   37.28
  5050.5   38.04  5100.5   42.49  5245.5   42.62  5385.5    45.9  5565.2   44.76
  5670.5   43.58  6149.8   47.28  6765.5   46.63  6815.5   50.38  6901.5   52.92
#Mann= 7 , 1 , 0
 3378.80      10       0  3849.8     0.1       0  4268.4    0.15       0
 4981.15   0.045       0 5018.85    0.15       0  5565.2     0.1       0
  6149.8      10       0
Bank Sta=4981.15,5018.85
Exp/Cntr=0.3,0.1

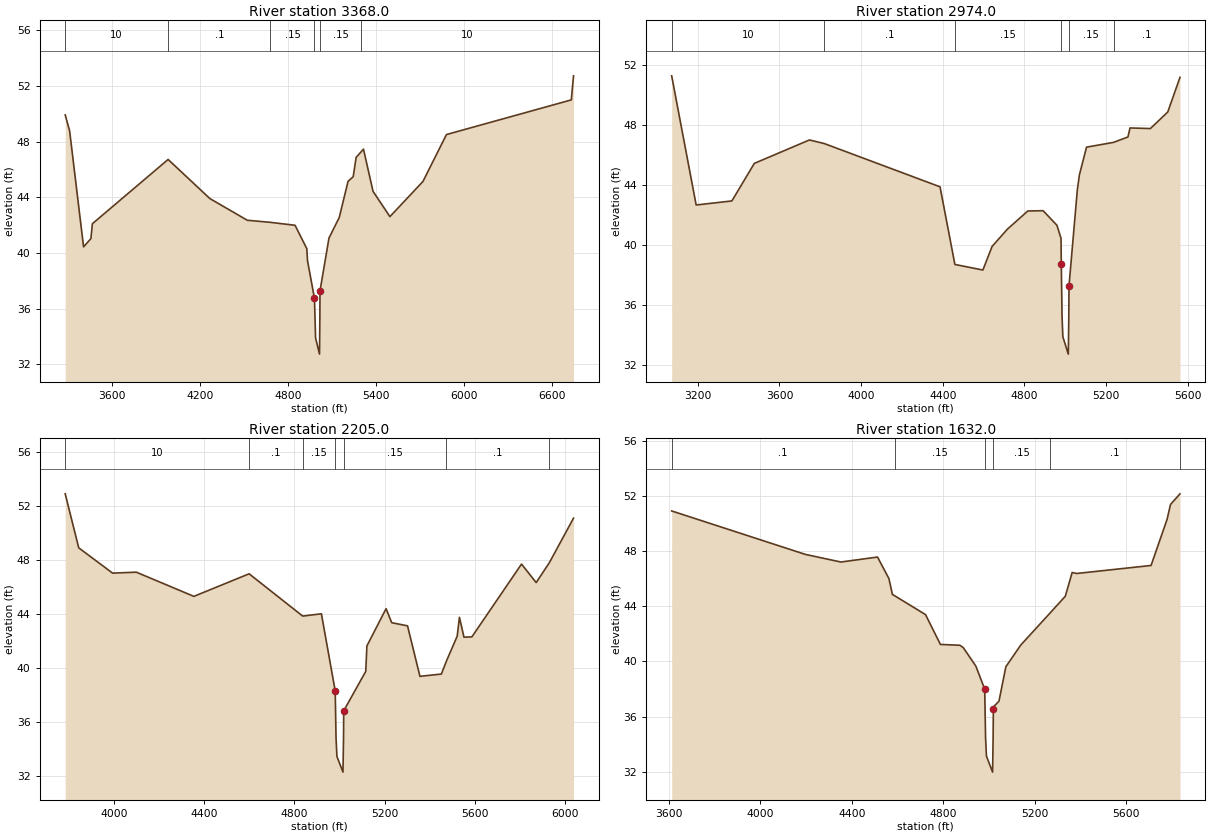
Type RM Length L Ch R = 1 ,3368.0,394,394,394
BEGIN DESCRIPTION:
Cross Section Bear Creek 5.0
END DESCRIPTION:
#Sta/Elev= 30
    3284   49.92    3314   48.78    3409   40.44    3459   41.03    3469    42.1
  3984.7   46.72    4269   43.91    4524   42.35  4681.5    42.2    4849   41.99
    4929   40.31    4934   39.44 4981.15   36.74 4988.75   33.89 5015.55   32.73
 5017.95   35.25 5018.85   37.27    5080   41.07    5150   42.55    5210   45.15
    5245   45.48    5265   46.87  5299.7   47.28    5315   47.46    5380   44.43
    5495   42.61    5720   45.14    5880   48.51    6730      51  6745.2   52.73
#Mann= 6 , 1 , 0
 3284.00      10       0  3984.7     0.1       0  4681.5    0.15       0
 4981.15   0.045       0 5018.85    0.15       0  5299.7      10       0
Bank Sta=4981.15,5018.85
Exp/Cntr=0.3,0.1

Type RM Length L Ch R = 1 ,2974.0,769,769,769
BEGIN DESCRIPTION:
Cross Section Bear Creek 4.0
END DESCRIPTION:
#Sta/Elev= 30
    3072   51.28    3192   42.68    3367   42.95    3477   45.45    3747   47.01
  3819.9   46.77    4387   43.89  4459.8   38.72    4597   38.35    4642   39.92
    4717   41.07    4817   42.28    4892    42.3  4959.8   41.33  4979.8   40.46
 4981.15   38.76 4984.85   35.26 4988.75   33.91 5015.55   32.75 5017.95   35.27
 5018.85   37.29  5059.8   43.69  5069.8   44.68  5104.8   46.53  5237.5   46.85
  5307.8   47.21  5317.8   47.81  5417.8   47.77  5502.8   48.87  5562.8   51.18
#Mann= 6 , 1 , 0
 3072.00      10       0  3819.9     0.1       0  4459.8    0.15       0
 4981.15   0.045       0 5018.85    0.15       0  5237.5     0.1       0
Bank Sta=4981.15,5018.85
Exp/Cntr=0.3,0.1

Type RM Length L Ch R = 1 ,2205.0,573,573,573
BEGIN DESCRIPTION:
Cross Section Bear Creek 3.0
END DESCRIPTION:
#Sta/Elev= 30
    3785   52.91    3845   48.91    3995   47.04    4100   47.11    4355   45.32
  4599.8   46.99  4837.1   43.86    4920   44.03 4981.15   38.32 4984.85   34.82
 4988.75   33.47 5015.55   32.31 5017.95   34.83 5018.85   36.85  5116.5   39.77
  5121.5   41.65  5206.5   44.41  5231.5   43.37  5301.5   43.14  5356.5    39.4
  5451.5   39.57    5474   40.54  5521.5   42.37  5531.5   43.77  5551.5    42.3
  5586.5   42.32  5806.5   47.71  5871.5   46.34  5929.7   47.81  6036.9   51.11
#Mann= 7 , 1 , 0
 3785.00      10       0  4599.8     0.1       0  4837.1    0.15       0
 4981.15   0.045       0 5018.85    0.15       0    5474     0.1       0
  5929.7     0.2       0
Bank Sta=4981.15,5018.85
Exp/Cntr=0.3,0.1

Type RM Length L Ch R = 1 ,1632.0,0,0,0
BEGIN DESCRIPTION:
Cross Section Bear Creek 2.0
END DESCRIPTION:
#Sta/Elev= 30
  3612.4    50.9  4197.4   47.75  4352.4    47.2  4512.4   47.56  4562.4      46
  4577.4   44.86    4587   44.76  4722.4   43.39  4787.4   41.23  4872.4   41.17
  4887.4      41  4942.4   39.66 4981.15   37.99 4984.85   34.49 4988.75   33.14
 5015.55   31.98 5017.95    34.5 5018.85   36.52  5022.4   36.76  5043.5   37.12
  5073.5   39.61  5138.5   41.18  5265.4   43.48  5333.5   44.72  5363.5   46.44
  5383.5   46.37  5708.5   46.95  5778.5   50.29  5793.5   51.37    5835   52.14
#Mann= 6 , 1 , 0
 3612.40     0.1       0    4587    0.15       0 4981.15   0.045       0
 5018.85    0.15       0  5265.4     0.1       0    5835     0.2       0
Bank Sta=4981.15,5018.85
Exp/Cntr=0.3,0.1

Chan Stop Cuts=-1