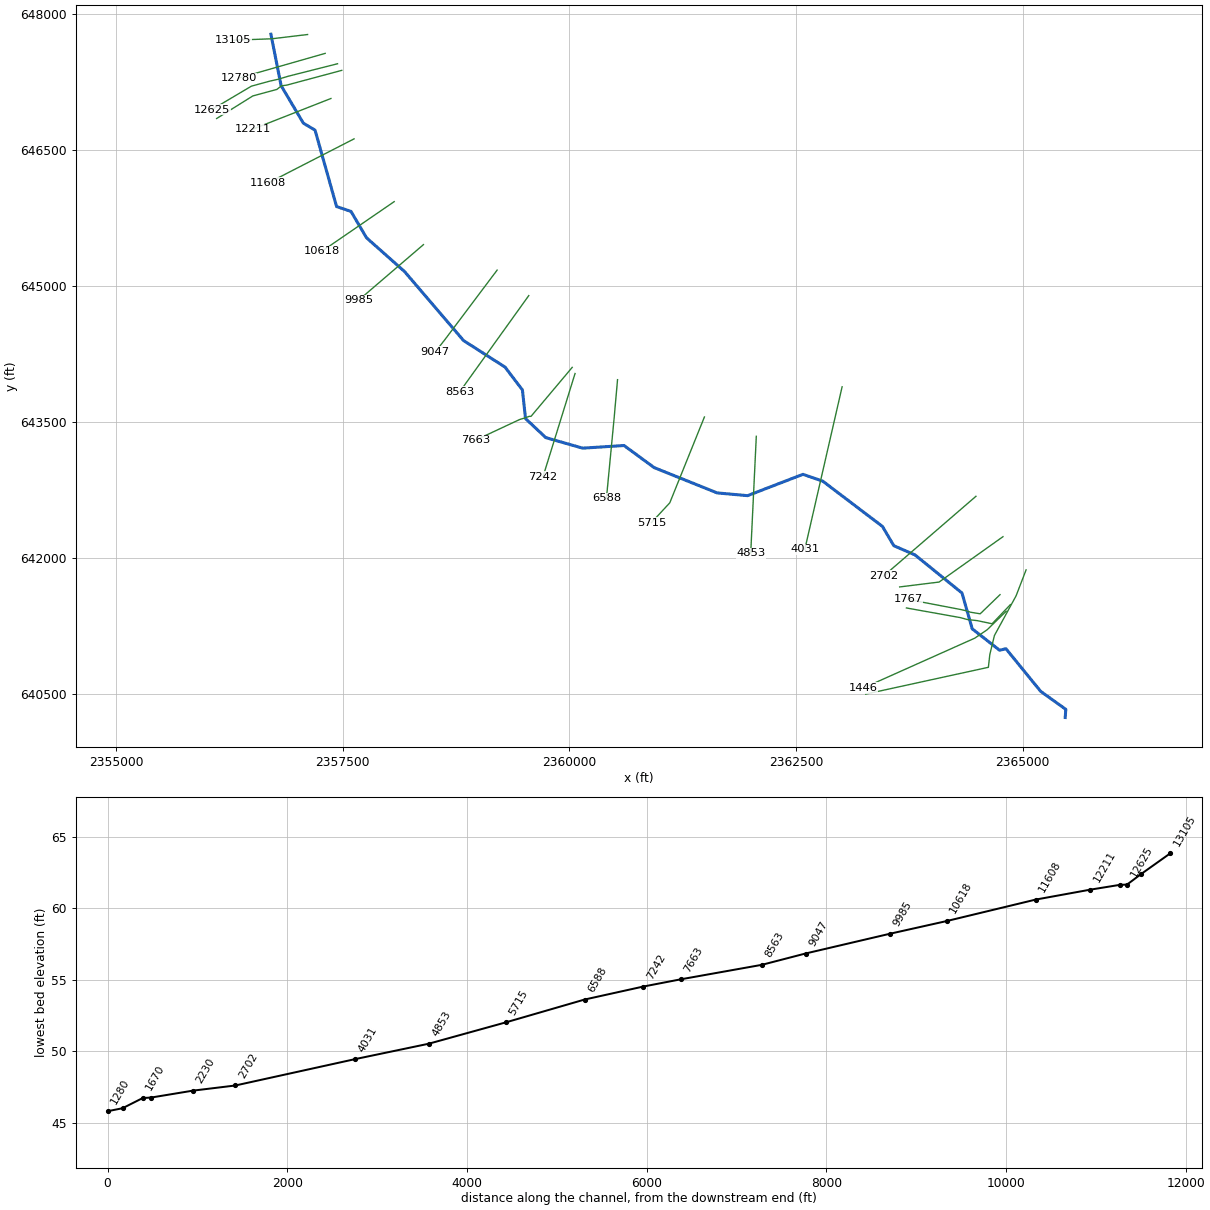
--- DTL_Appletree_Swamp.prj (project) ---

Proj Title=DTL_Appletree_Swamp_Main
Current Plan=p02
Default Exp/Contr=0.3,0.1
English Units
Geom File=g01
Flow File=f01
Flow File=f02
Plan File=p02
Plan File=p03
Y Axis Title=Elevation
X Axis Title(PF)=Main Channel Distance
X Axis Title(XS)=Station
BEGIN DESCRIPTION:
END DESCRIPTION:
DSS Export Rating Curves= 0
DSS Export Rating Curve Sorted= 0
DSS Export Volume Flow Curves= 0
DXF OffsetX= 0
DXF OffsetY= 0
DXF ScaleX= 1
DXF ScaleY= 10

--- DTL_Appletree_Swamp.p02 (plan) ---

Plan Title=DTL_Apppletree_Swamp_Main
Program Version=4.00
Short Identifier=Multi-Profile
Geom File=g01
Flow File=f01
Subcritical Flow
K Sum by GR= 0
Std Step Tol= 0.01
Critical Tol= 0.01
Num of Std Step Trials= 20
Max Error Tol= 0.3
Flow Tol Ratio= 0.001
Split Flow NTrial= 30
Split Flow Tol= 0.02
Split Flow Ratio= 0.02
Log Output Level= 0
Friction Slope Method= 1
Unsteady Friction Slope Method= 2
Unsteady Bridges Friction Slope Method= 1
Parabolic Critical Depth
Global Vel Dist= 0 , 0 , 0
Global Log Level= 0
CheckData=True
Encroach Param=-1 ,10,10, 2
Encroach River=Appletree Swamp
Encroach Reach=Main
Encroach Node=13105
       1   163.4  599.19
Encroach Node=12780
       1     460     565
Encroach Node=12625
       1  639.58  694.91
Encroach Node=12544
       1  657.73  713.07
Encroach Node=12211
       1     300     470
Encroach Node=11608
       1     295     470
Encroach Node=10618
       1     365     530
Encroach Node=9985
       1     360     520
Encroach Node=9047
       1     685     850
Encroach Node=8563
       1     670     820
Encroach Node=7663
       1     640     790
Encroach Node=7242
       1     650     800
Encroach Node=6588
       1     560     745
Encroach Node=5715
       1     575     785
Encroach Node=4853
       1     561     771
Encroach Node=4031
       1    1036    1246
Encroach Node=2702
       1     910    1110
Encroach Node=2230
       1     630     810
Encroach Node=1767
       1     340  478.69
Encroach Node=1670
       1     440     579
Encroach Node=1446
       1     300     450
Encroach Node=1280
       1     795     980
Encroach Node=1146
       1     839     971
Encroach Node=833
       1     825     955
Computation Interval=1HOUR
Output Interval=1HOUR
Run HTab= 0
Run UNet= 0
Run PostProcess= 0
Run WQNet= 0
UNET Theta= 1
UNET Theta Warmup= 1
UNET ZTol= 0.02
UNET ZSATol= 0.05
UNET MxIter= 20
UNET MaxInSteps= 0
UNET DtIC= 0
UNET DtMin= 0
UNET MaxCRTS= 20
UNET WFStab= 2
UNET SFStab= 1
UNET WFX= 1
UNET SFX= 1
UNET DSS MLevel= 4
UNET DZMax Abort= 100
UNET Convert EG Bridges= 0
UNET Use Existing IB Tables=-1
UNET Froude Reduction=False
UNET Froude Limit= 1
UNET Froude Power= 10
UNET Time Slicing=0,0, 5
Instantaneous Interval=1HOUR
Write IC File= 0
Echo Input=False
Echo Output=False
Write Detailed= 0
Detailed Automatic Start=False, 10
WQ ULTIMATE=-1
WQ Max Comp Step=1HOUR
WQ Output Interval=15MIN
WQ Output Selected Increments= 0
WQ Output face flow=0
WQ Output face velocity=0
WQ Output face area=0
WQ Output face dispersion=0
WQ Output cell volume=0
WQ Output cell surface area=0
WQ Output cell continuity=0
WQ Output face conc=0
WQ Output face dconc_dx=0
WQ Output face courant=0
WQ Output face peclet=0
WQ Output face adv mass=0
WQ Output face disp mass=0
WQ Output cell mass=0
WQ Output cell source sink temp=0
WQ Output cell source sink nsm=0
WQ Output MaxMinRange=-1
WQ Daily Max Min Mean=-1
WQ Daily Range=0
WQ Daily Time=0
WQ Create Restart=0
WQ Fixed Restart=0
WQ System Summary=False
Sorting and Armoring Iterations= 10
XS Update Threshold= 0.02
Hydraulics Update Threshold= 0.02
Energy Slope Method= 1
Volume Change Method= 0
XS Weighting Method= 0
Number of US Weighted Cross Sections= 1
Number of DS Weighted Cross Sections= 1
Upstream XS Weight=0.25
Main XS Weight=0.5
Downstream XS Weight=0.25
Number of DS XS's Weighted with US Boundary= 1
Upstream Boundary Weight= 1
Weight of XSs Associated with US Boundary= 0
Number of US XS's Weighted with DS Boundary= 1
Downstream Boundary Weight= 0.5
Weight of XSs Associated with DS Boundary= 0.5
Sediment Output Level= 4
Mass or Volume Output= 0
Output Increment Type= 1
Profile and TS Output Increment= 10
XS Output Flag= 0
XS Output Increment= 10
Disregard all LS=0
Disregard all Conn=0
Disregard all Breaches=0
Disregard all Pumps=0

--- DTL_Appletree_Swamp.p03 (plan) ---

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Plan Title=DTL_Apppletree_Swamp_Main_Future
Short Identifier=Future
Geom File=g01
Flow File=f02
Encroach Param=-1 ,0,0, 0

--- DTL_Appletree_Swamp.f01 (steady flow) ---

Flow Title=DTL_Appletree_Swamp_Main
Program Version=4.00
Number of Profiles= 6
Profile Names=100,FWay,10,25,50,500
River Rch & RM=Appletree Swamp,Main            ,13105
    1320    1320     580     840    1060    2080
River Rch & RM=Appletree Swamp,Main            ,12211
    1390    1390     610     880    1120    2180
River Rch & RM=Appletree Swamp,Main            ,10618
    1470    1470     650     930    1180    2290
River Rch & RM=Appletree Swamp,Main            ,7242
    1570    1570     700    1000    1270    2450
River Rch & RM=Appletree Swamp,Main            ,2702
    1620    1620     720    1030    1300    2520
Boundary for River Rch & Prof#=Appletree Swamp,Main            , 1
Up Type= 0
Dn Type= 3
Dn Slope=0.0022
Boundary for River Rch & Prof#=Appletree Swamp,Main            , 2
Up Type= 0
Dn Type= 3
Dn Slope=0.0022
Boundary for River Rch & Prof#=Appletree Swamp,Main            , 3
Up Type= 0
Dn Type= 3
Dn Slope=0.0022
Boundary for River Rch & Prof#=Appletree Swamp,Main            , 4
Up Type= 0
Dn Type= 3
Dn Slope=0.0022
Boundary for River Rch & Prof#=Appletree Swamp,Main            , 5
Up Type= 0
Dn Type= 3
Dn Slope=0.0022
Boundary for River Rch & Prof#=Appletree Swamp,Main            , 6
Up Type= 0
Dn Type= 3
Dn Slope=0.0022
DSS Import GetInterval= 0
DSS Import GetPeak= 0
DSS Import FillOption= 0

--- DTL_Appletree_Swamp.f02 (steady flow) ---

Flow Title=DTL_Appletree_Swamp_Main_Future
Program Version=4.00
Number of Profiles= 3
Profile Names=100-yr 10%,100-yr 20%,100-yr 35%
River Rch & RM=Appletree Swamp,Main            ,13105
    2260    2900    3540
River Rch & RM=Appletree Swamp,Main            ,12211
    2370    3040    3720
River Rch & RM=Appletree Swamp,Main            ,10618
    2500    3200    3910
River Rch & RM=Appletree Swamp,Main            ,7242
    2670    3420    4180
River Rch & RM=Appletree Swamp,Main            ,2702
    2740    3510    4290
Boundary for River Rch & Prof#=Appletree Swamp,Main            , 1
Up Type= 0
Dn Type= 3
Dn Slope=0.0022
Boundary for River Rch & Prof#=Appletree Swamp,Main            , 2
Up Type= 0
Dn Type= 3
Dn Slope=0.0022
Boundary for River Rch & Prof#=Appletree Swamp,Main            , 3
Up Type= 0
Dn Type= 3
Dn Slope=0.0022
DSS Import GetInterval= 0
DSS Import GetPeak= 0
DSS Import FillOption= 0

--- DTL_Appletree_Swamp.g01 (geometry) ---

Geom Title=DTL_Appletree_Swamp_Main
Program Version=4.00

River Reach=Appletree Swamp ,Main
Reach XY= 30
2356706.93328132647776.4551711832356819.51683508647209.092260063
2357065.18967843646794.8014219552357193.76146327646718.386115879
  2357431.497971 645875.391866492357590.39328994645822.022446379
 2357761.4180226645530.9165185092358181.09573521645158.543519154
2358832.44524881644396.8163412812359289.72414377644104.497472048
2359481.36887962643852.205667913 2359515.3312379643536.840912744
2359738.51244923643327.0020564052360146.06074819 643210.55968526
2360602.12670189643239.6702780722360934.47263618642995.869063497
2361629.48803891642716.8925493062361964.25985594642686.569015145
 2362575.5823044642921.8796401622362793.91175032642846.677275464
2363452.53891209642346.9454326632363577.47187275642134.680693582
2363811.56955643642032.7936188582364329.49551971641613.115906179
2364442.29906677641217.6970208732364744.57101686640981.506490842
2364814.67206614640998.1546335972365197.96153779640527.533383593
2365474.51216929640329.8239409182365468.16603045640239.639492095

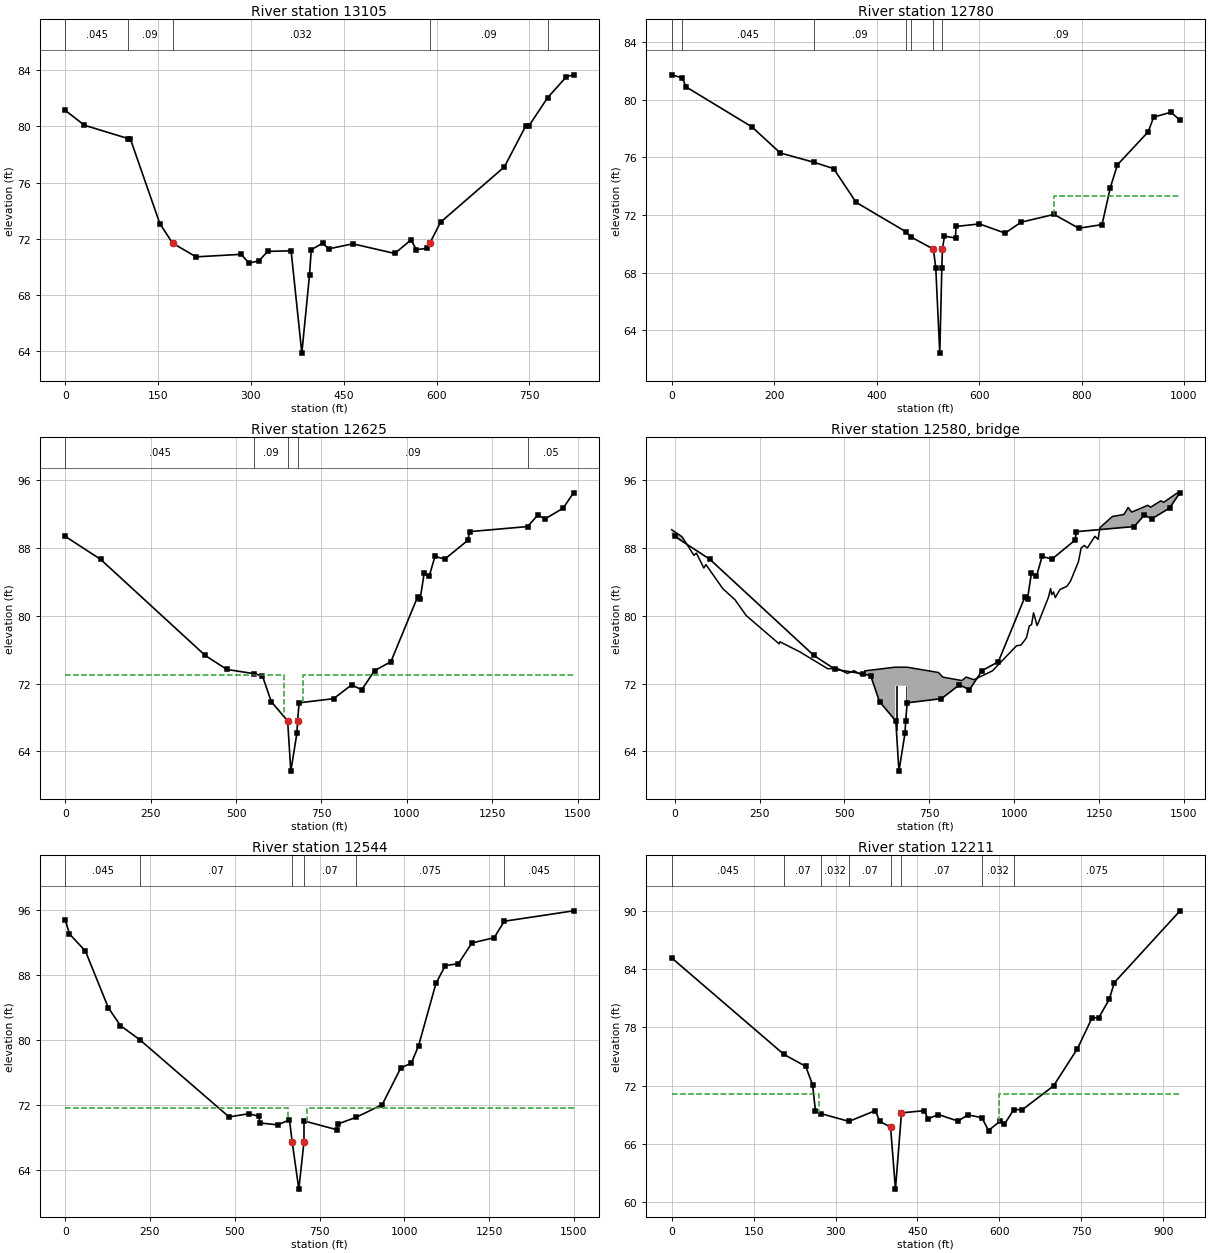
Type RM Length L Ch R = 1 ,13105   ,319.81,324.97,414.26
XS GIS Cut Line= 3
2357111.49999999647773.0000000152356716.75000003647725.750000015
2356293.25000003647710.250000015
#Sta/Elev= 30
       0   81.15   30.88   80.09  101.52   79.14  105.15   79.13  152.92   73.08
   173.4   71.69  211.42   70.71  284.31   70.89  296.96   70.26   313.1   70.43
  327.15    71.1  365.02   71.14  382.32   63.85  394.78   69.43  397.57   71.22
  415.85   71.68  425.88   71.28  464.65   71.64  532.61   70.95   558.7   71.92
  567.42   71.22  584.99   71.32  589.19   71.69  606.54   73.18   709.6   77.12
   743.8   80.01  749.27   80.04  779.46   82.05  809.95   83.55  821.35   83.68
#Mann= 5 ,-1 , 0
       0    .045       0  101.52     .09       0   173.4    .032       0
  589.19     .09       0  779.46    .085       0
Bank Sta=173.4,589.19
XS Rating Curve= 0 ,0
Exp/Cntr=0.3,0.1

Type RM Length L Ch R = 1 ,12780   ,148.79,155.02,150.61
XS GIS Cut Line= 2
2357305.71217971 647564.939757632356351.71917522647292.370327756
#Sta/Elev= 30
       0   81.74   20.44   81.53   28.57   80.89  156.31   78.13  211.95   76.31
  277.91   75.66  316.17   75.22  359.92   72.88  457.39   70.83  467.61   70.46
  510.77   69.63  515.44   68.34   523.3    62.4  527.32   68.34   528.5   69.63
  532.37   70.53  554.14    70.4  554.78    71.2  600.69   71.38  650.84   70.74
  682.02    71.5  746.42   72.04  794.39   71.08  839.98   71.33  856.21   73.91
  870.11   75.49  930.09   77.78  940.73    78.8  974.47   79.14  992.17   78.59
#Mann= 7 ,-1 , 0
       0     .08       0   20.44    .045       0  277.91     .09       0
  457.39    .032       0  467.61     .09       0  510.77     .05       0
   528.5     .09       0
#XS Ineff= 2 , 0
                          747.09           73.29
Permanent Ineff=
       F       F
Bank Sta=510.77,528.5
XS Rating Curve= 0 ,0
Exp/Cntr=0.5,0.3

Type RM Length L Ch R = 1 ,12625   ,85.44,80.68,104.68
BEGIN DESCRIPTION:
Survyed Section
END DESCRIPTION:
XS GIS Cut Line= 6
 2357441.7949395647450.4411680852356900.17000003647313.334500015
2356783.64470004647278.7199999992356693.90070002 647258.55310002
2356491.93693945647203.3033935732356056.37827285646945.232834756
#Sta/Elev= 30
       0   89.37  103.32   86.67  409.82   75.32  473.02   73.67  554.02   73.16
 577.366   72.91 603.236   69.87 651.206   67.59  660.47   61.67 678.248   66.13
 680.417   67.63 684.722   69.73  785.74   70.22  838.52   71.85  868.11   71.27
  905.56   73.53  953.41   74.58 1031.97   82.26 1039.35   82.03 1050.74   85.01
 1065.45   84.65 1082.33      87 1111.61    86.7 1178.85   88.91 1183.57   89.93
 1353.73   90.53 1383.73    91.9 1404.68   91.43 1457.58    92.7 1488.11   94.51
#Mann= 5 ,-1 , 0
       0    .045       0  554.02     .09       0 651.206     .05       0
 680.417     .09       0 1353.73     .05       0
#XS Ineff= 2 , 0
       0  639.58      73  694.91       0      73
Permanent Ineff=
       T       F
Bank Sta=651.206,680.417
XS Rating Curve= 0 ,0
Exp/Cntr=0.5,0.3

Type RM Length L Ch R = 3 ,12580   ,,,
BEGIN DESCRIPTION:
Appletree Road
END DESCRIPTION:
Bridge Culvert--1,0,-1,-1, 0
Deck Dist Width WeirC Skew NumUp NumDn MinLoCord MaxHiCord MaxSubmerge Is_Ogee
33.3,28.72,2.6,0, 60, 60, , , 0.98, 0, 0,0,,
   -9.08   21.19   56.56   63.71   85.72   91.77  141.64  177.71  210.41  307.42
  309.74  368.25   450.7   478.8  508.59  528.42   550.5  557.91 559.732 649.575
 684.913 776.864  790.08  845.81  858.39  881.37  935.84 1006.86 1020.13    1036
 1044.56 1051.17 1057.06 1067.41 1069.91  1100.7 1107.26 1110.43 1115.81  1121.1
 1134.86 1154.79  1165.8 1189.28 1197.33 1206.72 1215.35 1237.93  1246.9 1252.81
 1289.43 1323.53 1335.49 1346.36 1393.58    1402 1432.25 1440.46  1479.4  1488.5
   90.16   89.34   87.13    87.4   85.64   86.04    83.2   81.88   80.03   76.69
   76.93   75.75   73.75   73.79    73.2   73.52      73   73.11    73.5   73.94
   73.93   73.31   72.76   72.36   72.77   72.46    73.5   76.46   76.55   77.39
   78.81   78.96   80.35   78.86   79.05   82.16   83.22    82.5   82.81   82.15
   83.11   83.46   84.08   86.38      88    88.3      88   89.38   89.02   90.41
   91.72   91.96   92.77   92.24   93.04   92.82   93.57   93.39   94.47   94.32
                                                                                
                                                                           71.74
   71.73
                                                                                
                                                                                
                                                                                
    9.08   39.35   74.72   81.87  103.88  109.93   159.8  195.87  228.57  325.58
   327.9  386.41  468.86  496.96  526.75  546.58  568.66  576.07 577.892 667.735
 703.073 795.024  808.24  863.97  876.55  899.53     954 1025.02 1038.29 1054.16
 1062.72 1069.33 1075.22 1085.57 1088.07 1118.86 1125.42 1128.59 1133.97 1139.26
 1153.02 1172.95 1183.96 1207.44 1215.49 1224.88 1233.51 1256.09 1265.06 1270.97
 1307.59 1341.69 1353.65 1364.52 1411.74 1420.16 1450.41 1458.62 1497.56 1506.66
   90.16   89.34   87.13    87.4   85.64   86.04    83.2   81.88   80.03   76.69
   76.93   75.75   73.75   73.79    73.2   73.52      73   73.11    73.5   73.94
   73.93   73.31   72.76   72.36   72.77   72.46    73.5   76.46   76.55   77.39
   78.81   78.96   80.35   78.86   79.05   82.16   83.22    82.5   82.81   82.15
   83.11   83.46   84.08   86.38      88    88.3      88   89.38   89.02   90.41
   91.72   91.96   92.77   92.24   93.04   92.82   93.57   93.39   94.47   94.32
                                                                                
                                                                           71.74
   71.73
                                                                                
                                                                                
                                                                                
Pier Skew, UpSta & Num, DnSta & Num=  ,652.846, 2 ,671.01, 2 , 0 , 0 , 0 ,,
       1       1
   61.67   71.74
       1       1
   61.67   71.74
Pier Skew, UpSta & Num, DnSta & Num=  ,681.29, 2 ,699.45, 2 , 0 , 0 , 0 ,,
       1       1
   61.67   71.74
       1       1
   61.67   71.74
BR Coef=-1 , 1 , 0 ,1.25, 0 ,,,0.8,0,2,0,
WSPro=,,,, 1 ,,,, 0 ,,,, 0 ,,,,-1 ,-1 ,-1 , 0 , 0 , 0 , 0 , 0
BC Design=,, 0 ,, 0 ,,,,,,
BC Use User HTab Curves=0
BC User HTab FreeFlow(D)= 0

Type RM Length L Ch R = 1 ,12544   ,333.29,333.08,314.87
BEGIN DESCRIPTION:
Survyed Section
END DESCRIPTION:
XS GIS Cut Line= 6
2357488.66993952647377.524501413    2356883.5098647215.321899995
2356822.84650001647207.0674999952356773.43730001647167.731400013
 2356507.2309266647095.288884342 2356108.4616062646846.274501428
#Sta/Elev= 30
       0   94.81   12.39   93.04   59.46   90.94  127.25   83.95  162.68   81.77
  220.32   80.01  483.13   70.53  542.41   70.93  570.42   70.61  574.85   69.78
 626.498   69.56  661.31   70.16  669.17   67.47 688.822   61.65     704  67.468
  704.07   70.04 802.352   68.94  803.11   69.65  857.61   70.48  934.68   72.04
  989.29   76.55 1020.58   77.15    1042    79.3 1093.17   86.96 1120.69   89.15
 1159.22   89.37 1199.22   91.93 1264.67   92.57 1294.65    94.6 1498.79   95.88
#Mann= 6 ,-1 , 0
       0    .045       0  220.32     .07       0  669.17     .05       0
     704     .07       0  857.61    .075       0 1294.65    .045       0
#XS Ineff= 2 , 0
       0  657.73   71.66  713.07       0   71.66
Permanent Ineff=
       F       F
Bank Sta=669.17,704
XS Rating Curve= 0 ,0
Exp/Cntr=0.5,0.3

Type RM Length L Ch R = 1 ,12211   ,563.1,603.24,563.63
XS GIS Cut Line= 2
2357369.37125769647067.4056681542356502.98530991646727.349183649
#Sta/Elev= 30
       0   85.17   205.6   75.21  245.43   73.98  257.94   72.08  263.23   69.41
   272.8   69.11  324.64    68.3  372.89   69.41  381.07   68.29  400.77   67.71
  409.74   61.31  420.78   69.18  462.76   69.41  469.11   68.55  488.21   69.01
  524.46   68.33  542.36   68.98  567.93   68.68  580.13   67.36  601.49   68.33
  609.13      68  626.29   69.51  642.32   69.52  699.12   71.96   742.9    75.8
  769.84      79   781.8   78.99  801.15   80.89  810.44   82.62  930.73   90.03
#Mann= 8 ,-1 , 0
       0    .045       0   205.6     .07       0   272.8    .032       0
  324.64     .07       0  400.77     .05       0  420.78     .07       0
  567.93    .032       0  626.29    .075       0
#XS Ineff= 2 , 0
       0     270   71.12     600       0   71.12
Permanent Ineff=
       F       F
Bank Sta=400.77,420.78
XS Rating Curve= 0 ,0
Exp/Cntr=0.3,0.1

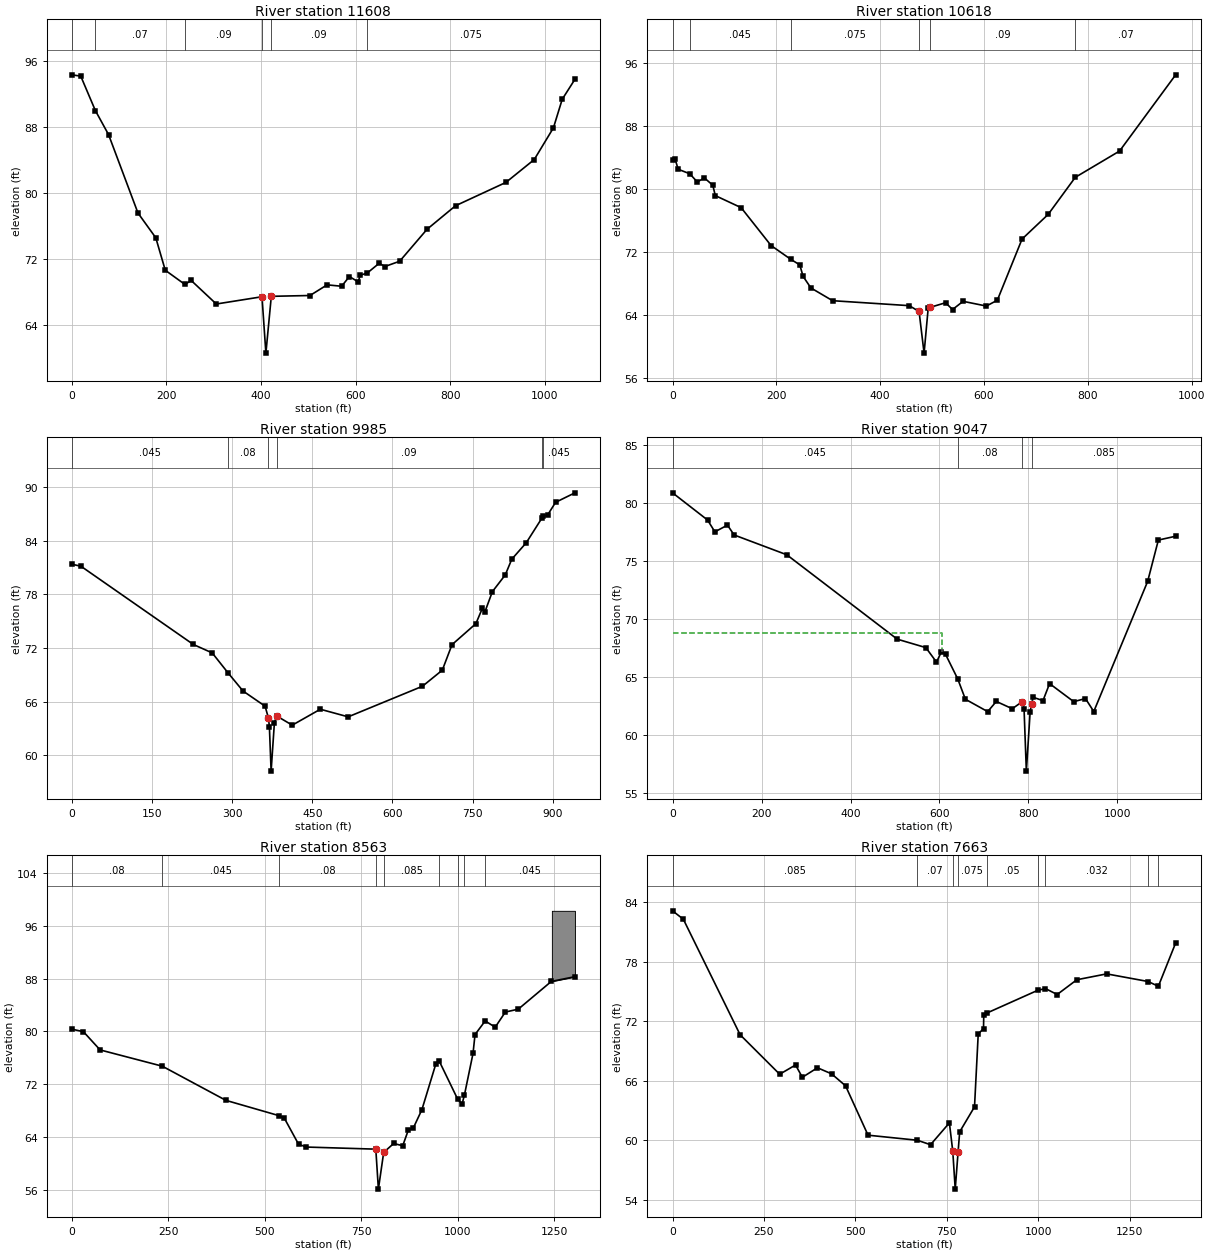
Type RM Length L Ch R = 1 ,11608   ,906.6801,989.89,910.88
XS GIS Cut Line= 2
2357624.23808315646622.0396950542356677.64037329646136.063192219
#Sta/Elev= 30
       0   94.33   18.91   94.17    49.8      90   77.77   87.08  139.91   77.59
   177.6   74.59  197.62   70.66   239.2   68.94  252.47   69.42  305.56   66.57
  402.21   67.45  410.45   60.62   421.9    67.5  503.73    67.6  539.95   68.89
  570.65   68.72  587.08    69.9  605.57   69.25  610.06   70.07  624.39    70.3
  650.16   71.51  662.08   71.11   693.4   71.75  751.26   75.62  811.47   78.47
  918.14    81.3  978.05   84.07 1018.59   87.91  1037.2   91.37 1064.06   93.79
#Mann= 6 ,-1 , 0
       0     .09       0    49.8     .07       0   239.2     .09       0
  402.21     .05       0   421.9     .09       0  624.39    .075       0
Bank Sta=402.21,421.9
XS Rating Curve= 0 ,0
Exp/Cntr=0.3,0.1

Type RM Length L Ch R = 1 ,10618   ,621.6,633.17,635.13
XS GIS Cut Line= 2
 2358066.7949395645929.6078347562357267.67923601645381.214906842
#Sta/Elev= 30
       0   83.61    5.16   83.73   10.74   82.48   33.24    81.9   47.64   80.86
   61.33   81.38   77.57   80.44   82.34   79.13  132.08    77.6  189.75   72.79
  227.66   71.04  245.06   70.33  251.55   68.86  266.54    67.4  308.32   65.78
  456.04   65.15   474.9   64.41  484.56   59.12  492.51   64.86  495.54   64.92
  525.93   65.52  539.42   64.66  559.67    65.7  604.51    65.1  625.66   65.84
  673.31   73.61  723.58   76.74  775.83   81.45  861.17   84.79  969.19   94.47
#Mann= 6 ,-1 , 0
       0    .075       0   33.24    .045       0  227.66    .075       0
   474.9     .05       0  495.54     .09       0  775.83     .07       0
Bank Sta=474.9,495.54
XS Rating Curve= 0 ,0
Exp/Cntr=0.3,0.1

Type RM Length L Ch R = 1 ,9985    ,916,937.83,945.36
XS GIS Cut Line= 2
2358389.71160619645455.6495014132357674.94867475644842.943106428
#Sta/Elev= 30
       0   81.37   17.13   81.14  227.44   72.39  262.69   71.45  292.13   69.23
  320.32   67.19  361.68   65.49  367.82   64.18   369.7   63.21  372.92   58.23
  379.05   63.62  383.06   64.41  412.46   63.37  464.99   65.15  517.12    64.3
   656.1   67.72  693.26   69.52   711.4   72.37  756.08   74.72  768.17   76.43
  772.55   75.97  786.94    78.3  811.06   80.17  823.28   81.93   850.4   83.77
  879.49   86.51  881.93   86.72  890.61    86.9  905.26   88.29  941.43   89.35
#Mann= 6 ,-1 , 0
       0    .045       0  292.13     .08       0  367.82     .05       0
  383.06     .09       0  879.49     .09       0  881.93    .045       0
Bank Sta=367.82,383.06
XS Rating Curve= 0 ,0
Exp/Cntr=0.3,0.1

Type RM Length L Ch R = 1 ,9047    ,498.58,484.71,478.79
XS GIS Cut Line= 3
2359202.21160619645174.3995014282358624.18756129 644405.03601858
2358520.12520142644272.448950931
#Sta/Elev= 30
       0   80.89   78.72   78.54   95.15   77.52  123.43    78.1  138.41   77.25
  256.74   75.54  504.96   68.25  569.35   67.52  593.24   66.27  604.35   67.15
  613.62   66.94  641.08   64.81  658.23   63.06  708.36   61.99  727.72   62.87
  763.55   62.24  786.06   62.85   790.1   62.21  795.25   56.85  803.81   61.99
  807.23   62.66  810.39   63.23  832.66   62.94  847.46   64.41  901.79   62.85
  928.07   63.12  946.82      62  1067.9   73.24 1091.98   76.81 1130.85   77.14
#Mann= 4 ,-1 , 0
       0    .045       0  641.08     .08       0  786.06     .05       0
  807.23    .085       0
#XS Ineff= 2 , 0
          606.45    68.8
Permanent Ineff=
       F       F
Bank Sta=786.06,807.23
XS Rating Curve= 0 ,0
Exp/Cntr=0.3,0.1

Type RM Length L Ch R = 1 ,8563    ,897.39,899.6,858.66
XS GIS Cut Line= 2
2359551.16993949644893.1495014132358790.60520625643833.580007508
#Sta/Elev= 30
       0   80.35   30.02   79.97   73.31    77.2  234.51   74.73  399.49   69.54
  537.49   67.21  551.33   66.79   587.9   62.87  608.08   62.45  788.05   62.13
  794.77   56.06  808.49   61.64  834.39   62.99  857.85   62.65  872.19      65
  885.44   65.36  907.64   68.14  943.83    75.1  952.78   75.47 1000.38   69.71
 1011.64   68.96 1017.99    70.4 1040.14   76.68 1045.26   79.53  1071.6    81.6
 1097.58   80.65 1123.87   82.95 1157.43   83.39 1243.04    87.6 1304.28   88.32
#Mann= 9 ,-1 , 0
       0     .08       0  234.51    .045       0  537.49     .08       0
  788.05     .05       0  808.49    .085       0  952.78    .075       0
 1000.38       0       0 1017.99    .075       0  1071.6    .045       0
#Block Obstruct= 1 ,-1
 1244.52 1304.28  98.323
Bank Sta=788.05,808.49
XS Rating Curve= 0 ,0
Exp/Cntr=0.3,0.1

Type RM Length L Ch R = 1 ,7663    ,358.31,420.76,472.38
BEGIN DESCRIPTION:
Survyed Section
END DESCRIPTION:
XS GIS Cut Line= 6
 2360030.3366062644101.4828347562359576.20800003643561.436400011
2359556.04050004643561.430800006    2359516.3484643546.269800022
2359451.68440002643526.8772000222358962.54133557643298.184671566
#Sta/Elev= 30
       0   83.12   29.53   82.27  184.82   70.62  293.02   66.64  336.43   67.57
  355.02   66.33  396.34   67.29  434.93   66.68  473.19   65.47  534.71   60.49
  669.59   59.98 705.578   59.53 757.202   61.73 766.493   58.85  773.16   55.05
  781.03   58.82 785.367   60.83  825.92   63.35 836.052   70.69 850.528   71.25
  851.24   72.63  859.07    72.8  998.61    75.1  1019.8   75.28 1051.98   74.68
 1105.84   76.17  1187.4   76.76 1300.79   75.99 1328.72   75.51 1376.06   79.88
#Mann= 9 ,-1 , 0
       0    .085       0  669.59     .07       0 766.493     .05       0
  781.03    .075       0  859.07     .05       0  998.61    .075       0
  1019.8    .032       0 1300.79    .075       0 1328.72    .045       0
Bank Sta=766.493,781.03
XS Rating Curve= 0 ,0
Exp/Cntr=0.3,0.1

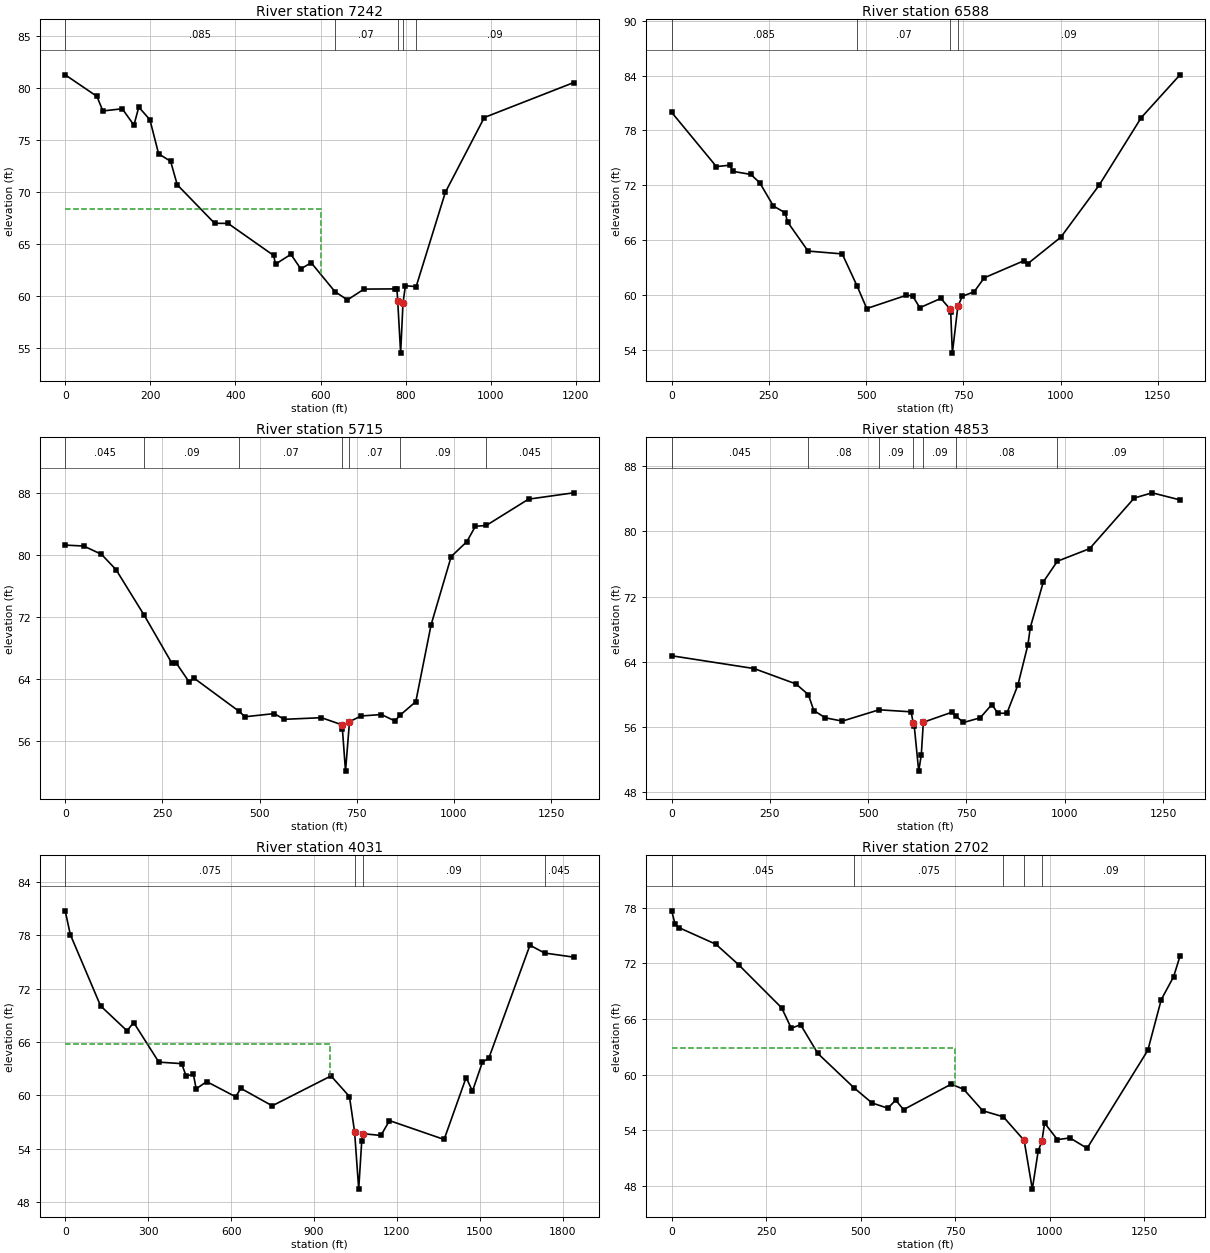
Type RM Length L Ch R = 1 ,7242    ,631.62,654.16,677.7
XS GIS Cut Line= 2
2360061.58660622644033.7745014132359707.41993952642893.149501428
#Sta/Elev= 30
       0   81.27   74.55    79.2   88.45    77.8  134.07   78.01   161.5   76.43
   172.8   78.17     199   76.96  219.44   73.68  247.66   72.97  263.21   70.71
  351.04   67.01  382.55      67  489.78   63.92  494.13   63.09  530.32   64.03
  553.49   62.63  577.99   63.22  633.72   60.45  663.08   59.65  702.13   60.69
   775.3   60.71  779.43 60.6584  781.19   59.59  788.12   54.54  793.66   59.37
  799.37   61.01  824.58   60.93  893.29      70  984.68   77.17 1194.34   80.52
#Mann= 5 ,-1 , 0
       0    .085       0  633.72     .07       0  781.19     .05       0
  793.66     .07       0  824.58     .09       0
#XS Ineff= 2 , 0
       0  600.72   68.36               0
Permanent Ineff=
       F       F
Bank Sta=781.19,793.66
XS Rating Curve= 0 ,0
Exp/Cntr=0.3,0.1

Type RM Length L Ch R = 1 ,6588    ,872.48,872.98,833.95
XS GIS Cut Line= 3
2360530.33660619  643966.06616812360491.77005896643531.468018681
2360408.01941733642659.306164548
#Sta/Elev= 30
       0   79.98  114.91   74.05  150.12    74.2  156.65   73.53  203.42   73.19
   226.2   72.29  261.54   69.73  291.75   68.99  297.83   67.99  350.66    64.8
  438.47   64.49  476.56   60.99  501.51   58.51  603.17   59.96  619.24    59.9
  637.99    58.6  691.96   59.62   715.7   58.46   717.3   58.16  721.62   53.63
  735.78   58.77  747.36   59.86  777.52   60.34   803.5   61.87  906.55   63.76
  915.26   63.41  1000.5   66.32 1098.79      72 1207.11    79.4 1306.84   84.09
#Mann= 4 ,-1 , 0
       0    .085       0  476.56     .07       0   715.7     .05       0
  735.78     .09       0
Bank Sta=715.7,735.78
XS Rating Curve= 0 ,0
Exp/Cntr=0.3,0.1

Type RM Length L Ch R = 1 ,5715    ,840.65,861.74,878.21
XS GIS Cut Line= 3
 2361488.6699395643554.6078347562361106.48587613642607.394012868
2360904.74991868642390.139904812
#Sta/Elev= 30
       0   81.27    47.6   81.15   93.24   80.08  130.68    78.1  203.22    72.2
  274.28   66.01  286.08   65.99     319   63.56  330.69   64.09  447.69   59.76
  462.57   59.07  537.95   59.48  563.21   58.74  659.38   58.95  711.39   58.04
  713.27   57.43  721.19   52.04  731.43   58.44  761.11   59.17  813.55   59.36
  848.14   58.53   861.5   59.27     902   61.02  941.34   70.96   993.1   79.79
 1033.28   81.71  1055.3    83.7  1083.3   83.81 1191.99   87.21 1307.84   88.03
#Mann= 7 ,-1 , 0
       0    .045       0  203.22     .09       0  447.69     .07       0
  711.39     .05       0  731.43     .07       0   861.5     .09       0
  1083.3    .045       0
Bank Sta=711.39,731.43
XS Rating Curve= 0 ,0
Exp/Cntr=0.3,0.1

Type RM Length L Ch R = 1 ,4853    ,859.14,821.86,736.42
XS GIS Cut Line= 2
2362060.88661294643341.1700656562361999.08660617642049.399501428
#Sta/Elev= 30
       0   64.72  209.49   63.15   316.1   61.26  347.63   59.95  361.57   57.99
  391.02   57.09  434.33   56.69  527.65   58.08  609.09   57.83  614.68   56.43
  617.11    56.1   628.5   50.54  635.02   52.52  640.27   56.55  712.38   57.77
  723.96   57.27  742.36   56.52  784.82   57.09  814.55   58.73  829.99   57.65
   852.9   57.66  880.85   61.13  906.37   66.08  912.37   68.19  945.53    73.8
  981.19   76.34 1063.37   77.89 1176.84   84.11 1222.39   84.75 1293.25   83.88
#Mann= 7 ,-1 , 0
       0    .045       0  347.63     .08       0  527.65     .09       0
  614.68     .05       0  640.27     .09       0  723.96     .08       0
  981.19     .09       0
Bank Sta=614.68,640.27
XS Rating Curve= 0 ,0
Exp/Cntr=0.3,0.1

Type RM Length L Ch R = 1 ,4031    ,1315.87,1329.57,1240.21
XS GIS Cut Line= 2
2363007.45932128643887.6414351022362596.22833107642095.295043945
#Sta/Elev= 30
       0   80.73   18.39   78.07  127.98   70.05  223.65   67.25  247.72   68.18
   338.7   63.73  421.24   63.56   437.5   62.16  463.66   62.38  473.66   60.73
  511.89   61.54  616.57   59.84  635.51   60.78  748.87   58.82  961.57   62.18
 1028.32   59.86  1046.9   55.89 1061.76   49.46 1072.79    54.9 1076.59   55.69
 1142.15   55.49 1173.13   57.16 1370.75   55.04 1450.37      62 1473.26   60.47
 1509.52   63.75 1532.18   64.15 1681.24   76.87 1733.91   75.99 1838.92   75.53
#Mann= 4 ,-1 , 0
       0    .075       0  1046.9     .05       0 1076.59     .09       0
 1733.91    .045       0
#XS Ineff= 2 , 0
          958.18   65.78
Permanent Ineff=
       F       F
Bank Sta=1046.9,1076.59
XS Rating Curve= 0 ,0
Exp/Cntr=0.3,0.1

Type RM Length L Ch R = 1 ,2702    ,490.71,472.03,494.2
XS GIS Cut Line= 2
 2364483.4616062642679.6078347562363465.24476314641800.450183064
#Sta/Elev= 30
       0   77.68    9.01   76.24   20.03   75.85  117.06   74.07  176.87   71.87
   291.1    67.2  316.47      65  341.15   65.38   386.9   62.27  482.67   58.56
  530.06   56.93  572.03   56.36  592.72   57.23  613.85   56.21  739.83   58.96
  772.99    58.4  823.13   56.09  877.77   55.43  932.78   52.88  954.39   47.62
  969.95   51.73  980.05   52.86  986.83   54.76 1020.87   52.97 1054.11   53.15
  1099.4   52.03 1260.13   62.62 1295.64   68.09 1328.14   70.55 1345.24   72.78
#Mann= 5 ,-1 , 0
       0    .045       0  482.67    .075       0  877.77     .09       0
  932.78     .05       0  980.05     .09       0
#XS Ineff= 2 , 0
       0  749.34   62.86               0
Permanent Ineff=
       F       F
Bank Sta=932.78,980.05
XS Rating Curve= 0 ,0
Exp/Cntr=0.3,0.1

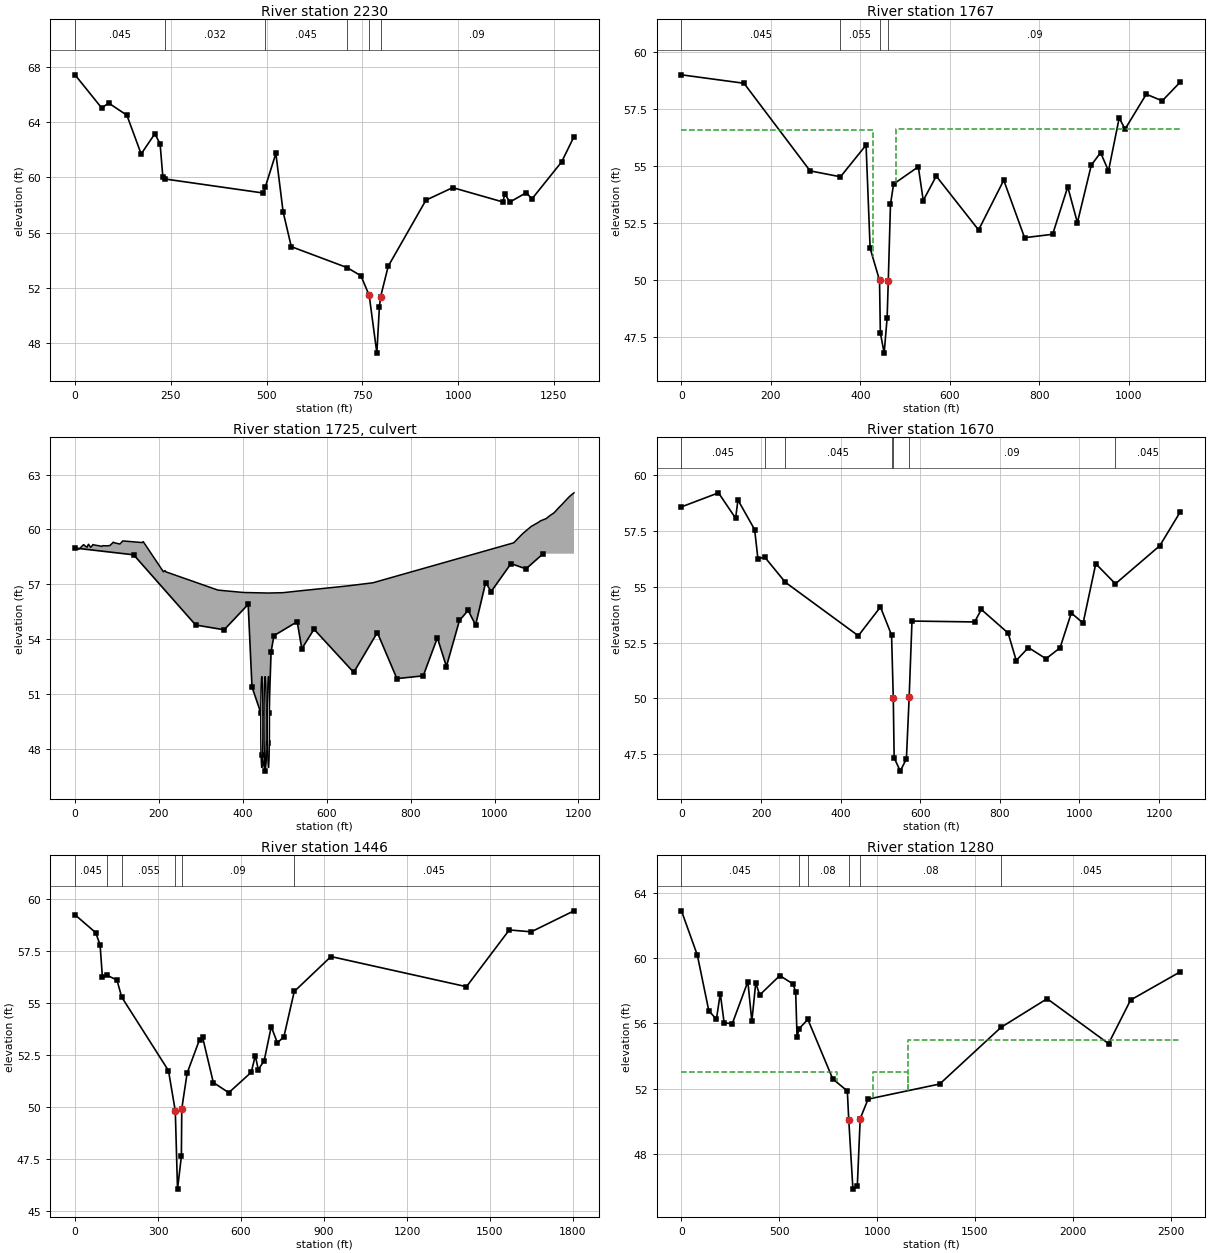
Type RM Length L Ch R = 1 ,2230    ,570.79,462.52,429.4
XS GIS Cut Line= 3
2364781.82447715642234.2957246012364077.16390628641733.717176974
2363642.04563026641679.808718011
#Sta/Elev= 30
       0   67.44   69.61   65.04   88.08   65.39  135.52   64.51  172.76    61.7
  208.55   63.17  222.19   62.43  229.44   60.02  234.25   59.89  491.43   58.87
  497.28   59.34  524.44   61.74  543.26   57.52  564.71   54.98  710.55   53.46
   746.5   52.87  768.17   51.44  788.12   47.26  794.77   50.62  797.84   51.34
  817.76   53.56   916.2   58.35  986.08   59.26 1117.34   58.22 1121.93    58.8
 1135.57   58.22 1178.68    58.9 1192.64   58.43 1270.64   61.13 1302.81   62.96
#Mann= 6 ,-1 , 0
       0    .045       0  234.25    .032       0  497.28    .045       0
  710.55    .055       0  768.17     .05       0  797.84     .09       0
Bank Sta=768.17,797.84
XS Rating Curve= 0 ,0
Exp/Cntr=0.5,0.3

Type RM Length L Ch R = 1 ,1767    ,95.07,97.08,93.19
BEGIN DESCRIPTION:
Surveyed Section
END DESCRIPTION:
XS GIS Cut Line= 6
2364749.02753246641594.6258040822364530.50760001641383.438500017
2364423.19790001641401.1229000092364385.70770001641414.649299994
2364311.78200002641431.523800001  2363735.971348641541.680024624
#Sta/Elev= 30
       0   58.98  139.82   58.61  287.61   54.77 355.551   54.51 412.759    55.9
  421.85   51.38 442.866   49.97 444.695   47.67  453.21   46.78 459.846   48.32
  462.46   49.96 467.349    53.3 474.242   54.19 529.606   54.95   540.6   53.47
  569.67   54.54  664.36   52.18  720.59   54.36  767.21   51.84  829.99   51.99
   863.7   54.07  885.27    52.5  916.35   55.02  937.09   55.57  954.82   54.77
  978.75   57.09  991.87    56.6 1039.24   58.13 1074.91   57.84 1115.73   58.67
#Mann= 4 ,-1 , 0
       0    .045       0 355.551    .055       0 442.866     .05       0
  462.46     .09       0
#XS Ineff= 2 , 0
       0  427.69   56.55  478.69       0   56.62
Permanent Ineff=
       F       F
Bank Sta=442.866,462.46
XS Rating Curve= 0 ,0
Exp/Cntr=0.5,0.3

Type RM Length L Ch R = 2 ,1725    ,,,
BEGIN DESCRIPTION:
Shingleton Road
Shingleton Road
END DESCRIPTION:
Bridge Culvert--1,0,-1,-1, 0
Deck Dist Width WeirC Skew NumUp NumDn MinLoCord MaxHiCord MaxSubmerge Is_Ogee
35.26,19.71,2.6,0, 49, 50, , , 0.98, 0, 0,0,,
       0    9.64   19.95   20.87   28.48   32.06   37.39   39.92   42.68   49.77
   56.54    63.6    66.1   76.12   83.32   90.17   91.11   95.31  106.89  113.92
  159.96  162.66  210.83  214.37  216.53 340.736 401.585 461.144  496.27  527.87
 649.997 710.001 1044.65 1046.19 1065.79 1065.88 1067.09 1085.15 1087.93 1104.08
 1109.83 1123.01 1131.59 1141.96 1153.53 1160.99 1175.56 1180.13 1189.35
   58.96   58.92   59.16   59.16   59.02   59.19   59.02   59.08   59.17   59.13
   59.11   59.07   59.11    59.1   59.12   59.27    59.3   59.26    59.2   59.37
   59.28   59.33   57.68   57.75   57.68   56.68   56.55   56.52   56.54   56.62
   56.91   57.08   59.26   59.28   59.74   59.74   59.77   60.12   60.17   60.38
   60.47   60.59   60.75   60.91    61.2   61.37   61.73   61.83      62
                                                                                
                                                                                
                                                                                
                                                                                
                                                                        
       0    9.64   19.95   20.87   28.48   32.06   37.39   39.92   42.68   49.77
   56.54    63.6    66.1   76.12   83.32   90.17   91.11   95.31  106.89  113.92
  159.96  162.66  210.83  214.37  216.53 340.736 401.585 461.144  496.27  527.87
 649.997 710.001 1044.65 1046.19 1065.79 1065.88 1067.09 1085.15 1087.93 1104.08
 1109.83 1123.01 1131.59 1141.96 1153.53 1160.99 1175.56 1180.13 1189.35 1254.04
   58.96   58.92   59.16   59.16   59.02   59.19   59.02   59.08   59.17   59.13
   59.11   59.07   59.11    59.1   59.12   59.27    59.3   59.26    59.2   59.37
   59.28   59.33   57.68   57.75   57.68   56.68   56.55   56.52   56.54   56.62
   56.91   57.08   59.26   59.28   59.74   59.74   59.77   60.12   60.17   60.38
   60.47   60.59   60.75   60.91    61.2   61.37   61.73   61.83      62      63
                                                                                
                                                                                
                                                                                
                                                                                
                                                                                
BR Coef=-1 , 1 , 0 ,1.25, 0 ,,,0.8,0,2,0,
WSPro=,,,, 1 ,,,, 0 ,,,, 0 ,,,,-1 ,-1 ,-1 , 0 , 0 , 0 , 0 , 0
Multiple Barrel Culv=1,5,,48,0.024,0.5,1,2,1,46.96,46.78, 3,Culvert #1  , 0 ,18.09
  445.19  543.37  453.19  551.37  461.19  559.37
Culvert Bottom n=0.024
BC Design=,, 0 ,, 0 ,,,,,,
BC Use User HTab Curves=0
BC User HTab FreeFlow(D)= 0

Type RM Length L Ch R = 1 ,1670    ,109.9,223.84,252.52
BEGIN DESCRIPTION:
Survyed Section
END DESCRIPTION:
XS GIS Cut Line= 6
2364863.35606259 641484.823446812364661.92132977641273.641872019
2364497.88059999641308.1807000042364386.31890003641320.863800019
2364310.41970001641341.6803999992363716.81881458641447.820665613
#Sta/Elev= 30
       0   58.59   93.05   59.22  136.13   58.08  141.96    58.9   183.9   57.57
  192.18   56.26  209.17   56.34  260.97   55.21  444.45   52.81 500.105    54.1
 528.009   52.84 532.328   50.03 534.527   47.34 549.812   46.74  565.32   47.29
 572.262   50.07 579.348   53.47  736.81   53.43  753.56   53.99  820.96   52.93
  841.28    51.7  871.94   52.28  916.11   51.78  951.46   52.27  979.68   53.83
 1009.38   53.38  1041.2   56.04 1090.52   55.14 1202.21   56.85 1254.04   58.38
#Mann= 7 ,-1 , 0
       0    .045       0  209.17    .035       0  260.97    .045       0
 528.009     .09       0 532.328     .05       0 572.262     .09       0
 1090.52    .045       0
#XS Ineff= 2 , 0
       0  525.87    51.6  576.87       0    51.6
Permanent Ineff=
       F       F
Bank Sta=532.328,572.262
XS Rating Curve= 0 ,0
Exp/Cntr=0.5,0.3

Type RM Length L Ch R = 1 ,1446    ,94.87,166.75,256.59
XS GIS Cut Line= 4
2364816.99132346641411.5599854742364608.19569434641208.348484546
2364471.13072994641115.1443087612363242.01165557640565.362301737
#Sta/Elev= 30
       0   59.23   74.84   58.37    90.7   57.78   99.13   56.22  115.0756.32292
  151.61   56.09  168.82   55.27  337.93   51.73  362.54   49.79  370.55   46.03
  384.49    47.6  385.97    49.9   405.3   51.61  450.02   53.22   461.3   53.33
  499.97   51.16   555.8   50.67  636.88   51.65  651.73   52.45  662.53   51.78
  683.76   52.21  709.26   53.84  731.64   53.07  754.99   53.36   792.5   55.54
  925.25   57.22 1414.88   55.77 1569.65    58.5 1649.05   58.41 1803.59   59.42
#Mann= 6 ,-1 , 0
       0    .045       0  115.07    .035       0  168.82    .055       0
  362.54     .05       0  385.97     .09       0   792.5    .045       0
Bank Sta=362.54,385.97
XS Rating Curve= 0 ,0
Exp/Cntr=0.5,0.3

Type RM Length L Ch R = 1 ,1280    ,120.5,133.7,108.04
BEGIN DESCRIPTION:
Survyed Section
END DESCRIPTION:
XS GIS Cut Line= 6
2365036.82144199641868.3446449792364926.27836244641581.582793847
2364687.32950003641144.0685000272364636.85519999640935.471700013
2364620.68453085640793.3318471312363267.83880098 640497.98752135
#Sta/Elev= 30
       0   62.92   81.36   60.19  139.57   56.79  178.54   56.25  198.43   57.84
  218.11   56.04   259.5   55.98  339.39   58.57  359.66   56.13  379.67   58.49
   399.9   57.75  502.58   58.94  569.78   58.43  583.66   57.95  590.84   55.15
   600.6   55.67     646   56.25  773.28   52.59  847.75   51.85  855.05   50.08
 876.246   45.82   898.9   46.04  913.52   50.15  953.71   51.35 1320.06   52.28
 1633.24   55.76 1868.83   57.52 2182.77   54.76 2295.58   57.44 2550.34   59.18
#Mann= 6 ,-1 , 0
       0    .045       0   600.6    .035       0     646     .08       0
  855.05     .05       0  913.52     .08       0 1633.24    .045       0
#XS Ineff= 3 ,-1
       0     795   53.04     980    1160   53.04    1160 2550.34      55
Permanent Ineff=
       F       F       T
Bank Sta=855.05,913.52
XS Rating Curve= 0 ,0
Exp/Cntr=0.5,0.3