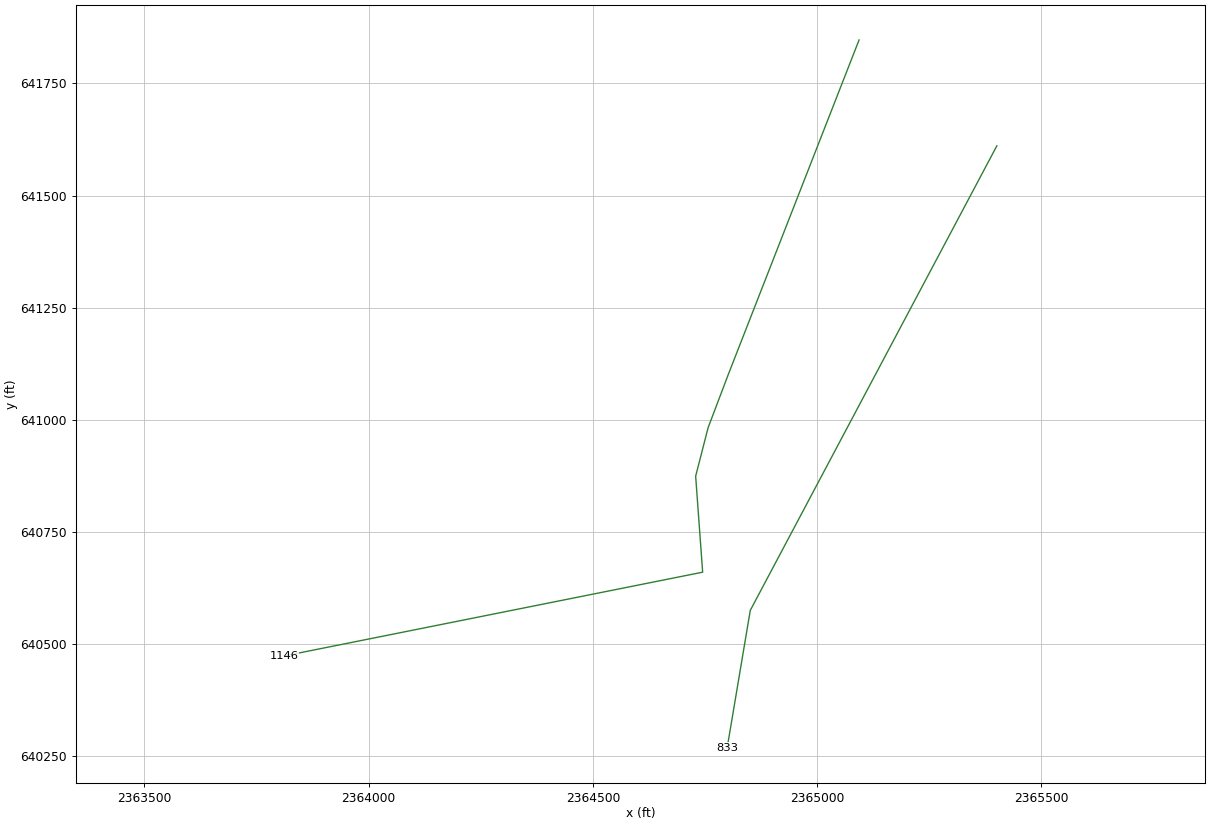
HEC-RAS study DTL_Appletree_Swamp.prj: DTL_Appletree_Swamp_Main

--- DTL_Appletree_Swamp.g01 (geometry) --- (continued)

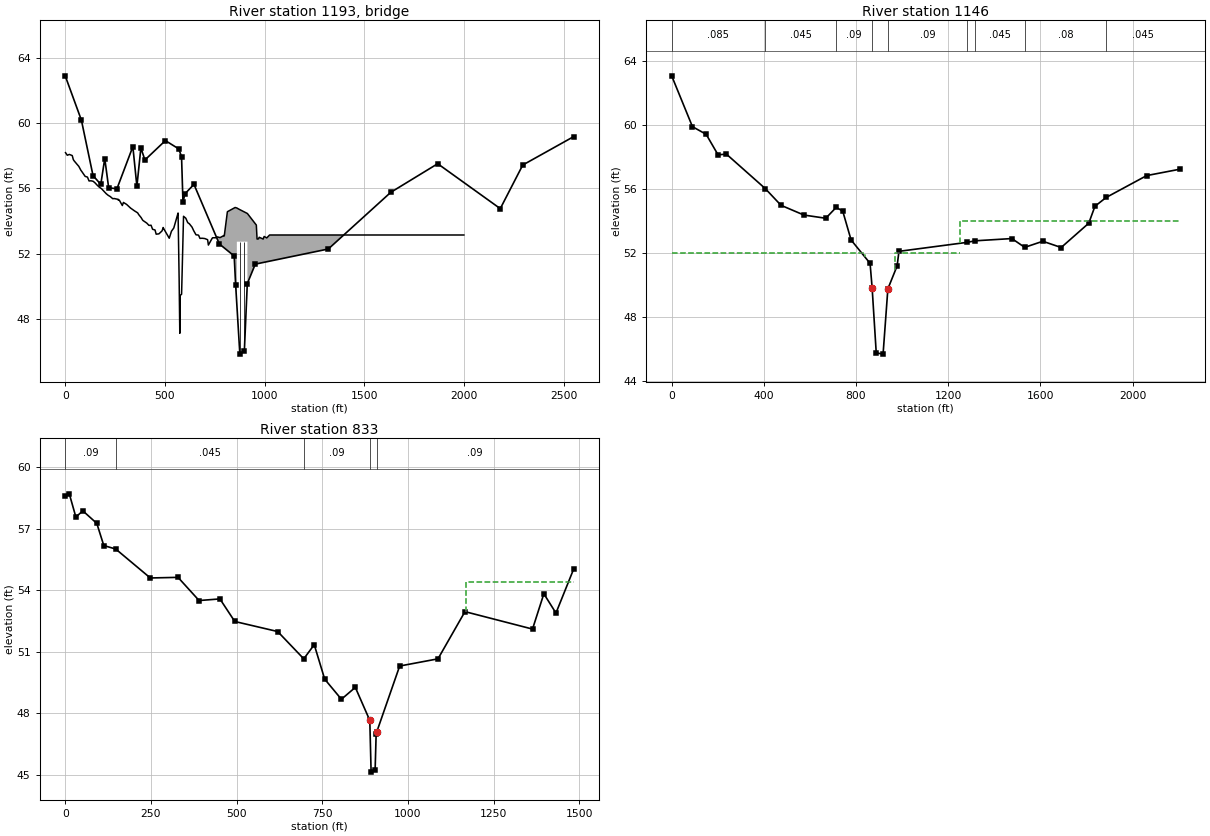
Type RM Length L Ch R = 3 ,1193    ,,,
Bridge Culvert--1,0,-1,-1, 0
Deck Dist Width WeirC Skew NumUp NumDn MinLoCord MaxHiCord MaxSubmerge Is_Ogee
66,28,2.6,0, 105, 106, , , 0.98, 0, 1,1,,
     1.5   10.39   20.82   35.34    40.5   43.93   58.88   68.13   78.93   82.19
  100.18  111.49  119.62  129.38  140.19  149.01  161.21  170.02  182.63  191.79
  205.56  215.42  226.22  238.43   246.1  265.04  266.28  266.75  272.02  286.55
  292.06  308.02  325.64  327.79  328.23  330.74   347.9  363.56  368.34  380.84
  387.66  390.38  409.33  420.15  430.68  438.51  450.59  456.35  470.09  485.74
  489.37  491.26  495.55   521.1   521.9  533.02  544.77  559.91  566.25  571.59
   574.9  576.91  577.12   583.9  593.65  605.09  614.67  621.55  622.24  636.46
  644.36  656.26  666.33  669.33  676.14  686.13  695.02  700.74  714.53  718.35
  735.52   739.4  756.54  761.17  764.09  776.83  796.45  797.37  798.22 813.666
 852.486 861.133 869.489 914.133 958.923  962.58   969.5  973.42  993.29  995.05
  998.14 1011.13 1025.34    1100    2000
    58.2   58.04   58.09   58.02   57.78   57.71   57.49   57.36   57.11   57.06
   56.74    56.7   56.46   56.47   56.44   56.35   56.19   56.09   55.98   55.86
   55.68   55.58    55.5   55.37   55.38   55.33   55.28   55.32   55.27   54.95
   55.14   55.02   54.82   54.79   54.79   54.77   54.62    54.5    54.4   54.21
   54.07   54.03   53.87   53.73   53.74   53.49   53.45   53.19   53.21   53.39
   53.51    53.6    53.5   52.96   52.94   53.37   53.57   54.22   54.49   50.44
    47.1   49.21   49.43    49.5   54.29   54.17    53.9   53.84   53.84   53.62
   53.41   53.15   53.14   53.12   52.93   52.94   52.93   52.92   52.85   52.52
    52.9   52.97   52.97   53.02   53.02   52.98   53.11   53.08    53.1   54.57
   54.83    54.8   54.74   54.46   53.75   52.89    52.9      53   52.89   52.96
   53.05   52.96   53.14   53.14   53.14
                                                                                
                                                                                
                                                                                
                                                                                
                                                                                
                                                                                
                                                                                
                                                                                
                                                                                
           52.73   52.73   52.73
                                        
     .14    3.84   19.94   28.83   39.26   53.78   58.94   62.37   77.32   86.57
   97.37  100.63  118.62  129.93  138.06  147.82  158.63  167.45  179.65  188.46
  201.07  210.23     224  233.86  244.66  256.87  264.54  283.48  284.72  285.19
  290.46  304.99   310.5  326.46  344.08  346.23  346.67  349.18  366.34     382
  386.78  399.28   406.1  408.82  427.77  438.59  449.12  456.95  469.03  474.79
  488.53  504.18  507.81   509.7  513.99  539.54  540.34  551.46  563.21  578.35
  584.69  590.03  593.34  595.35  595.56  602.34  612.09  623.53  633.11  639.99
  640.68   654.9   662.8   674.7  684.77  687.77  694.58  704.57  713.46  719.18
  732.97  736.79  753.96  757.84  774.98  779.61  782.53  795.27  814.89  815.81
  816.66 832.106 870.926 879.573 887.929 932.573 977.363  981.02  987.94  991.86
 1011.73 1013.49 1016.58 1029.57    1100    2000
   58.46   58.47    58.2   58.04   58.09   58.02   57.78   57.71   57.49   57.36
   57.11   57.06   56.74    56.7   56.46   56.47   56.44   56.35   56.19   56.09
   55.98   55.86   55.68   55.58    55.5   55.37   55.38   55.33   55.28   55.32
   55.27   54.95   55.14   55.02   54.82   54.79   54.79   54.77   54.62    54.5
    54.4   54.21   54.07   54.03   53.87   53.73   53.74   53.49   53.45   53.19
   53.21   53.39   53.51    53.6    53.5   52.96   52.94   53.37   53.57   54.22
   54.49   50.44    47.1   49.21   49.43    49.5   54.29   54.17    53.9   53.84
   53.84   53.62   53.41   53.15   53.14   53.12   52.93   52.94   52.93   52.92
   52.85   52.52    52.9   52.97   52.97   53.02   53.02   52.98   53.11   53.08
    53.1   54.57   54.83    54.8   54.74   54.46   53.75   52.89    52.9      53
   52.89   52.96   53.05   52.96   53.14   53.14
                                                                                
                                                                                
                                                                                
                                                                                
                                                                                
                                                                                
                                                                                
                                                                                
                                                                                
                           52.73   52.73   52.73
                                                
Pier Skew, UpSta & Num, DnSta & Num=  ,878.13, 2 ,896.57, 2 , 0 , 0 , 0 ,,
       1       1
      40      53
       1       1
      40      53
Pier Skew, UpSta & Num, DnSta & Num=  ,895.13, 2 ,913.57, 2 , 0 , 0 , 0 ,,
       1       1
      40      53
       1       1
      40      53
BR Coef=-1 , 1 , 0 ,1.25, 0 ,,,0.8,0,2,0,
WSPro=,,,, 1 ,,,, 0 ,,,, 0 ,,,,-1 ,-1 ,-1 , 0 , 0 , 0 , 0 , 0
BC Design=,, 0 ,, 0 ,,,,,,
BC Use User HTab Curves=0
BC User HTab FreeFlow(D)= 0

Type RM Length L Ch R = 1 ,1146    ,300.48,313.31,262.93
BEGIN DESCRIPTION:
Surveyed Section
END DESCRIPTION:
XS GIS Cut Line= 6
2365093.75177151641846.8926367612364802.65211123641102.331273898
2364757.16008227640982.4054491972364729.33928157640874.113914192
2364744.94461526640660.0321378562363811.77559257640473.263121739
#Sta/Elev= 30
       0    63.1   90.15   59.92  149.75   59.44  201.16   58.16  237.72    58.2
  405.87   56.05  474.52      55  574.12   54.39  668.72   54.19  714.11   54.87
  742.28   54.64  778.68   52.83  861.05   51.37  869.95   49.84  887.77   45.77
  917.46   45.69  938.24   49.77  978.43   51.21  986.34   52.12 1281.08   52.68
    1318   52.78 1476.34   52.92 1532.13   52.37 1610.69   52.75 1690.38   52.36
 1810.09   53.88 1836.98   54.94 1885.54   55.49 2061.69   56.86 2206.09   57.26
#Mann= 9 ,-1 , 0
       0    .085       0  405.87    .045       0  714.11     .09       0
  869.95     .05       0  938.24     .09       0 1281.08    .035       0
    1318    .045       0 1532.13     .08       0 1885.54    .045       0
#XS Ineff= 3 ,-1
       0     839   52.04     971    1250   52.04    1250 2206.09      54
Permanent Ineff=
       F       F       T
Bank Sta=869.95,938.24
XS Rating Curve= 0 ,0
Exp/Cntr=0.5,0.3

Type RM Length L Ch R = 1 ,833     ,916.92,832.65,771.82
XS GIS Cut Line= 3
2365401.08858378 641610.913552972364851.16412285640574.895148903
2364799.70529722640268.884409562
#Sta/Elev= 30
       0   58.59   11.94    58.7   31.07   57.57   51.52   57.87   92.19   57.26
  112.59   56.18  147.43   56.01  248.37    54.6  329.18   54.63  390.67    53.5
   451.4   53.58   494.8   52.48  619.99   51.99  696.08   50.66  726.65   51.35
  757.16   49.67  805.93   48.69   846.5   49.27  888.75   47.66  892.57   45.14
  904.26   45.23  907.32   47.01  908.63   47.08  975.93   50.31 1087.73   50.66
 1166.44   52.96 1363.56   52.11 1396.61   53.83 1431.94   52.89 1483.23   55.02
#Mann= 5 ,-1 , 0
       0     .09       0  147.43    .045       0  696.08     .09       0
  888.75     .05       0  908.63     .09       0
#XS Ineff= 2 , 0
                         1169.89           54.42
Permanent Ineff=
       F       F
Bank Sta=888.75,908.63
XS Rating Curve= 0 ,0
Exp/Cntr=0.3,0.1

Chan Stop Cuts=-1
Use User Specified Reach Order=0