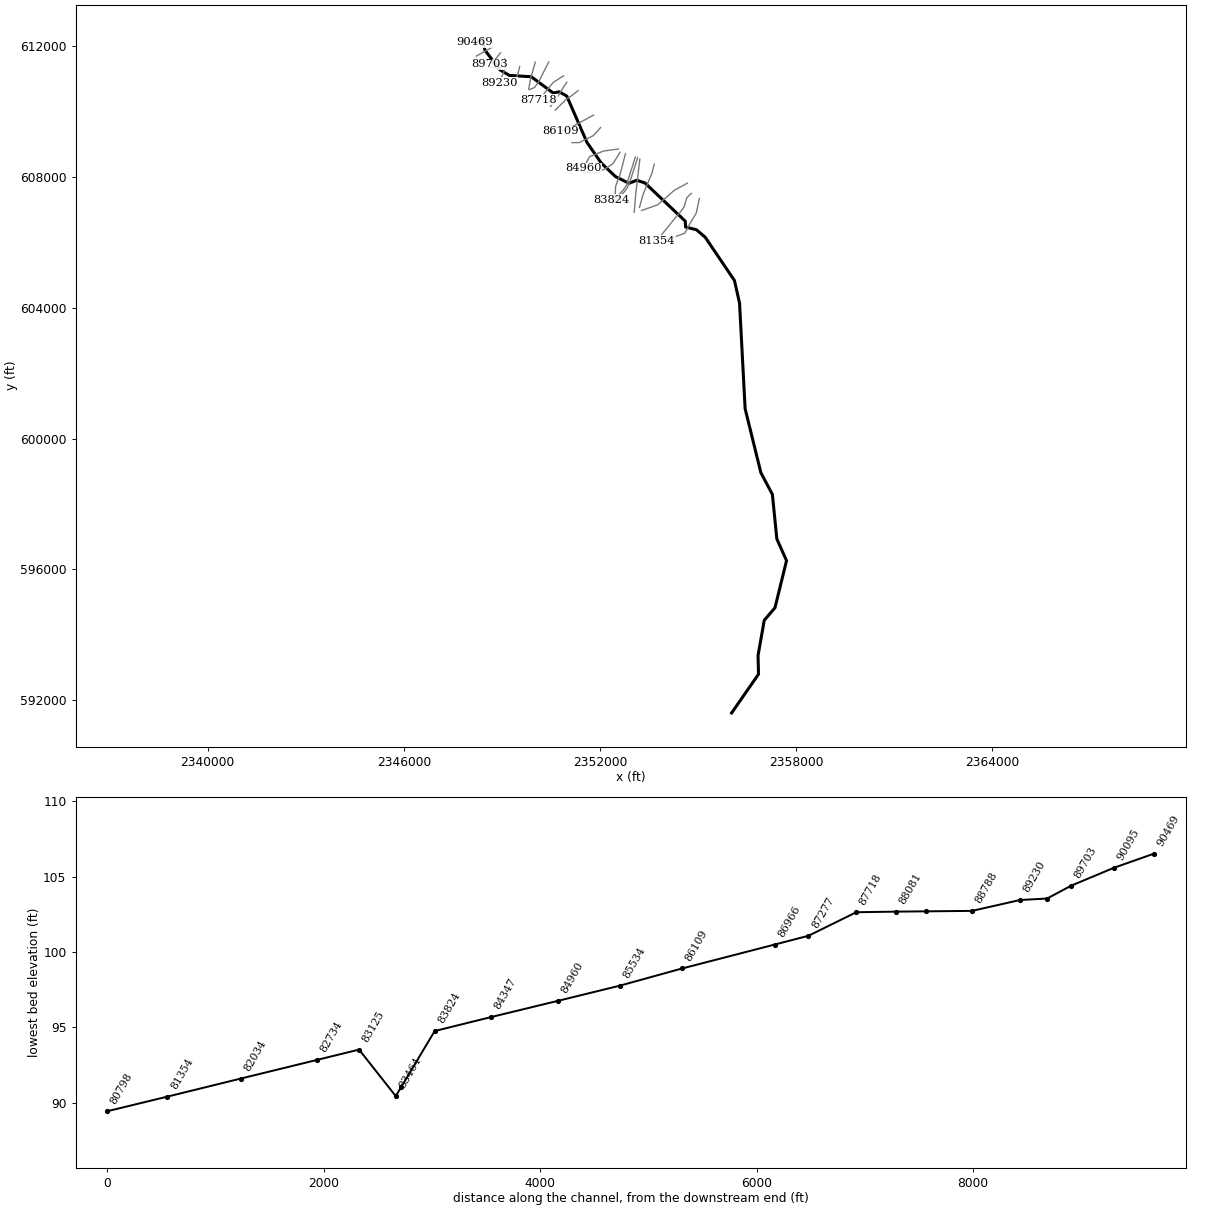
--- DTL_Bear_Creek.prj (project) ---

Proj Title=DTL_Bear_Creek
Current Plan=p01
Default Exp/Contr=0.3,0.1
English Units
Geom File=g02
Geom File=g01
Flow File=f01
Flow File=f02
Plan File=p01
Plan File=p02
Y Axis Title=Elevation
X Axis Title(PF)=Main Channel Distance
X Axis Title(XS)=Station
BEGIN DESCRIPTION:
END DESCRIPTION:
DSS Export Rating Curves= 0
DSS Export Rating Curve Sorted= 0
DSS Export Volume Flow Curves= 0
DXF OffsetX= 0
DXF OffsetY= 0
DXF ScaleX= 1
DXF ScaleY= 10

--- DTL_Bear_Creek.p01 (plan) ---

Plan Title=DTL_Bear_Creek
Program Version=4.00
Short Identifier=Multi Profile
Geom File=g02
Flow File=f01
Subcritical Flow
K Sum by GR= 0
Std Step Tol= 0.01
Critical Tol= 0.01
Num of Std Step Trials= 20
Max Error Tol= 0.3
Flow Tol Ratio= 0.001
Split Flow NTrial= 30
Split Flow Tol= 0.02
Split Flow Ratio= 0.02
Log Output Level= 0
Friction Slope Method= 1
Unsteady Friction Slope Method= 2
Unsteady Bridges Friction Slope Method= 1
Parabolic Critical Depth
Global Vel Dist= 0 , 0 , 0
Global Log Level= 0
CheckData=True
Encroach Param=-1 ,10,10, 2
Encroach River=Bear Creek
Encroach Reach=Main
Encroach Node=90469
       1     100     135
Encroach Node=90095
       1   231.5  264.55
Encroach Node=89703
       1  341.34  374.45
Encroach Node=89481
       1     321     355
Encroach Node=89230
       1     377     411
Encroach Node=88788
       1     230     350
Encroach Node=88361
       1     405     505
Encroach Node=88081
       1     610     710
Encroach Node=87718
       1     480     640
Encroach Node=87277
       1     340     500
Encroach Node=86966
       1     350     485
Encroach Node=86109
       1     455     570
Encroach Node=85534
       1     505     620
Encroach Node=84960
       1     655     770
Encroach Node=84347
       1     555     700
Encroach Node=83824
       1     675     820
Encroach Node=83517
       1     615     865
Encroach Node=83464
       1     610     860
Encroach Node=83125
       1     595     830
Encroach Node=82734
       1     650     850
Encroach Node=82034
       1     830    1050
Encroach Node=81354
       1     624    1130
Encroach Node=80798
       1  548.71 1067.46
Encroach Node=80139
       1     650    1065
Encroach Node=79258
       1   503.2  997.29
Encroach Node=78555
       1  539.71 1166.23
Encroach Node=78194
       1      70 1064.79
Encroach Node=78067
       1      80     734
Encroach Node=77840
       1     485     595
Encroach Node=77763
       1     600     710
Encroach Node=77646
       1     630     750
Encroach Node=77427
       1  634.02     755
Encroach Node=76647
       1     697     780
Encroach Node=76019
       1     405     510
Encroach Node=75475
       1     385     525
Encroach Node=74859
       1  648.33     830
Encroach Node=74527
       1  600.61     845
Encroach Node=73493
       1     785    1035
Encroach Node=72565
       1     660     920
Encroach Node=71645
       1     380     685
Encroach Node=70720
       1     560     920
Encroach Node=69800
       1     550     905
Encroach Node=68953
       1     590     945
Encroach Node=68119
       1     730    1085
Encroach Node=67246
       1     750    1100
Encroach Node=66439
       1     495     825
Encroach Node=66049
       1     390     700
Encroach Node=65949
       1     390     700
Encroach Node=65580
       1     270     610
Encroach Node=64617
       1  714.03 1214.03
Computation Interval=1HOUR
Output Interval=1HOUR
Run HTab= 0
Run UNet= 0
Run PostProcess= 0
Run WQNet= 0
UNET Theta= 1
UNET Theta Warmup= 1
UNET ZTol= 0.02
UNET ZSATol= 0.05
UNET MxIter= 20
UNET MaxInSteps= 0
UNET DtIC= 0
UNET DtMin= 0
UNET MaxCRTS= 20
UNET WFStab= 2
UNET SFStab= 1
UNET WFX= 1
UNET SFX= 1
UNET DSS MLevel= 4
UNET DZMax Abort= 100
UNET Convert EG Bridges= 0
UNET Use Existing IB Tables=-1
UNET Froude Reduction=False
UNET Froude Limit= 1
UNET Froude Power= 10
UNET Time Slicing=0,0, 5
Instantaneous Interval=1HOUR
Write IC File= 0
Echo Input=False
Echo Output=False
Write Detailed= 0
Detailed Automatic Start=False, 10
WQ ULTIMATE=-1
WQ Max Comp Step=1HOUR
WQ Output Interval=15MIN
WQ Output Selected Increments= 0
WQ Output face flow=0
WQ Output face velocity=0
WQ Output face area=0
WQ Output face dispersion=0
WQ Output cell volume=0
WQ Output cell surface area=0
WQ Output cell continuity=0
WQ Output face conc=0
WQ Output face dconc_dx=0
WQ Output face courant=0
WQ Output face peclet=0
WQ Output face adv mass=0
WQ Output face disp mass=0
WQ Output cell mass=0
WQ Output cell source sink temp=0
WQ Output cell source sink nsm=0
WQ Output MaxMinRange=-1
WQ Daily Max Min Mean=-1
WQ Daily Range=0
WQ Daily Time=0
WQ Create Restart=0
WQ Fixed Restart=0
WQ System Summary=False
Sorting and Armoring Iterations= 10
XS Update Threshold= 0.02
Hydraulics Update Threshold= 0.02
Energy Slope Method= 1
Volume Change Method= 0
XS Weighting Method= 0
Number of US Weighted Cross Sections= 1
Number of DS Weighted Cross Sections= 1
Upstream XS Weight=0.25
Main XS Weight=0.5
Downstream XS Weight=0.25
Number of DS XS's Weighted with US Boundary= 1
Upstream Boundary Weight= 1
Weight of XSs Associated with US Boundary= 0
Number of US XS's Weighted with DS Boundary= 1
Downstream Boundary Weight= 0.5
Weight of XSs Associated with DS Boundary= 0.5
Sediment Output Level= 4
Mass or Volume Output= 0
Output Increment Type= 1
Profile and TS Output Increment= 10
XS Output Flag= 0
XS Output Increment= 10
Disregard all LS=0
Disregard all Conn=0
Disregard all Breaches=0
Disregard all Pumps=0

--- DTL_Bear_Creek.p02 (plan) ---

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Plan Title=DTL_Bear_Creek_Future
Short Identifier=Future
Geom File=g02
Flow File=f02

--- DTL_Bear_Creek.f01 (steady flow) ---

Flow Title=DTL_Bear_Creek
Program Version=4.00
Number of Profiles= 6
Profile Names=100-yr,FW,10-yr,25-yr,50-yr,500-yr
River Rch & RM=Bear Creek,Main            ,90469
     530     530     210     320     410     860
River Rch & RM=Bear Creek,Main            ,88788
     690     690     290     420     550    1130
River Rch & RM=Bear Creek,Main            ,83824
     780     780     330     480     620    1250
River Rch & RM=Bear Creek,Main            ,82034
    1120    1120     490     700     900    1780
River Rch & RM=Bear Creek,Main            ,74859
    1170    1170     510     740     940    1850
River Rch & RM=Bear Creek,Main            ,74527
    1390    1390     610     880    1120    2180
River Rch & RM=Bear Creek,Main            ,73493
    1830    1830     830    1170    1480    2830
River Rch & RM=Bear Creek,Main            ,68953
    2020    2020     920    1300    1640    3120
Boundary for River Rch & Prof#=Bear Creek,Main            , 1
Up Type= 0
Dn Type= 1
Dn Known WS=82.56
Boundary for River Rch & Prof#=Bear Creek,Main            , 2
Up Type= 0
Dn Type= 1
Dn Known WS=83.33
Boundary for River Rch & Prof#=Bear Creek,Main            , 3
Up Type= 0
Dn Type= 1
Dn Known WS=80.82
Boundary for River Rch & Prof#=Bear Creek,Main            , 4
Up Type= 0
Dn Type= 1
Dn Known WS=81.69
Boundary for River Rch & Prof#=Bear Creek,Main            , 5
Up Type= 0
Dn Type= 1
Dn Known WS=82.12
Boundary for River Rch & Prof#=Bear Creek,Main            , 6
Up Type= 0
Dn Type= 1
Dn Known WS=83.59
DSS Import GetInterval= 0
DSS Import GetPeak= 0
DSS Import FillOption= 0

--- DTL_Bear_Creek.f02 (steady flow) ---

Flow Title=DTL_Bear_Creek_Future
Program Version=4.00
Number of Profiles= 3
Profile Names=100-yr-10%,100-yr-20%,100-yr-35%
River Rch & RM=Bear Creek,Main            ,90469
     930    1190    1450
River Rch & RM=Bear Creek,Main            ,88788
    1210    1550    1900
River Rch & RM=Bear Creek,Main            ,83824
    1350    1730    2120
River Rch & RM=Bear Creek,Main            ,82034
    1930    2470    3020
River Rch & RM=Bear Creek,Main            ,74859
    2010    2580    3150
River Rch & RM=Bear Creek,Main            ,74527
    2370    3040    3720
River Rch & RM=Bear Creek,Main            ,73493
    3080    3950    4830
River Rch & RM=Bear Creek,Main            ,68953
    3410    4370    5340
Boundary for River Rch & Prof#=Bear Creek,Main            , 1
Up Type= 0
Dn Type= 1
Dn Known WS=83.85
Boundary for River Rch & Prof#=Bear Creek,Main            , 2
Up Type= 0
Dn Type= 1
Dn Known WS=84.62
Boundary for River Rch & Prof#=Bear Creek,Main            , 3
Up Type= 0
Dn Type= 1
Dn Known WS=85.31
DSS Import GetInterval= 0
DSS Import GetPeak= 0
DSS Import FillOption= 0

--- DTL_Bear_Creek.g02 (geometry) ---

Geom Title=DTL_Bear_Creek
Program Version=4.00

River Reach=Bear Creek      ,Main
Reach XY= 30
2348378.15080774612235.3128435612348485.90753733611875.155580163
2348932.61872374611285.5432860552349228.87711778611108.659597829
2349899.36127566611068.7933468672350566.73151951610572.727696016
2350757.33944964610607.2366378612350984.77530915610476.997148141
2351602.06461941609061.349477351 2352041.6909859608425.321982563
2352478.71601298608011.7090105122352889.62477955607808.630361393
2353125.14886558607902.4527537382353377.47879194607819.209891424
2354610.51368977606649.9078100322354618.31770808606471.716057926
 2354951.2891573606388.4731956122355219.22712033606159.555324286
 2356113.9207616604837.0195851922356270.16825691604143.517252922
2356440.55599068 600913.954329552356923.10445811598955.145725995
2357274.28528342598293.1048367472357410.85560438596931.303636298
2357707.40830132596265.3607378752357353.62613654594824.218684271
2357025.85736625594441.8217855692356835.95958664 593364.86725454
2356850.13649842592791.6730857642356026.94301863591606.361788422

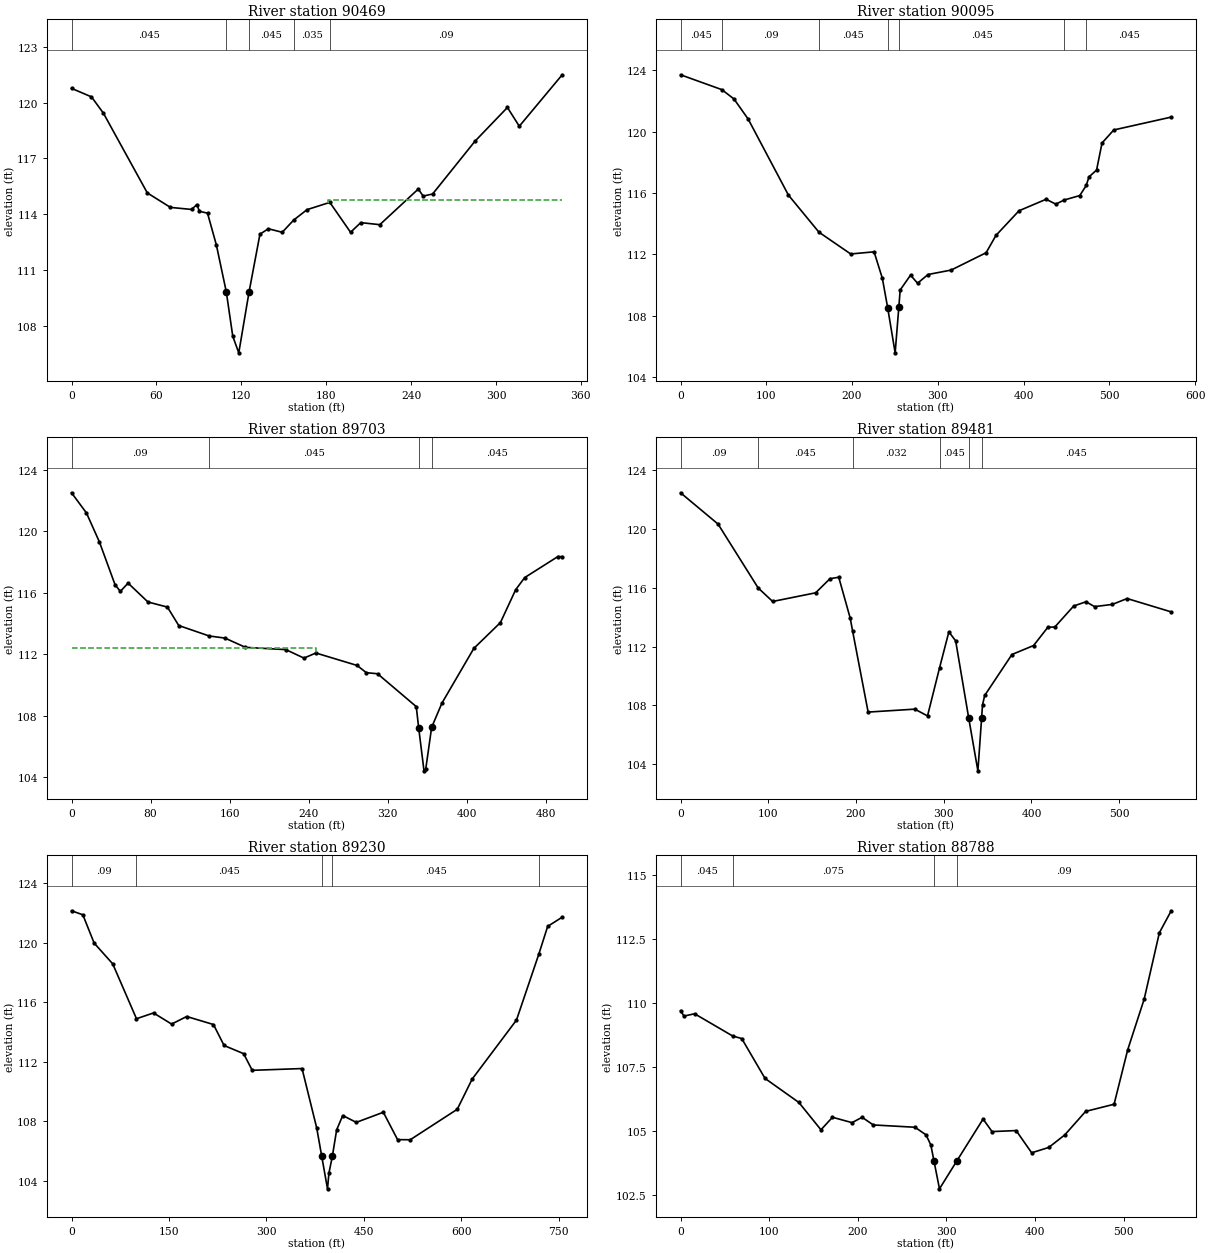
Type RM Length L Ch R = 1 ,90469   ,354.39,373.86,380.36
XS GIS Cut Line= 2
2348494.90662423612244.3260136542348166.57266732612132.771584913
#Sta/Elev= 30
       0  120.77   14.12  120.31   22.48  119.44   53.56  115.14    69.9  114.36
   84.81  114.25   88.56  114.51   90.42  114.15   96.11  114.05  102.36  112.34
  109.39  109.81  113.96  107.42   118.2  106.53  125.45   109.8  133.17  112.92
  139.11  113.21  148.91  113.02  157.02  113.68  166.48  114.24  182.54  114.63
   197.2  113.02  204.41  113.54  217.87  113.43  245.07  115.35  248.49  114.97
  255.17  115.08  285.09  117.92  308.04  119.74  316.44  118.73  346.77   121.5
#Mann= 5 ,-1 , 0
       0    .045       0  109.39     .05       0  125.45    .045       0
  157.02    .035       0  182.54     .09       0
#XS Ineff= 2 , 0
       0                  181.28       0  114.78
Permanent Ineff=
       F       F
Bank Sta=109.39,125.45
XS Rating Curve= 0 ,0
Exp/Cntr=0.3,0.1

Type RM Length L Ch R = 1 ,90095   ,383.73,392.76,398.26
XS GIS Cut Line= 2
2348720.37983601611980.5387281782348220.71469161611701.778173938
#Sta/Elev= 30
       0  123.72   48.18  122.75   62.34  122.14   78.87  120.83  125.81  115.87
  161.41  113.45  198.41  112.03  225.68  112.17  235.34  110.44   241.5  108.53
  250.25  105.58  254.55  108.57  256.11  109.68  268.21  110.65  276.37  110.12
  288.59  110.69  315.55  110.98  356.31  112.11  367.79  113.24   394.7  114.85
  426.32   115.6  437.55  115.28  447.32  115.55  465.51  115.84  473.07   116.5
  476.25  117.06  485.09   117.5  491.48  119.27  505.16  120.12  572.17  120.96
#Mann= 7 ,-1 , 0
       0    .045       0   48.18     .09       0  161.41    .045       0
   241.5     .05       0  254.55    .045       0  447.32    .035       0
  473.07    .045       0
Bank Sta=241.5,254.55
XS Rating Curve= 0 ,0
Exp/Cntr=0.3,0.1

Type RM Length L Ch R = 1 ,89703   ,215.49,221.43,220.87
XS GIS Cut Line= 3
2348957.06332546 611801.711202832348783.49543324 611580.80661267
2348609.92754096611452.822207242
#Sta/Elev= 30
       0   122.5   15.09  121.19   28.23   119.3   44.03  116.52   49.42  116.08
   57.25  116.62   77.37  115.39   97.03  115.06  108.51  113.86  139.24  113.18
  155.37  113.04  175.95  112.44  216.93  112.29  235.22  111.74  247.36  112.07
  288.99  111.26  298.36  110.79   309.7  110.72  348.89  108.58  351.34  107.19
  356.73   104.4  358.47  104.51  364.45  107.23  374.88  108.81  407.15  112.37
  434.05  114.05  449.49  116.19  458.63  116.98  492.25  118.35  496.59  118.34
#Mann= 4 ,-1 , 0
       0     .09       0  139.24    .045       0  351.34     .05       0
  364.45    .045       0
#XS Ineff= 2 , 0
       0  247.36   112.4               0
Permanent Ineff=
       F       F
Bank Sta=351.34,364.45
XS Rating Curve= 0 ,0
Exp/Cntr=0.3,0.1

Type RM Length L Ch R = 1 ,89481   ,209.64,251.48,276.3
XS GIS Cut Line= 4
2349084.16616458 611608.119994732348981.10957195611469.438900962
2348830.97774568611337.1193252652348640.13220377611360.020790279
#Sta/Elev= 30
       0  122.48   42.76  120.35    88.5     116  105.01  115.08  154.01  115.67
  170.32  116.63  180.35  116.73  193.43  113.94  196.04   113.1  213.85  107.55
  267.05  107.75  281.53  107.29  295.33  110.58  305.87  113.01  313.61   112.4
  328.56  107.12  338.96  103.55   343.2  107.14  344.23  108.04   346.7  108.68
  377.77  111.47  402.42  112.08  418.78  113.33  426.62  113.34  448.15  114.77
  462.15  115.06  471.97  114.73  492.21  114.88  509.05  115.28  559.35  114.37
#Mann= 6 ,-1 , 0
       0     .09       0    88.5    .045       0  196.04    .032       0
  295.33    .045       0  328.56     .05       0   343.2    .045       0
#XS Ineff= 2 , 0
       0     305   111.7               0
Permanent Ineff=
       F       F
Bank Sta=328.56,343.2
XS Rating Curve= 0 ,0
Exp/Cntr=0.3,0.1

Type RM Length L Ch R = 1 ,89230   ,414.79,442.1,446.76
XS GIS Cut Line= 4
2349097.32020813611594.8323009312349086.80094191611417.757986575
2349111.34589639611333.6038570112348913.23304963610884.781832561
#Sta/Elev= 30
       0  122.15   17.45  121.88   34.81  119.98   63.46  118.58  100.05  114.89
  126.29  115.28  154.14  114.53  177.39  115.04  218.61   114.5  234.94  113.09
  265.05  112.54  278.29  111.42     355  111.54  377.61  107.54  385.15  105.68
  394.21  103.45  396.37   104.5  401.63  105.63  408.32  107.42  417.68  108.38
  438.54  107.92  480.19   108.6  502.11  106.76  521.58  106.75     594   108.8
  616.96  110.83  685.22   114.8   719.6  119.23  733.24   121.1  755.65  121.72
#Mann= 5 ,-1 , 0
       0     .09       0  100.05    .045       0  385.15     .05       0
  401.63    .045       0   719.6     .09       0
#XS Ineff= 2 , 0
       0                     417       0     108
Permanent Ineff=
       F       T
Bank Sta=385.15,401.63
XS Rating Curve= 0 ,0
Exp/Cntr=0.3,0.1

Type RM Length L Ch R = 1 ,88788   ,420.43,426.52,430.48
XS GIS Cut Line= 4
2349543.85416669611385.4375000152349529.64062501611314.255208328
  2349424.890625610934.8489583282349405.17708333610849.473958328
#Sta/Elev= 30
       0   109.7    3.86  109.49   15.89  109.58   58.87  108.71   69.08  108.61
   95.36  107.05  133.56  106.11  158.48  105.04  171.47  105.53  193.58  105.32
  204.89  105.53  217.53  105.23  264.58  105.14  277.14  104.84  282.53  104.44
   286.1  103.81  292.25  102.73   311.8  103.82  341.46  105.46  351.58  104.97
  378.77  105.01  396.29  104.14  415.61  104.35  433.65  104.84   457.2  105.76
   489.3  106.04  504.67  108.17  523.33  110.16  540.41  112.75  553.81  113.61
#Mann= 4 ,-1 , 0
       0    .045       0   58.87    .075       0   286.1     .05       0
   311.8     .09       0
Bank Sta=286.1,311.8
XS Rating Curve= 0 ,0
Exp/Cntr=0.3,0.1

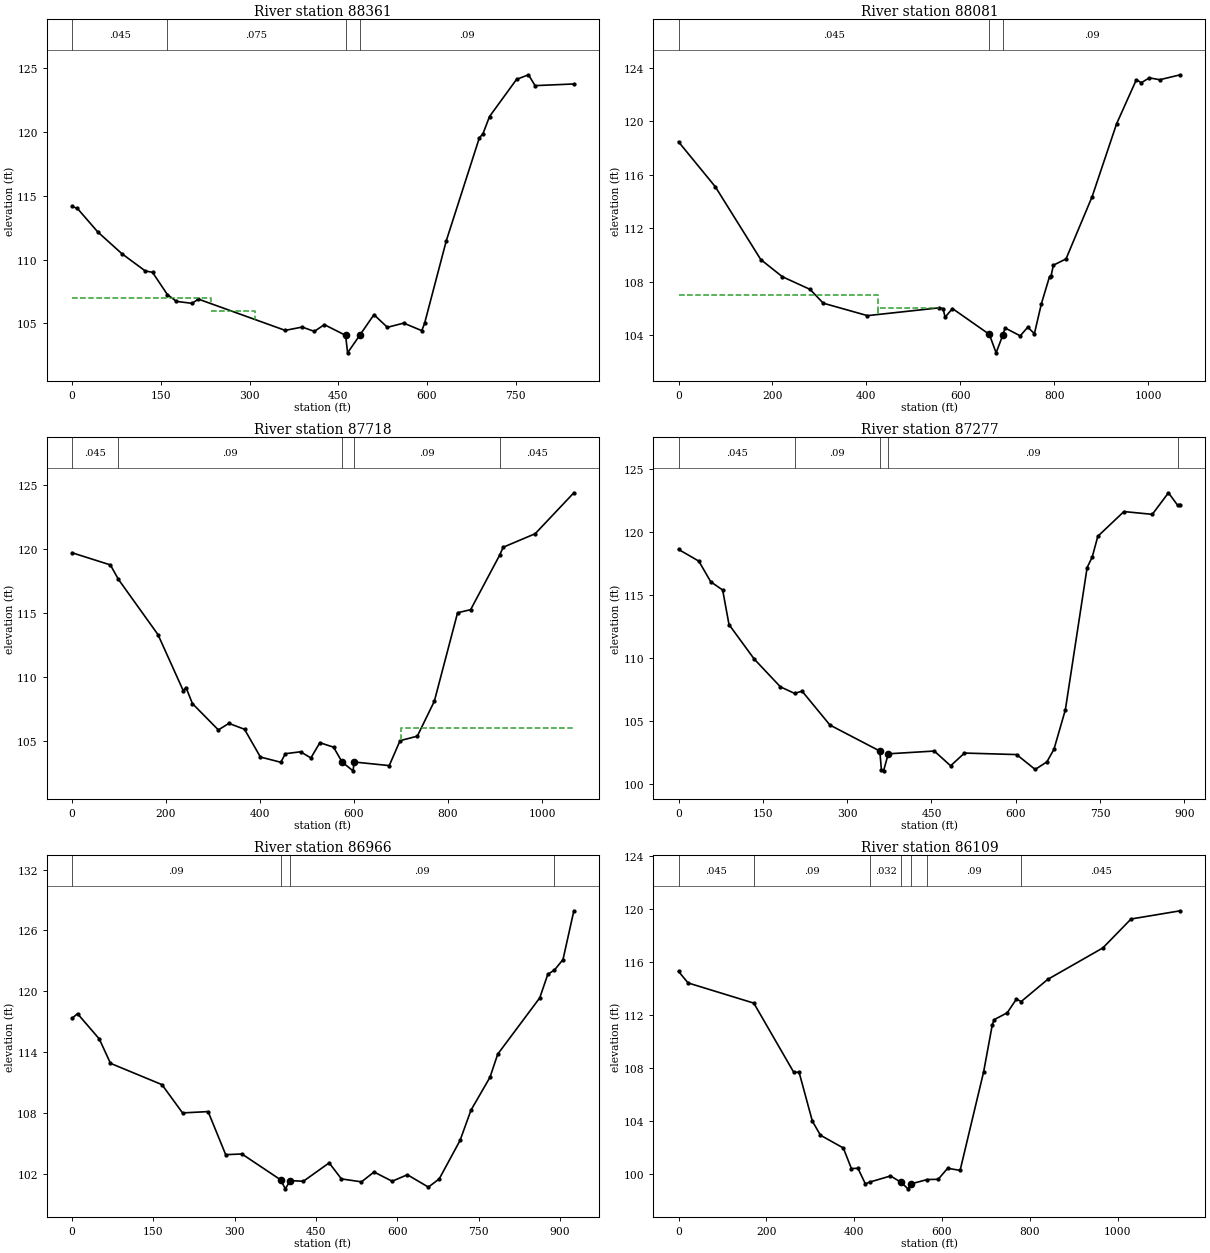
Type RM Length L Ch R = 1 ,88361   ,291.71,280.02,254.46
XS GIS Cut Line= 3
2350023.02801368611517.3689113712349886.88114615611050.782250851
2349820.22590894610694.814920172
#Sta/Elev= 30
       0  114.17    8.91  114.02   43.52  112.17   84.18  110.47  123.65  109.12
  135.96  109.01  161.07  107.27  176.46  106.73  202.81  106.58  213.51  106.91
  360.25  104.46  388.97  104.72  409.55  104.38  426.44  104.91  462.34  104.07
  465.71   102.7  486.04  104.06  510.26  105.69  533.02   104.7  560.56  105.03
  591.08  104.44  595.81     105  632.67   111.5  688.39  119.54  694.63  119.88
  705.66  121.22  751.33  124.13   771.5  124.49  782.62  123.64   848.2  123.77
#Mann= 4 ,-1 , 0
       0    .045       0  161.07    .075       0  462.34     .05       0
  486.04     .09       0
#XS Ineff= 2 ,-1
       0     235     107     235     310     106
Permanent Ineff=
       T       T
Bank Sta=462.34,486.04
XS Rating Curve= 0 ,0
Exp/Cntr=0.3,0.1

Type RM Length L Ch R = 1 ,88081   ,388.97,363.03,358.88
XS GIS Cut Line= 4
2350432.13613224 611520.089802342350129.08024405610921.345720246
 2349998.7733939610740.7284884452349837.68130992610673.556036308
#Sta/Elev= 30
       0  118.45   78.36  115.09  175.11  109.65  220.98  108.37  280.15  107.42
  308.11  106.39  402.22  105.46  554.22  106.04   563.1  105.99  567.57  105.34
  583.14  105.99  661.72  104.06  676.11  102.68  690.87  104.05  695.17  104.54
  727.45  103.95  743.65   104.6  757.64  104.11  772.37  106.33  789.79  108.37
  793.14  108.44   798.1  109.23  824.97   109.7  880.62  114.36  932.65   119.8
  974.71  123.09  985.27  122.87 1002.58  123.23 1024.57  123.09 1068.32  123.46
#Mann= 3 ,-1 , 0
       0    .045       0  661.72     .05       0  690.87     .09       0
#XS Ineff= 2 ,-1
       0     425     107     425  554.22  106.04
Permanent Ineff=
       T       T
Bank Sta=661.72,690.87
XS Rating Curve= 0 ,0
Exp/Cntr=0.3,0.1

Type RM Length L Ch R = 1 ,87718   ,354.87,441.09,394.49
XS GIS Cut Line= 3
2350887.38317978611098.7041054672350572.50147633610896.151700318
2350131.14634876610361.279135957
#Sta/Elev= 30
       0  119.69    81.5  118.74   98.67  117.61  182.83  113.29  236.45  108.92
  242.58  109.15  256.09   107.9  311.27  105.84  333.81  106.35  366.97  105.89
  400.79  103.72  444.23  103.31  453.98  103.98  486.22  104.13  508.26  103.65
  527.36  104.84  556.51  104.49   574.6  103.33  597.82  102.64  600.54  103.33
  674.97  103.05     698     105  734.68  105.35  770.92  108.08  820.42     115
  848.19  115.24  910.03  119.51  917.33  120.12  985.58  121.18 1067.86  124.38
#Mann= 5 ,-1 , 0
       0    .045       0   98.67     .09       0   574.6     .05       0
  600.54     .09       0  910.03    .045       0
#XS Ineff= 2 , 0
       0                     700       0     106
Permanent Ineff=
       F       F
Bank Sta=574.6,600.54
XS Rating Curve= 0 ,0
Exp/Cntr=0.3,0.1

Type RM Length L Ch R = 1 ,87277   ,327.77,310.51,243.08
BEGIN DESCRIPTION:
Surveyed Section
END DESCRIPTION:
XS GIS Cut Line= 6
2350985.20485936610899.2983739082350835.95160003610675.039299995
2350806.97040004610624.8993999962350789.43490005610596.314300001
2350747.18750003610521.1469000132350488.57171668610158.111032113
#Sta/Elev= 30
       0  118.64    36.1  117.71   57.35  116.07   78.51  115.42    89.8  112.68
  134.55  109.95   181.3  107.74  206.61  107.22   219.8   107.4 269.431  104.71
 358.135  102.65 360.927  101.18  364.81  101.08   373.2  102.43  455.11  102.65
  484.14  101.48  508.82  102.49   601.6  102.37  634.55  101.19  655.41  101.79
     668  102.79  688.28  105.92  727.01   117.2  736.05  118.03  746.05  119.68
  792.51  121.64  842.98  121.42  871.77  123.13  887.85  122.15  892.85   122.2
#Mann= 5 ,-1 , 0
       0    .045       0  206.61     .09       0 358.135     .05       0
   373.2     .09       0  887.85    .045       0
Bank Sta=358.135,373.2
XS Rating Curve= 0 ,0
Exp/Cntr=0.3,0.1

Type RM Length L Ch R = 1 ,86966   ,835.1,857.38,798.14
XS GIS Cut Line= 4
2351331.34311037610643.4570579682351045.79933432610422.853842363
2350989.67705868610400.4049320972350631.54186378610045.239863336
#Sta/Elev= 30
       0  117.32   10.03  117.78   50.16  115.29   70.88  112.88   165.8  110.78
  203.81  107.99  250.97  108.12   283.4  103.87  313.31  103.94  384.71  101.39
  393.37   100.5  402.46  101.31  426.74  101.25  474.25  103.06  496.88  101.48
  533.87  101.19  557.01  102.16  590.52  101.25  618.54  101.89  657.29  100.67
  677.28  101.48  715.76  105.28  735.86  108.26  770.87   111.5  785.25  113.79
  862.75  119.34  877.72  121.68  889.65  122.07  905.61  123.12  925.66  127.93
#Mann= 4 ,-1 , 0
       0     .09       0  384.71     .05       0  402.46     .09       0
  889.65    .045       0
Bank Sta=384.71,402.46
XS Rating Curve= 0 ,0
Exp/Cntr=0.3,0.1

Type RM Length L Ch R = 1 ,86109   ,544.26,574.78,545.25
XS GIS Cut Line= 3
2351809.16439162609898.5073438882351004.91617675609460.420917884
2350785.79912786609401.874201149
#Sta/Elev= 30
       0   115.3   21.72  114.43  171.39  112.91  262.26   107.7  274.49   107.7
  304.75  104.01  323.23  102.95  375.24  101.99  393.58  100.44  408.54  100.46
  425.33   99.29  435.46   99.42  482.65   99.88  507.48   99.39  522.27   98.91
  530.14   99.29  566.17   99.61  591.22   99.63  612.82  100.46  641.16   100.3
  694.68  107.72  714.47  111.28  718.58  111.66  748.44  112.18  769.32  113.21
   780.3  113.03  840.76   114.7  966.25  117.07 1030.37  119.25 1142.63  119.87
#Mann= 7 ,-1 , 0
       0    .045       0  171.39     .09       0  435.46    .032       0
  507.48    .032       0  530.14    .032       0  566.17     .09       0
   780.3    .045       0
Bank Sta=507.48,530.14
XS Rating Curve= 0 ,0
Exp/Cntr=0.3,0.1

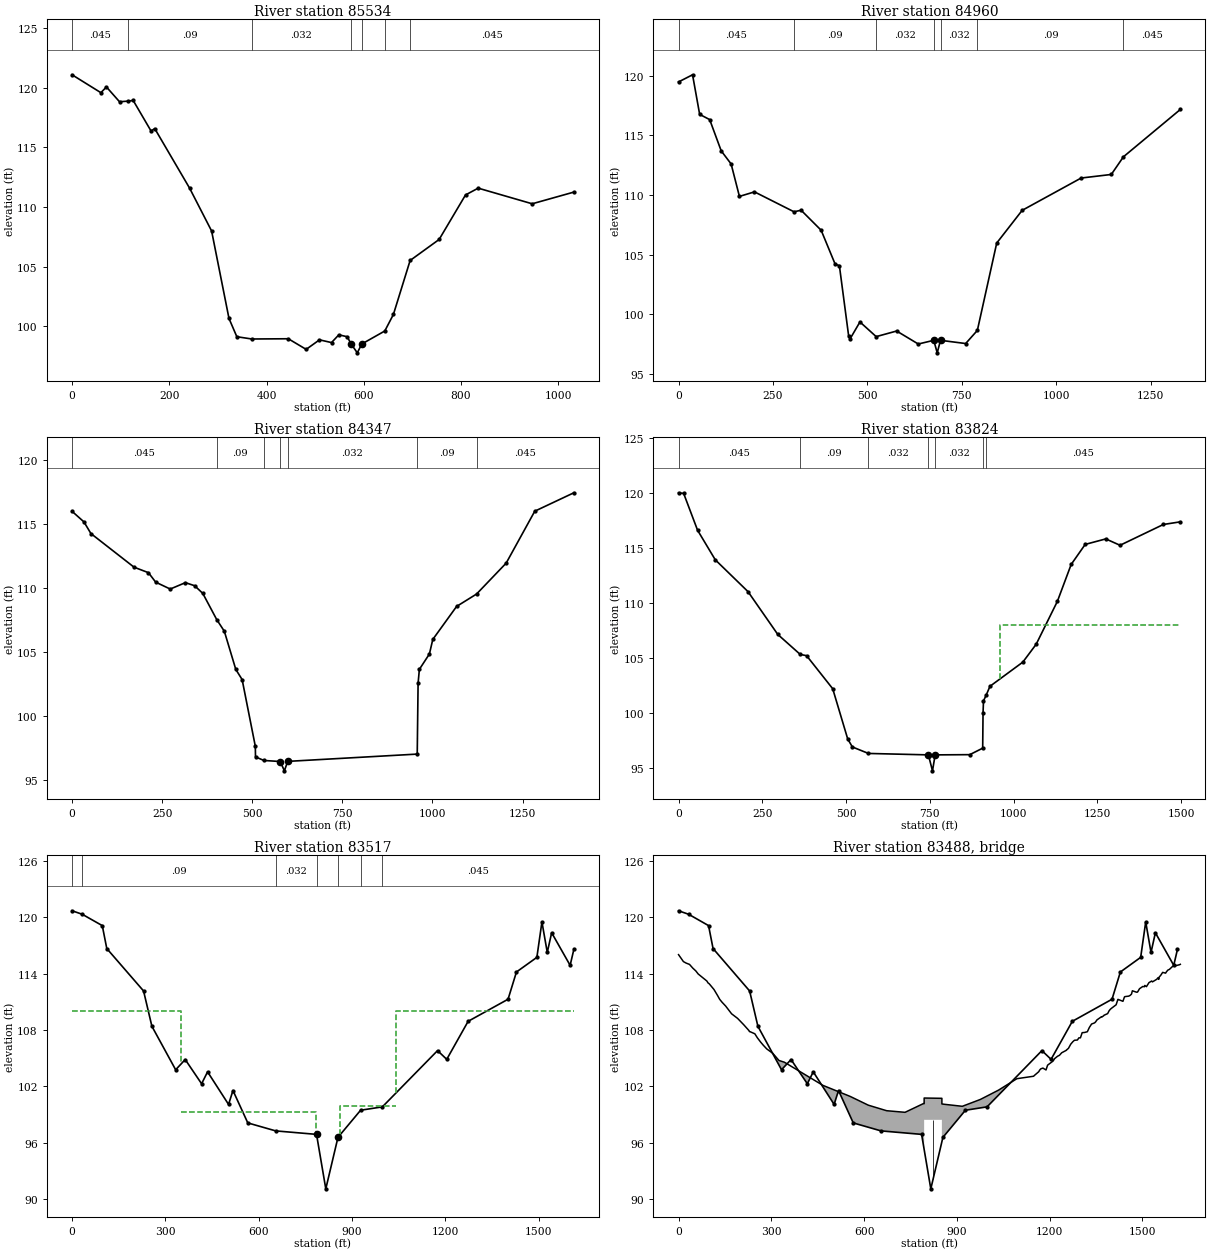
Type RM Length L Ch R = 1 ,85534   ,561.05,573.95,554.78
XS GIS Cut Line= 4
2352019.85724008609514.7453699562351794.11490248609266.428798586
2351363.95421085609054.5113990462351146.98686801609051.973577842
#Sta/Elev= 30
       0  121.07   59.28  119.57   70.68  120.05   97.59  118.81  114.56  118.86
   125.7  118.92  162.43  116.36  170.06  116.56  241.74  111.57  287.02  107.98
  322.76  100.65   338.9   99.12   369.8   98.93  444.77   98.95   481.5   98.06
  508.92   98.86  533.63   98.63   548.7   99.28  565.92   99.12  573.72   98.53
  586.64   97.77  595.86   98.51  643.21    99.6  660.96  100.99  695.33  105.51
  754.99  107.27  809.26     111  835.32  111.57  946.41  110.26  1032.1  111.24
#Mann= 7 ,-1 , 0
       0    .045       0  114.56     .09       0   369.8    .032       0
  573.72    .032       0  595.86    .032       0  643.21     .09       0
  695.33    .045       0
Bank Sta=573.72,595.86
XS Rating Curve= 0 ,0
Exp/Cntr=0.3,0.1

Type RM Length L Ch R = 1 ,84960   ,511.08,613.76,538.94
XS GIS Cut Line= 4
2352565.40122265608860.0925908832352106.51034401608795.307848617
2351679.98104912608623.1995366222351489.36274673608265.637768537
#Sta/Elev= 30
       0  119.48   37.11  120.08   55.93  116.76    82.5  116.32  112.95   113.7
  139.24   112.6  161.21  109.88   201.1  110.26  305.71  108.59  324.57  108.72
  377.61  107.04   414.9  104.18  425.85  104.08  450.35   98.19  454.35   97.94
  480.31   99.35  523.33   98.12  577.48   98.59  634.76    97.5  675.74   97.81
   684.9   96.76  693.65   97.81  760.25   97.54  791.17   98.64  842.47  105.97
  909.81  108.71 1065.94  111.42  1145.8  111.72 1177.92   113.2 1328.58  117.17
#Mann= 7 ,-1 , 0
       0    .045       0  305.71     .09       0  523.33    .032       0
  675.74    .032       0  693.65    .032       0  791.17     .09       0
 1177.92    .045       0
Bank Sta=675.74,693.65
XS Rating Curve= 0 ,0
Exp/Cntr=0.3,0.1

Type RM Length L Ch R = 1 ,84347   ,392.39,522.73,591.02
XS GIS Cut Line= 5
2352614.31206246608758.5085389612352402.27891076 608413.39633204
2352235.59157799608299.5610803962351932.53128956608133.064995974
2351493.12511902 608152.76659973
#Sta/Elev= 30
       0  115.99   33.03  115.16   52.33  114.25  171.98  111.62  211.94  111.19
  231.99  110.45  272.43  109.91  314.52  110.41  340.12  110.17  362.77  109.57
  401.46  107.52  422.52  106.61   454.4  103.62  471.94  102.83  508.55   97.61
  509.04   96.78  532.54    96.5  577.62   96.42  589.22   95.69  598.37   96.43
  957.85      97  960.26  102.55  963.81  103.63  991.64  104.83 1001.06  105.97
 1067.11  108.55 1122.51  109.52 1204.72  111.94 1284.05     116 1392.52  117.44
#Mann= 7 ,-1 , 0
       0    .045       0  401.46     .09       0  532.54    .032       0
  577.62    .032       0  598.37    .032       0  957.85     .09       0
 1122.51    .045       0
Bank Sta=577.62,598.37
XS Rating Curve= 0 ,0
Exp/Cntr=0.3,0.1

Type RM Length L Ch R = 1 ,83824   ,291.93,306.71,311.48
XS GIS Cut Line= 6
2352779.85644333608713.3600714362352592.90339963607996.500791907
2352570.45448938607975.9226241562352478.78810583607710.277186111
2352465.51923215607490.7135867332352347.18362962607298.708089143
#Sta/Elev= 30
       0  120.02    15.3  119.96   56.77  116.62  109.71  113.93  207.39  111.04
  296.31  107.15   363.1  105.34   382.3  105.22  460.22  102.22  504.98   97.66
  518.84   96.93  566.89   96.34  745.82   96.21  758.11   94.76  766.05   96.21
  869.43   96.23  907.96   96.82  909.01  100.03  910.36  101.11  919.14  101.69
  929.68  102.44 1027.92  104.64 1067.62  106.26 1130.95  110.16  1172.1  113.51
 1213.94  115.33 1275.46  115.83 1317.95  115.25 1447.29  117.14 1497.94  117.38
#Mann= 7 ,-1 , 0
       0    .045       0   363.1     .09       0  566.89    .032       0
  745.82    .032       0  766.05    .032       0  907.96     .09       0
  919.14    .045       0
#XS Ineff= 2 , 0
       0                     960       0     108
Permanent Ineff=
       F       F
Bank Sta=745.82,766.05
XS Rating Curve= 0 ,0
Exp/Cntr=0.5,0.3

Type RM Length L Ch R = 1 ,83517   ,68.36,53.08,62.92
BEGIN DESCRIPTION:
Surveyed Section
END DESCRIPTION:
XS GIS Cut Line= 6
2353083.03794028608613.8458240182352842.34900004     607857.7755
2352830.96240005607797.983500004    2352801.8633607731.275999993
2352712.63092101607605.5156049132352353.44835688607214.530417889
#Sta/Elev= 30
       0  120.68   32.59  120.31   97.13   119.1  111.63  116.66  229.93  112.14
  256.68  108.38  333.08  103.75  363.83  104.84  416.53  102.26   435.7  103.53
  503.17  100.06  517.36  101.54  565.05   98.09 654.804   97.24 786.073   96.87
 815.856   91.07 854.992   96.55 927.783   99.44  997.76    99.8 1175.18  105.79
 1204.76  104.86 1273.55  108.91  1401.9  111.26 1428.86  114.16 1494.56  115.72
 1510.84  119.49 1528.01  116.25  1542.1  118.34 1601.51  114.87  1613.5  116.57
#Mann= 7 ,-1 , 0
       0    .045       0   32.59     .09       0 654.804    .032       0
 786.073    .032       0 854.992    .032       0 927.783    .035       0
  997.76    .045       0
#XS Ineff= 4 ,-1
       0     350     110     350   784.3   99.22   861.7    1040   99.86
    1040    1620     110
Permanent Ineff=
       F       F       F       F
Bank Sta=786.073,854.992
XS Rating Curve= 0 ,0
Exp/Cntr=0.5,0.3

Type RM Length L Ch R = 3 ,83488   ,,,
BEGIN DESCRIPTION:
1140 Greene Co. / 1705 Wayne Co.
END DESCRIPTION:
Bridge Culvert--1,0,-1,-1, 0
Deck Dist Width WeirC Skew NumUp NumDn MinLoCord MaxHiCord MaxSubmerge Is_Ogee
12.98,27,2.6,0, 134, 134, , , 0.98, 0, 1,1,,
       0    3.35   15.75   24.53   35.47   46.23   56.02   63.54   76.01    91.6
   95.37   99.41  114.55  126.34  133.12  140.81  152.23  161.65  171.61  186.65
  191.02  207.48  210.67  227.55   229.5  231.62  246.79  254.79  265.69  273.92
  285.32  295.19  304.83  318.52  324.74  342.58  466.83 555.241 613.683 672.958
 732.544 791.373   794.3   794.3 850.517   851.7   851.7 860.616  917.76 976.112
1035.3141094.231  1146.9 1148.28    1151 1165.15 1167.35 1171.15 1178.27 1188.45
 1193.56 1207.46 1211.24 1216.37 1225.78 1231.85 1235.96 1239.18 1254.03 1254.61
 1254.84 1260.96 1268.48 1274.95 1280.35 1290.01  1294.7 1299.71 1302.01 1305.36
 1312.88 1322.11 1325.58 1328.67 1335.78 1345.28 1348.57 1353.21  1367.9 1369.35
 1375.11 1375.77 1387.74 1392.58 1396.66 1400.31 1414.83 1415.16 1420.83 1421.55
 1437.19 1442.06  1443.7 1455.86 1460.47  1464.9 1467.71 1481.12 1484.18  1485.1
  1490.8 1501.48 1506.49 1507.99 1513.18 1521.42 1530.15 1532.64 1546.85 1550.11
 1553.17 1554.35 1559.21 1565.64 1575.25    1577 1581.97 1587.47 1597.55 1604.12
 1604.71 1606.63 1620.63 1622.79
  116.01  115.85  115.27  115.11  114.97  114.57  114.27  113.95  113.61   113.2
     113   112.9   112.3  111.65  111.25  110.94  110.54  110.14  109.71  109.34
  109.22  108.65  108.55  107.93  107.81   107.8  107.58  107.16  106.69  106.37
  105.97  105.73   105.5  104.98  104.74  104.55  102.09  100.91   99.98   99.39
   99.22  100.14  100.14  100.74  100.72  100.71  100.11  100.07   99.86  100.59
  101.59   102.8  103.05  103.06  103.15  103.55  103.69  103.84  103.93  103.73
  104.24  104.59  104.68  104.94  105.19  105.29  105.44  105.56  105.83  105.83
  105.86  106.03  106.48  106.73  106.89  106.92  107.15  107.15  107.36   107.7
  107.72   107.8  108.05  108.26  108.62  108.74  108.84  109.06   109.4  109.37
  109.51  109.55  109.73  110.04   110.2   110.3  110.67  110.67  111.24  111.24
  111.04   111.5  111.54  111.59  111.67  111.81  112.16  112.01  112.02  112.06
  112.38  112.62  112.59  112.73   112.6  113.03   113.2  113.11  113.39  113.54
  113.38  113.62   113.8  114.12  114.04  114.14  114.35  114.44  114.75  114.82
  114.82  114.82  114.94  114.98
                                                                                
                                                                                
                                                                                
                                                                                
                       0   98.42   98.42   98.42       0
                                                                                
                                                                                
                                                                                
                                                                                
                                                                                
                                                                                
                                                                                
                                                                                
                                
       0    3.35   15.75   24.53   35.47   46.23   56.02   63.54   76.01    91.6
   95.37   99.41  114.55  126.34  133.12  140.81  152.23  161.65  171.61  186.65
  191.02  207.48  210.67  227.55   229.5  231.62  246.79  254.79  265.69  273.92
  285.32  295.19  304.83  318.52  324.74  342.58  466.83 555.241 613.683 672.958
 732.544 791.373   797.3   797.3 850.517   854.7   854.7 860.616  917.76 976.112
1035.3141094.231  1146.9 1148.28    1151 1165.15 1167.35 1171.15 1178.27 1188.45
 1193.56 1207.46 1211.24 1216.37 1225.78 1231.85 1235.96 1239.18 1254.03 1254.61
 1254.84 1260.96 1268.48 1274.95 1280.35 1290.01  1294.7 1299.71 1302.01 1305.36
 1312.88 1322.11 1325.58 1328.67 1335.78 1345.28 1348.57 1353.21  1367.9 1369.35
 1375.11 1375.77 1387.74 1392.58 1396.66 1400.31 1414.83 1415.16 1420.83 1421.55
 1437.19 1442.06  1443.7 1455.86 1460.47  1464.9 1467.71 1481.12 1484.18  1485.1
  1490.8 1501.48 1506.49 1507.99 1513.18 1521.42 1530.15 1532.64 1546.85 1550.11
 1553.17 1554.35 1559.21 1565.64 1575.25    1577 1581.97 1587.47 1597.55 1604.12
 1604.71 1606.63 1620.63 1622.79
  116.01  115.85  115.27  115.11  114.97  114.57  114.27  113.95  113.61   113.2
     113   112.9   112.3  111.65  111.25  110.94  110.54  110.14  109.71  109.34
  109.22  108.65  108.55  107.93  107.81   107.8  107.58  107.16  106.69  106.37
  105.97  105.73   105.5  104.98  104.74  104.55  102.09  100.91   99.98   99.39
   99.22  100.14  100.14  100.74  100.72   100.7   100.1  100.07   99.86  100.59
  101.59   102.8  103.05  103.06  103.15  103.55  103.69  103.84  103.93  103.73
  104.24  104.59  104.68  104.94  105.19  105.29  105.44  105.56  105.83  105.83
  105.86  106.03  106.48  106.73  106.89  106.92  107.15  107.15  107.36   107.7
  107.72   107.8  108.05  108.26  108.62  108.74  108.84  109.06   109.4  109.37
  109.51  109.55  109.73  110.04   110.2   110.3  110.67  110.67  111.24  111.24
  111.04   111.5  111.54  111.59  111.67  111.81  112.16  112.01  112.02  112.06
  112.38  112.62  112.59  112.73   112.6  113.03   113.2  113.11  113.39  113.54
  113.38  113.62   113.8  114.12  114.04  114.14  114.35  114.44  114.75  114.82
  114.82  114.82  114.94  114.98
                                                                                
                                                                                
                                                                                
                                                                                
                       0   98.42   98.42   98.42       0
                                                                                
                                                                                
                                                                                
                                                                                
                                                                                
                                                                                
                                                                                
                                                                                
                                
Pier Skew, UpSta & Num, DnSta & Num=  ,823, 4 ,826, 4 , 3 , 3 , 0 ,,
       1       1     1.3     1.3
    90.4   97.12   97.12   98.42
       1       1     1.3     1.3
    90.4   97.12   97.12   98.42
BR Coef=-1 , 1 , 0 ,0.9, 0 ,,,0.8,0,1.2,0,
WSPro=,,,, 1 ,,,, 0 ,,,, 0 ,,,,-1 ,-1 ,-1 , 0 , 0 , 0 , 0 , 0
BC Design=,, 0 ,, 0 ,,,,,,
BC Use User HTab Curves=0
BC User HTab FreeFlow(D)= 0

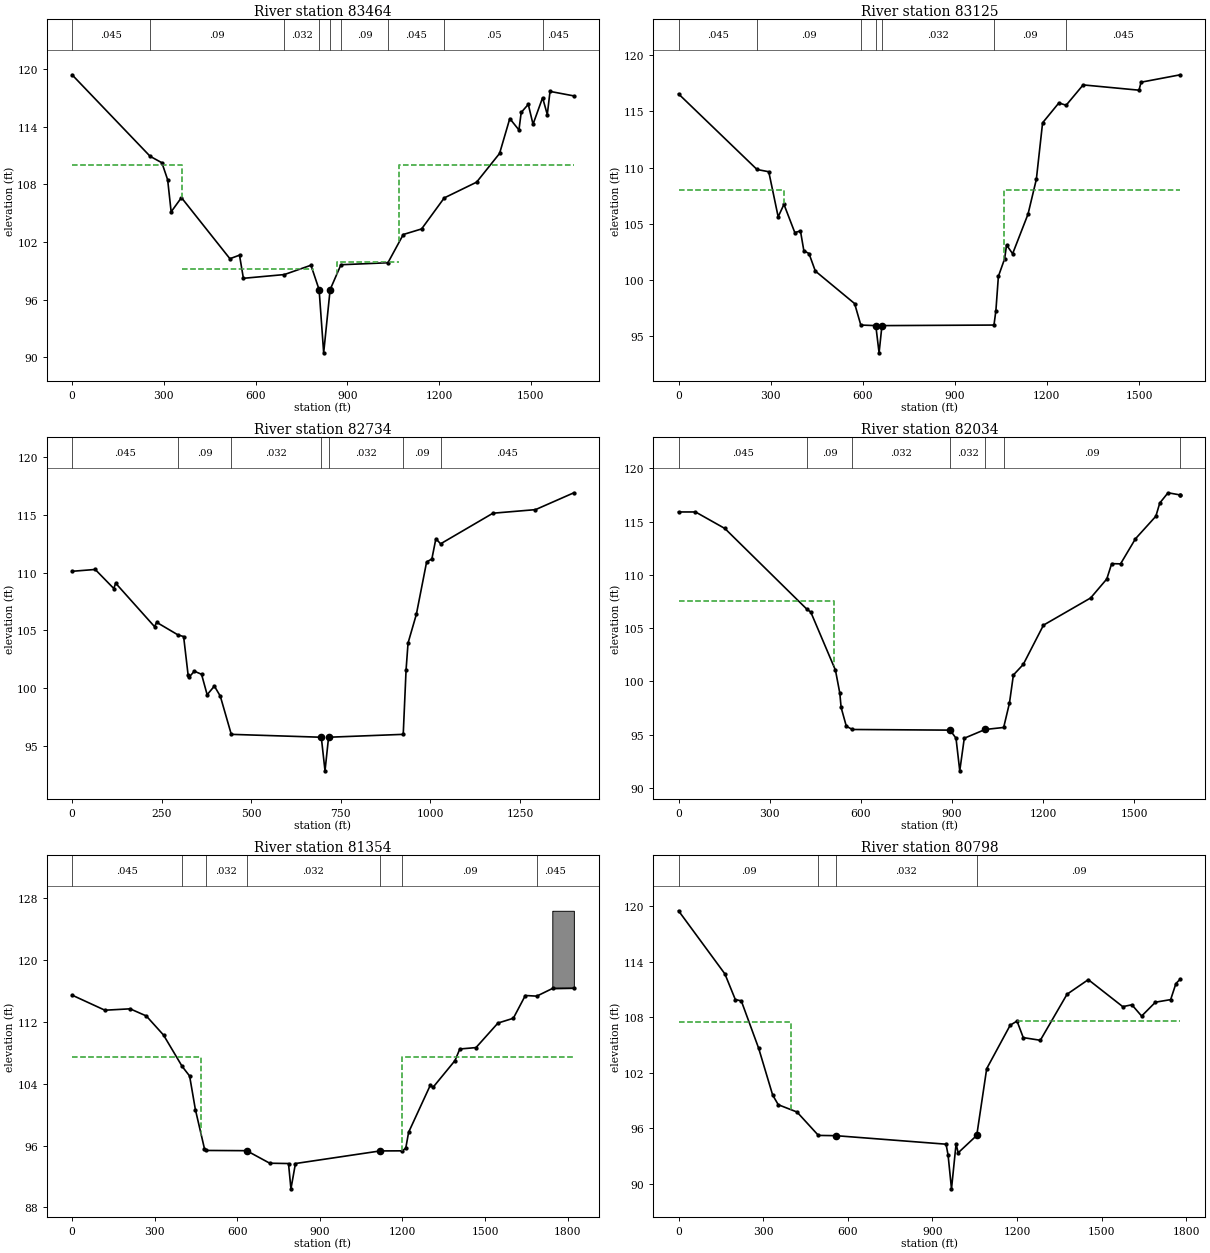
Type RM Length L Ch R = 1 ,83464   ,187.58,338.55,268.71
BEGIN DESCRIPTION:
Surveyed Section
END DESCRIPTION:
XS GIS Cut Line= 6
2353152.25541359608591.396913767    2352925.2586607885.452399999
2352894.98439999607827.207400009    2352844.7718607684.225600004
2352755.65799899607562.4885268962352396.47543487607173.374082416
#Sta/Elev= 30
       0   119.4  255.29  110.91  293.73  110.24  312.52  108.47  323.97  105.13
  357.59  106.61  516.09  100.25  547.46  100.62  560.19   98.21 694.158    98.6
 781.096   99.57 807.733   97.03  822.67   90.45 843.746   97.03  879.09  99.622
 1032.81   99.83 1082.97  102.77 1142.86  103.35 1216.91  106.58 1322.73  108.22
 1397.82  111.21 1431.22  114.84 1461.18  113.65 1468.54  115.48 1491.68  116.32
 1507.17  114.25 1538.49  117.01 1553.85  115.26 1562.78  117.67 1640.71   117.2
#Mann= 9 ,-1 , 0
       0    .045       0  255.29     .09       0 694.158    .032       0
 807.733    .032       0 843.746    .032       0  879.09     .09       0
 1032.81    .045       0 1216.91     .05       0 1538.49    .045       0
#XS Ineff= 4 ,-1
       0     360     110     360   787.3   99.22   864.7    1070   99.86
    1070    1650     110
Permanent Ineff=
       F       F       F       F
Bank Sta=807.733,843.746
XS Rating Curve= 0 ,0
Exp/Cntr=0.5,0.3

Type RM Length L Ch R = 1 ,83125   ,363.3,391.46,271.98
XS GIS Cut Line= 3
2353220.05400169608547.8156905322353094.26239541 607474.56362839
2353046.98487619606922.470859796
#Sta/Elev= 30
       0  116.55  255.67  109.83  293.97  109.63  324.59  105.62  343.45  106.73
   378.8  104.22  397.17  104.37  408.29   102.6  424.94  102.36  445.65   100.8
  573.62   97.91  593.81      96  642.61   95.95  653.31   93.53  662.71   95.95
 1027.61      96  1033.9   97.29 1041.99  100.33 1062.43   101.9 1068.55  103.12
 1088.36  102.34 1138.51  105.86 1165.68  108.96    1186  113.98 1239.12  115.75
 1262.65  115.54  1318.1  117.35 1500.09  116.88 1506.89  117.59 1634.71  118.25
#Mann= 7 ,-1 , 0
       0    .045       0  255.67     .09       0  593.81    .032       0
  642.61    .032       0  662.71    .032       0 1027.61     .09       0
 1262.65    .045       0
#XS Ineff= 2 , 0
       0     345     108    1060       0     108
Permanent Ineff=
       F       F
Bank Sta=642.61,662.71
XS Rating Curve= 0 ,0
Exp/Cntr=0.3,0.1

Type RM Length L Ch R = 1 ,82734   ,747.06,700.47,614.31
XS GIS Cut Line= 4
2353660.25155999608393.5584264992353592.52885874608126.429993689
2353321.63805361607475.5395869172353208.76688477607069.203379244
#Sta/Elev= 30
       0  110.12   64.56  110.28  116.38  108.63  121.67  109.09  230.01  105.33
  236.09   105.7  295.61  104.61  311.26  104.47  323.86  101.12  326.61  100.95
  341.11  101.47  361.31   101.2  376.91   99.43  397.08  100.18  413.59   99.31
  444.26      96  695.41   95.75  705.76   92.84  715.74   95.75  924.03      96
  931.95  101.58  937.47  103.91  960.63  106.39  989.28  110.93 1003.94  111.19
 1015.11  112.94 1028.31   112.5 1174.32  115.15 1293.08  115.46 1400.13  116.92
#Mann= 7 ,-1 , 0
       0    .045       0  295.61     .09       0  444.26    .032       0
  695.41    .032       0  715.74    .032       0  924.03     .09       0
 1028.31    .045       0
Bank Sta=695.41,715.74
XS Rating Curve= 0 ,0
Exp/Cntr=0.3,0.1

Type RM Length L Ch R = 1 ,82034   ,620.02,679.28,730.02
XS GIS Cut Line= 4
2354676.09207922607814.1530933232354278.44241157607598.032634825
2353763.98821816607150.9251721652353276.48958607606978.906444207
#Sta/Elev= 30
       0   115.9   55.82   115.9  152.44  114.35  422.53  106.77  435.08  106.51
  516.36  101.05  530.73   98.89  534.94   97.56  552.06    95.8  571.79   95.49
  893.59   95.43  913.02   94.67  925.36   91.61  940.26   94.67 1008.84   95.49
 1069.85   95.68 1088.91   97.97 1101.82   100.6 1134.18  101.59  1200.8  105.28
 1355.97  107.83 1409.13  109.61 1425.26  111.05 1454.46  111.03  1503.4  113.38
 1570.65   115.5 1583.51  116.74 1610.73   117.7 1649.98   117.5 1651.14  117.47
#Mann= 7 ,-1 , 0
       0    .045       0  422.53     .09       0  571.79    .032       0
  893.59    .032       0 1008.84    .032       0 1069.85     .09       0
 1649.98    .045       0
#XS Ineff= 2 , 0
       0     510   107.5               0
Permanent Ineff=
       F       F
Bank Sta=893.59,1008.84
XS Rating Curve= 0 ,0
Exp/Cntr=0.3,0.1

Type RM Length L Ch R = 1 ,81354   ,421.31,556.29,574.76
XS GIS Cut Line= 6
2354796.48799263607501.876192972  2354656.311721607366.714859232
2354574.01972996607086.1507123412354398.63761853606849.969469011
 2354363.5611963606826.5851874952353735.49900585606049.600487724
#Sta/Elev= 30
       0  115.44  119.27  113.49  210.72  113.67  269.55  112.75  332.23  110.28
  399.86  106.23  426.91  104.99  447.83  100.66  480.76   95.61  487.11   95.37
  634.06   95.34  717.94   93.72   786.1   93.68  794.96   90.41  811.31   93.68
  1119.4   95.31 1199.77   95.32 1212.07   95.68 1222.38   97.72 1301.14   103.8
 1310.86  103.52 1390.73  106.98 1408.23  108.48 1467.06  108.66 1546.82  111.83
 1602.68  112.45 1646.22  115.39 1687.84  115.31  1745.5  116.31 1822.53  116.34
#Mann= 7 ,-1 , 0
       0    .045       0  399.86     .09       0  487.11    .032       0
  634.06    .032       0  1119.4    .032       0 1199.77     .09       0
 1687.84    .045       0
#XS Ineff= 2 , 0
       0     470   107.5    1200       0   107.5
Permanent Ineff=
       F       F
#Block Obstruct= 1 ,-1
 1744.22 1822.53 126.338
Bank Sta=634.06,1119.4
XS Rating Curve= 0 ,0
Exp/Cntr=0.3,0.1

Type RM Length L Ch R = 1 ,80798   ,836.96,658.63,563.75
XS GIS Cut Line= 6
2355041.04219165607347.6189289542354948.16823426606903.753316492
2354695.61799388606475.8209647092354683.92585309606431.390829831
2354588.05029885606279.3929999322354021.43930018606072.174721479
#Sta/Elev= 30
       0  119.52  164.42  112.69   201.3  109.92  222.56  109.77  284.19  104.64
  333.73   99.59  353.63   98.54  420.13   97.75  495.98   95.22  558.71   95.19
   948.6   94.27  955.74   93.11  967.91   89.44  984.11   94.29  991.68   93.34
 1057.46   95.22 1092.73  102.44 1176.03  107.14 1200.28  107.59 1222.36   105.8
  1282.9  105.51 1377.61  110.49 1452.97  112.07 1575.15  109.15 1607.61  109.35
  1642.1  108.13 1691.06  109.63 1745.05  109.91 1763.75  111.65 1779.34  112.14
#Mann= 4 ,-1 , 0
       0     .09       0  495.98    .032       0  558.71    .032       0
 1057.46     .09       0
#XS Ineff= 2 , 0
       0     400   107.5 1200.29       0  107.59
Permanent Ineff=
       F       F
Bank Sta=558.71,1057.46
XS Rating Curve= 0 ,0
Exp/Cntr=0.3,0.1