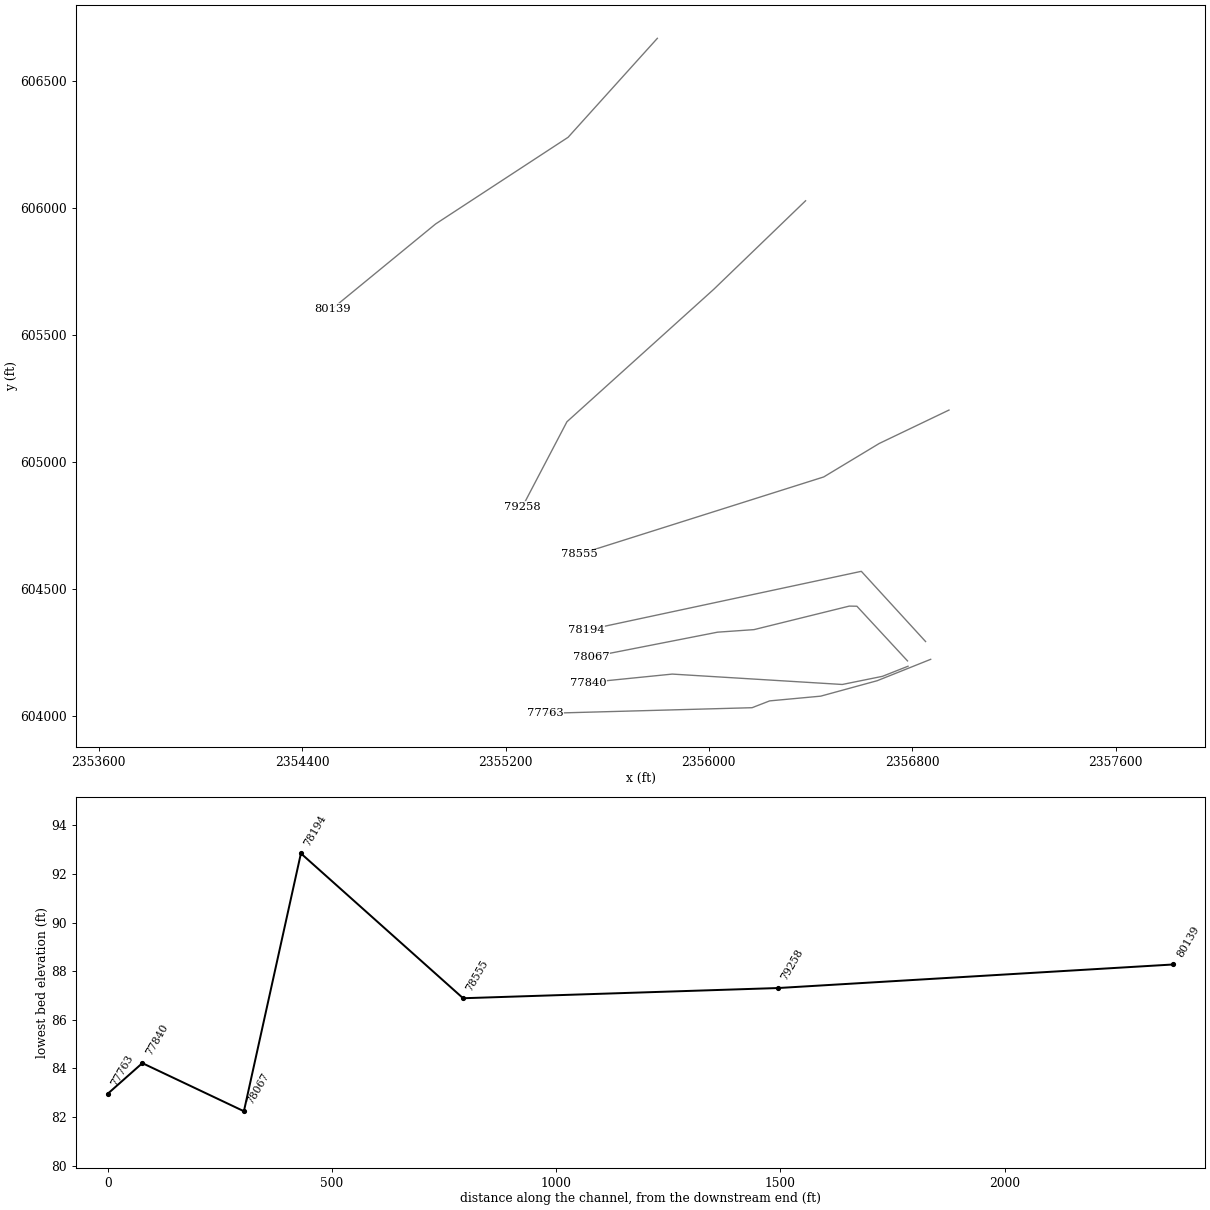
HEC-RAS study DTL_Bear_Creek.prj: DTL_Bear_Creek

--- DTL_Bear_Creek.g02 (geometry) --- (continued)

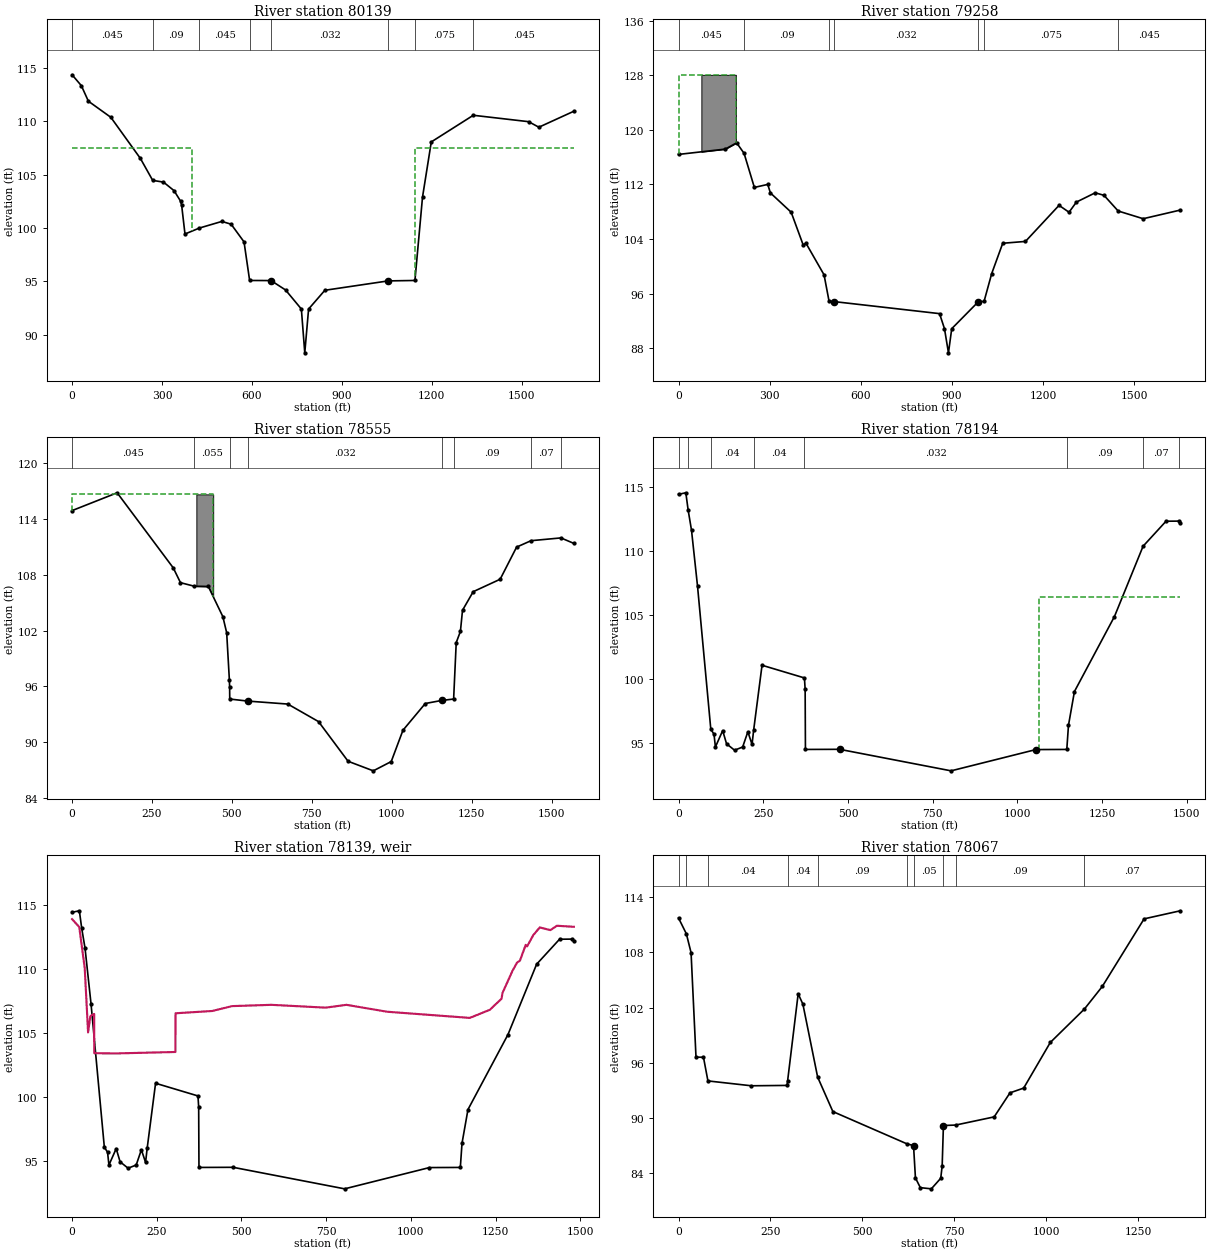
Type RM Length L Ch R = 1 ,80139   ,878.3,881.68,1009.56
XS GIS Cut Line= 4
2355797.27902268606666.6295438262355446.25343065606277.054571778
2354924.78395274605935.6440615952354518.07244292605601.878184795
#Sta/Elev= 30
       0  114.37   30.91  113.35   54.47  111.89  129.27  110.38   227.9  106.52
  268.98  104.46  304.88   104.3  340.06   103.5  361.82  102.52  365.52  102.13
  376.63   99.43  424.81   99.99  499.64  100.61  530.57  100.35  573.62   98.69
  592.29   95.07  663.67   95.06  712.08   94.18  764.86   92.39  776.22   88.28
  788.96   92.39  843.27   94.15  1054.5   95.03 1143.69   95.07 1168.96  102.89
 1198.23  108.07 1338.38  110.57 1522.87  109.97 1557.06  109.45 1673.81  110.95
#Mann= 8 ,-1 , 0
       0    .045       0  268.98     .09       0  424.81    .045       0
  592.29    .032       0  663.67    .032       0  1054.5    .032       0
 1143.69    .075       0 1338.38    .045       0
#XS Ineff= 2 , 0
       0     400   107.5    1145       0   107.5
Permanent Ineff=
       F       F
Bank Sta=663.67,1054.5
XS Rating Curve= 0 ,0
Exp/Cntr=0.3,0.1

Type RM Length L Ch R = 1 ,79258   ,884.72,702.28,651.51
XS GIS Cut Line= 4
2356380.44672814606027.0262539542356019.16832782605678.416964874
2355441.57657436605156.9474869972355266.78452927 604823.06712006
#Sta/Elev= 30
       0  116.41  153.88  117.19  191.24  118.11  215.75  116.57   249.6  111.57
  293.68  112.01  302.51  110.76  370.81  107.93  410.75  103.08  419.08  103.42
  479.08   98.75  495.71   94.84   513.2   94.82  859.28   93.06  875.51   90.85
  888.61   87.31  899.35   90.85  987.29   94.82  1005.7   94.84 1030.99   98.94
 1067.26  103.38 1142.11  103.65 1252.64  108.94 1285.56  107.93 1309.82  109.42
 1371.74  110.78 1400.66  110.41 1447.29  108.11 1529.66  106.98 1651.91  108.25
#Mann= 7 ,-1 , 0
       0    .045       0  215.75     .09       0  495.71    .032       0
   513.2    .032       0  987.29    .032       0  1005.7    .075       0
 1447.29    .045       0
#XS Ineff= 2 , 0
       0   188.7  128.09               0
Permanent Ineff=
       F       F
#Block Obstruct= 1 ,-1
   75.17   188.7 128.085
Bank Sta=513.2,987.29
XS Rating Curve= 0 ,0
Exp/Cntr=0.3,0.1

Type RM Length L Ch R = 1 ,78555   ,438.84,361.67,387.94
XS GIS Cut Line= 4
2356944.80257212605203.0667216932356670.14939475 605071.38369143
2356451.93180172604939.7006611532355488.76449458604634.948505402
#Sta/Elev= 30
       0  114.91  141.03  116.83   316.6  108.74  339.14  107.15  382.22  106.77
  426.25  106.74   471.7  103.49  483.65  101.76  492.15   96.63  492.85    95.9
  493.26   94.62  549.71    94.4  674.89   94.08  771.02   92.19  863.44   87.92
  942.28   86.89  998.42   87.89 1035.07   91.26 1104.92   94.14 1156.23   94.47
 1193.58   94.62 1201.71   100.7 1214.79   101.9 1221.39  104.18  1254.8  106.18
 1339.13  107.52 1390.55  110.98 1435.64  111.67 1529.19  111.97 1569.69  111.38
#Mann= 8 ,-1 , 0
       0    .045       0  382.22    .055       0  493.26    .032       0
  549.71    .032       0 1156.23    .032       0 1193.58     .09       0
 1435.64     .07       0 1529.19    .045       0
#XS Ineff= 2 , 0
       0  441.49  116.66               0
Permanent Ineff=
       F       F
#Block Obstruct= 1 ,-1
  388.82  441.49 116.657
Bank Sta=549.71,1156.23
XS Rating Curve= 0 ,0
Exp/Cntr=0.5,0.3

Type RM Length L Ch R = 1 ,78194   ,142.69,127.11,128.99
XS GIS Cut Line= 3
2356852.62218243604291.6657869522356599.89908364604568.081676275
2355517.92831695  604336.4188357
#Sta/Elev= 30
       0  114.43   21.52  114.55   28.44  113.19   38.32  111.62   55.99  107.28
   95.24    96.1  104.69   95.71  108.83   94.71  130.25   95.99  141.75   94.96
  165.35   94.46  189.29   94.71   204.6    95.9  216.94   94.91  221.58      96
  246.46  101.09  371.59   100.1  373.68   99.23  374.54   94.52  475.26   94.53
  804.43   92.85 1054.79   94.51 1145.94   94.52 1150.89    96.4 1168.51   99.04
 1286.58  104.89 1371.13  110.38 1438.81  112.33 1476.14  112.34 1481.03  112.16
#Mann= 8 ,-1 , 0
       0    .045       0   28.44     .04       0   95.24     .04       0
  221.58     .04       0  371.59    .032       0 1145.94     .09       0
 1371.13     .07       0 1476.14    .045       0
#XS Ineff= 2 , 0
       0                 1064.79       0 106.403
Permanent Ineff=
       F       F
Bank Sta=475.26,1054.79
XS Rating Curve= 0 ,0
Exp/Cntr=0.5,0.3

Type RM Length L Ch R = 5 ,78139   ,,,
IW Pilot Flow=0
#Inline Weir SE= 30
       0   113.9   21.23  113.28   37.34  110.08   47.28  105.06      54  106.33
    65.2   106.5    65.6  103.43  133.27  103.42   304.9  103.53  305.45  106.55
 413.758  106.73 472.354  107.11 588.216  107.21 748.638  106.99  809.62  107.21
 930.272  106.671173.876  106.191232.906  106.82  1267.7  107.69 1270.29  108.13
 1299.83  109.86 1313.39  110.51 1321.95  110.66 1338.92  111.89 1343.08  111.77
 1360.98  112.64 1380.32  113.25 1411.84  113.04 1431.02  113.38 1481.03   113.3
IW Dist,WD,Coef,Skew,MaxSub,Min_El,Is_Ogee,SpillHt,DesHd
53,13,2.6,0,0.98,, 0 ,,,1,1,

Type RM Length L Ch R = 1 ,78067   ,316.91,226.47,214.73
BEGIN DESCRIPTION:
Surveyed Section
END DESCRIPTION:
XS GIS Cut Line= 6
2356781.54381089604215.322350875    2356582.4223604430.620100006
2356552.41390005604431.1575000142356177.61089998604338.547600016
2356034.14839999604328.4794999962355537.67230907604231.117544547
#Sta/Elev= 30
       0  111.75   21.29  110.03   34.06  107.98    47.5   96.59    67.8   96.58
   79.92      94  198.04   93.47   295.2   93.51  296.59      94  325.28  103.49
   338.1  102.37  378.22   94.42 419.638   90.66  620.27  87.157 638.997   86.95
 644.161   83.43 657.518   82.37  687.39   82.24 712.939   83.39 716.843   84.73
 720.249   89.14  753.44  89.189 858.228   90.08  901.27    92.7  938.52   93.22
 1010.86   98.19 1103.55  101.83 1152.22  104.29 1265.93  111.66 1364.43  112.54
#Mann= 10 ,-1 , 0
       0    .045       0   21.29     .04       0   79.92     .04       0
  296.59     .04       0  378.22     .09       0  620.27     .04       0
 638.997     .05       0 720.249     .04       0  753.44     .09       0
 1103.55     .07       0
Bank Sta=638.997,720.249
XS Rating Curve= 0 ,0
Exp/Cntr=0.5,0.3

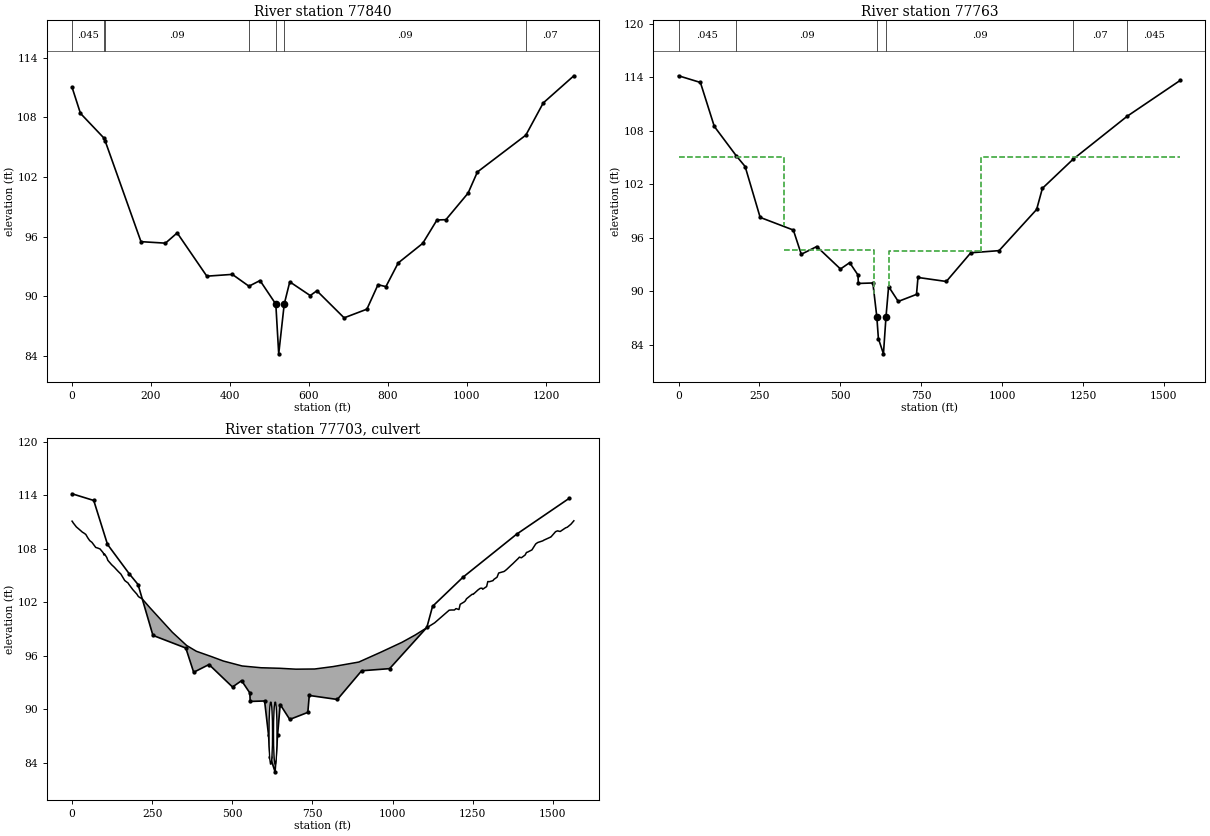
Type RM Length L Ch R = 1 ,77840   ,58.23,77.11,117.97
XS GIS Cut Line= 5
 2356783.5604708604194.4209307432356682.95214091604154.619833231
2356524.85333686604122.5578380082355855.97378115604163.464521572
2355526.50914049604130.296940282
#Sta/Elev= 30
       0  111.02   21.25   108.4   79.68  105.96   83.62  105.65  174.53    95.5
  236.48   95.35  266.21   96.38  341.27   92.03  405.84   92.21  447.95   91.02
  475.95   91.59  515.97   89.22  523.34   84.22  537.29   89.22  551.33   91.46
   603.1   90.08  619.93   90.56  688.94   87.84  746.61   88.71  774.76   91.17
  794.78   90.98  825.93   93.36  888.03   95.33  924.09   97.68  946.75   97.71
 1002.88  100.38 1026.54  102.51 1149.16  106.21 1193.26  109.45 1270.77  112.18
#Mann= 7 ,-1 , 0
       0    .045       0   79.68     .04       0   83.62     .09       0
  447.95     .04       0  515.97     .05       0  537.29     .09       0
 1149.16     .07       0
Bank Sta=515.97,537.29
XS Rating Curve= 0 ,0
Exp/Cntr=0.5,0.3

Type RM Length L Ch R = 1 ,77763   ,104.25,117.04,92.21
BEGIN DESCRIPTION:
Surveyed Section
END DESCRIPTION:
XS GIS Cut Line= 6
2356872.69460332 604221.576226222356662.23606965604137.392812744
2356440.08539522604076.5936808142356239.19130003604057.950599998
2356169.99350002604031.0973999952355355.05473273604008.779264405
#Sta/Elev= 30
       0  114.16   67.61  113.41  110.54  108.48   178.7  105.17  205.86  103.98
  252.32   98.27  354.94   96.85  379.43   94.13  427.28      95  500.61   92.48
  528.99   93.19  554.67   91.81  555.82   90.86 600.746   90.91 612.938   87.12
  617.82   84.68 633.461   82.96  641.22   87.07 649.411   90.51 679.251   88.84
 735.631   89.63  740.17   91.53  827.79   91.08   903.5    94.3  990.91   94.54
    1107   99.16 1124.81  101.53 1219.55  104.79 1386.93  109.62  1551.2  113.65
#Mann= 6 ,-1 , 0
       0    .045       0   178.7     .09       0 612.938     .05       0
  641.22     .09       0 1219.55     .07       0 1386.93    .045       0
#XS Ineff= 4 ,-1
       0     325     105     325  604.61   94.64  649.39     935   94.48
     935    1560     105
Permanent Ineff=
       F       F       F       F
Bank Sta=612.938,641.22
XS Rating Curve= 0 ,0
Exp/Cntr=0.5,0.3

Type RM Length L Ch R = 2 ,77703   ,,,
BEGIN DESCRIPTION:
SR_1716
END DESCRIPTION:
Bridge Culvert--1,0,-1,-1, 0
Deck Dist Width WeirC Skew NumUp NumDn MinLoCord MaxHiCord MaxSubmerge Is_Ogee
50.51,20.08,2.6,0, 109, 109, , , 0.98, 0, 1,1,,
       0     .87    3.01   13.39   18.96   27.95   32.57   35.44    42.8    49.3
   55.15   62.05   73.79   80.07   87.24   97.07    99.5  101.31  108.35  111.66
  123.41  131.75  139.65   144.4  152.29  164.63  164.73  165.13  174.66   177.2
  189.89  202.19  206.38   209.9  219.18  221.46  242.84  312.69  357.39  387.77
  435.08 472.506 530.623  589.76 648.633 698.361 756.839 814.278  894.75  964.26
 1029.73 1070.95 1131.36 1176.77 1183.45 1193.07 1198.02 1207.23 1211.06  1222.9
 1227.02 1230.81  1248.1 1251.72 1253.08 1254.21 1266.56 1273.44 1279.16  1281.3
 1293.56 1297.24 1302.92 1312.81 1313.48 1316.16 1326.05 1331.15 1347.76 1349.15
  1355.8 1371.16 1374.31  1387.2 1392.66 1395.79 1401.99 1413.73 1417.96 1421.17
 1434.69 1435.03 1446.67  1452.9 1468.85  1471.8 1493.77 1494.24 1494.61  1508.7
 1515.02 1520.36 1523.18  1526.8 1540.08 1545.38 1556.07  1556.5 1565.75
  111.09  111.06  110.92  110.44  110.27  109.99  109.84  109.79   109.6   109.2
   108.9  108.71  108.14  108.07  107.97  107.54  107.29  107.41  107.01  106.69
   106.2  105.92  105.61  105.43  105.15  104.41  104.41   104.4  104.15     104
  103.39   102.9  102.66  102.55  102.37  102.26  101.38   98.63   97.14   96.49
   95.89   95.39   94.84   94.64   94.58   94.48    94.5   94.77   95.28    96.4
    97.5   98.32   99.68   101.1  101.12  101.12  101.28  101.17  101.76  102.01
  102.14  102.38  102.88  102.88  102.96  102.96  103.37  103.55  103.57  103.45
  103.75  104.31   104.3  104.41  104.41  104.55   104.8  105.27  105.44  105.47
  105.66  106.18  106.28  106.73  106.92  107.05  106.98  107.29  107.58  107.61
  107.86  107.87  108.53  108.69  108.88  108.95  109.31  109.31  109.33  109.91
     110  109.95  109.93  110.02  110.34  110.41  110.73  110.74  111.13
                                                                                
                                                                                
                                                                                
                                                                                
                                                                                
                                                                                
                                                                                
                                                                                
                                                                                
                                                                                
                                                                        
       0     .87    3.01   13.39   18.96   27.95   32.57   35.44    42.8    49.3
   55.15   62.05   73.79   80.07   87.24   97.07    99.5  101.31  108.35  111.66
  123.41  131.75  139.65   144.4  152.29  164.63  164.73  165.13  174.66   177.2
  189.89  202.19  206.38   209.9  219.18  221.46  242.84  312.69  357.39  387.77
  435.08 472.506 530.623  589.76 648.633 698.361 756.839 814.278  894.75  964.26
 1029.73 1070.95 1131.36 1176.77 1183.45 1193.07 1198.02 1207.23 1211.06  1222.9
 1227.02 1230.81  1248.1 1251.72 1253.08 1254.21 1266.56 1273.44 1279.16  1281.3
 1293.56 1297.24 1302.92 1312.81 1313.48 1316.16 1326.05 1331.15 1347.76 1349.15
  1355.8 1371.16 1374.31  1387.2 1392.66 1395.79 1401.99 1413.73 1417.96 1421.17
 1434.69 1435.03 1446.67  1452.9 1468.85  1471.8 1493.77 1494.24 1494.61  1508.7
 1515.02 1520.36 1523.18  1526.8 1540.08 1545.38 1556.07  1556.5 1565.75
  111.09  111.06  110.92  110.44  110.27  109.99  109.84  109.79   109.6   109.2
   108.9  108.71  108.14  108.07  107.97  107.54  107.29  107.41  107.01  106.69
   106.2  105.92  105.61  105.43  105.15  104.41  104.41   104.4  104.15     104
  103.39   102.9  102.66  102.55  102.37  102.26  101.38   98.63   97.14   96.49
   95.89   95.39   94.84   94.64   94.58   94.48    94.5   94.77   95.28    96.4
    97.5   98.32   99.68   101.1  101.12  101.12  101.28  101.17  101.76  102.01
  102.14  102.38  102.88  102.88  102.96  102.96  103.37  103.55  103.57  103.45
  103.75  104.31   104.3  104.41  104.41  104.55   104.8  105.27  105.44  105.47
  105.66  106.18  106.28  106.73  106.92  107.05  106.98  107.29  107.58  107.61
  107.86  107.87  108.53  108.69  108.88  108.95  109.31  109.31  109.33  109.91
     110  109.95  109.93  110.02  110.34  110.41  110.73  110.74  111.13
                                                                                
                                                                                
                                                                                
                                                                                
                                                                                
                                                                                
                                                                                
                                                                                
                                                                                
                                                                                
                                                                        
BR Coef=-1 , 0 , 0 ,, 0 ,,,0.8,-1,,0,
WSPro=,,,, 1 ,,,, 0 ,,,, 0 ,,,,-1 ,-1 ,-1 , 0 , 0 , 0 , 0 , 0
Multiple Barrel Culv=3,7,10.79,70,0.024,0.9,1,34,3,83.8,84.26, 2,Culvert #1  , 0 ,23
     620     654     634     668
Culvert Bottom n=0.024
BC Design=,, 0 ,, 0 ,,,,,,
BC Use User HTab Curves=0
BC User HTab FreeFlow(D)= 0