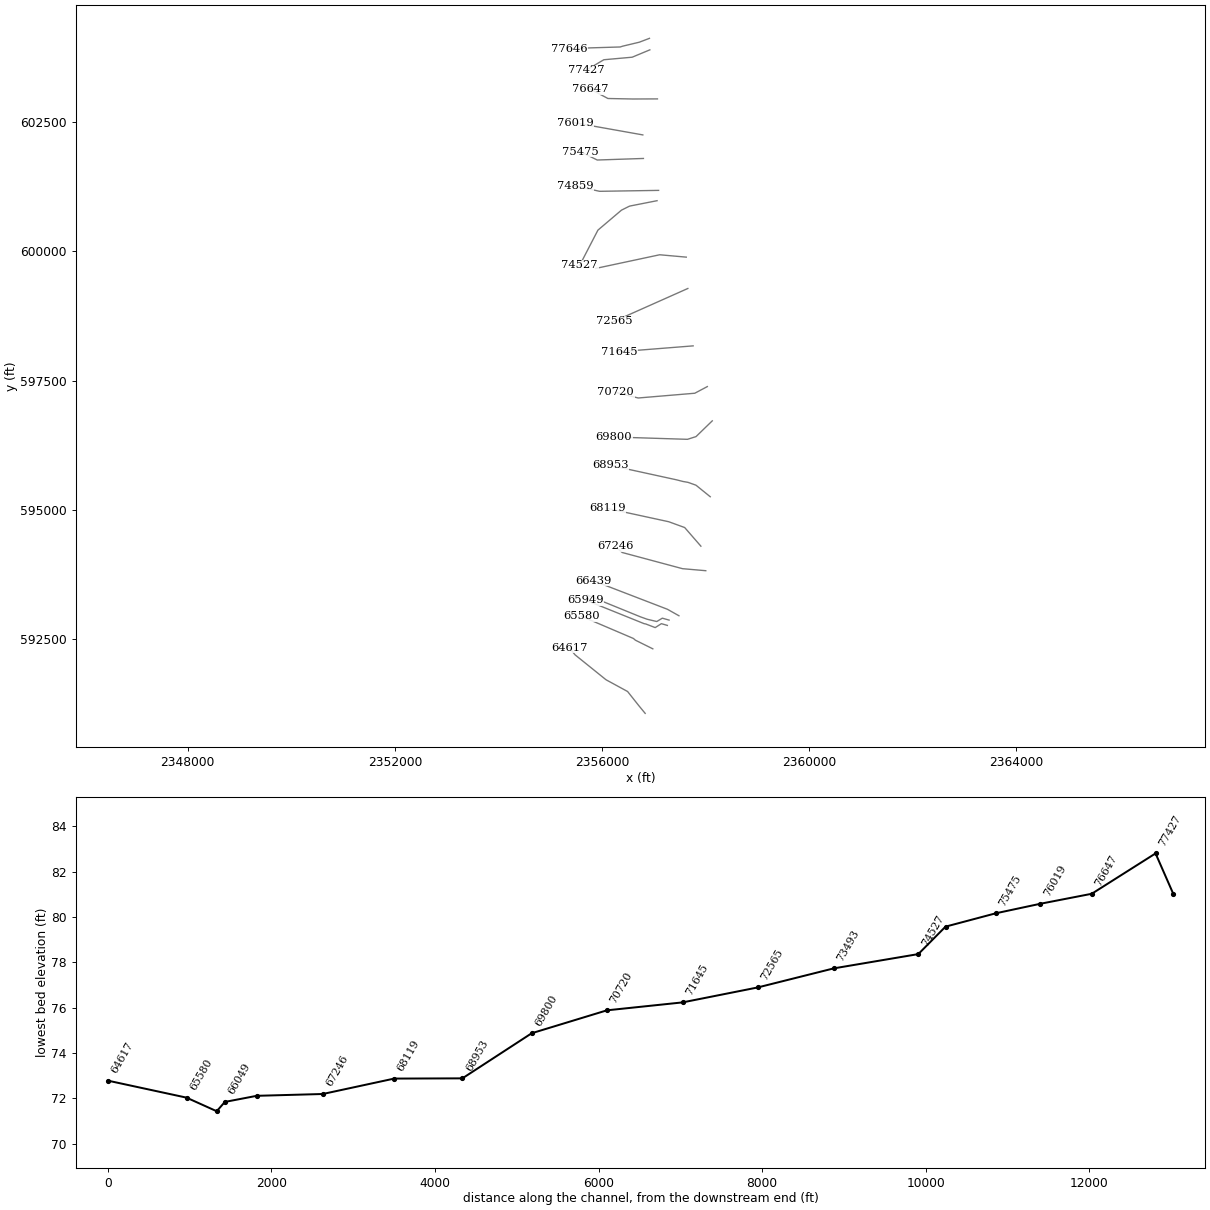
HEC-RAS study DTL_Bear_Creek.prj: DTL_Bear_Creek

--- DTL_Bear_Creek.g02 (geometry) --- (continued)

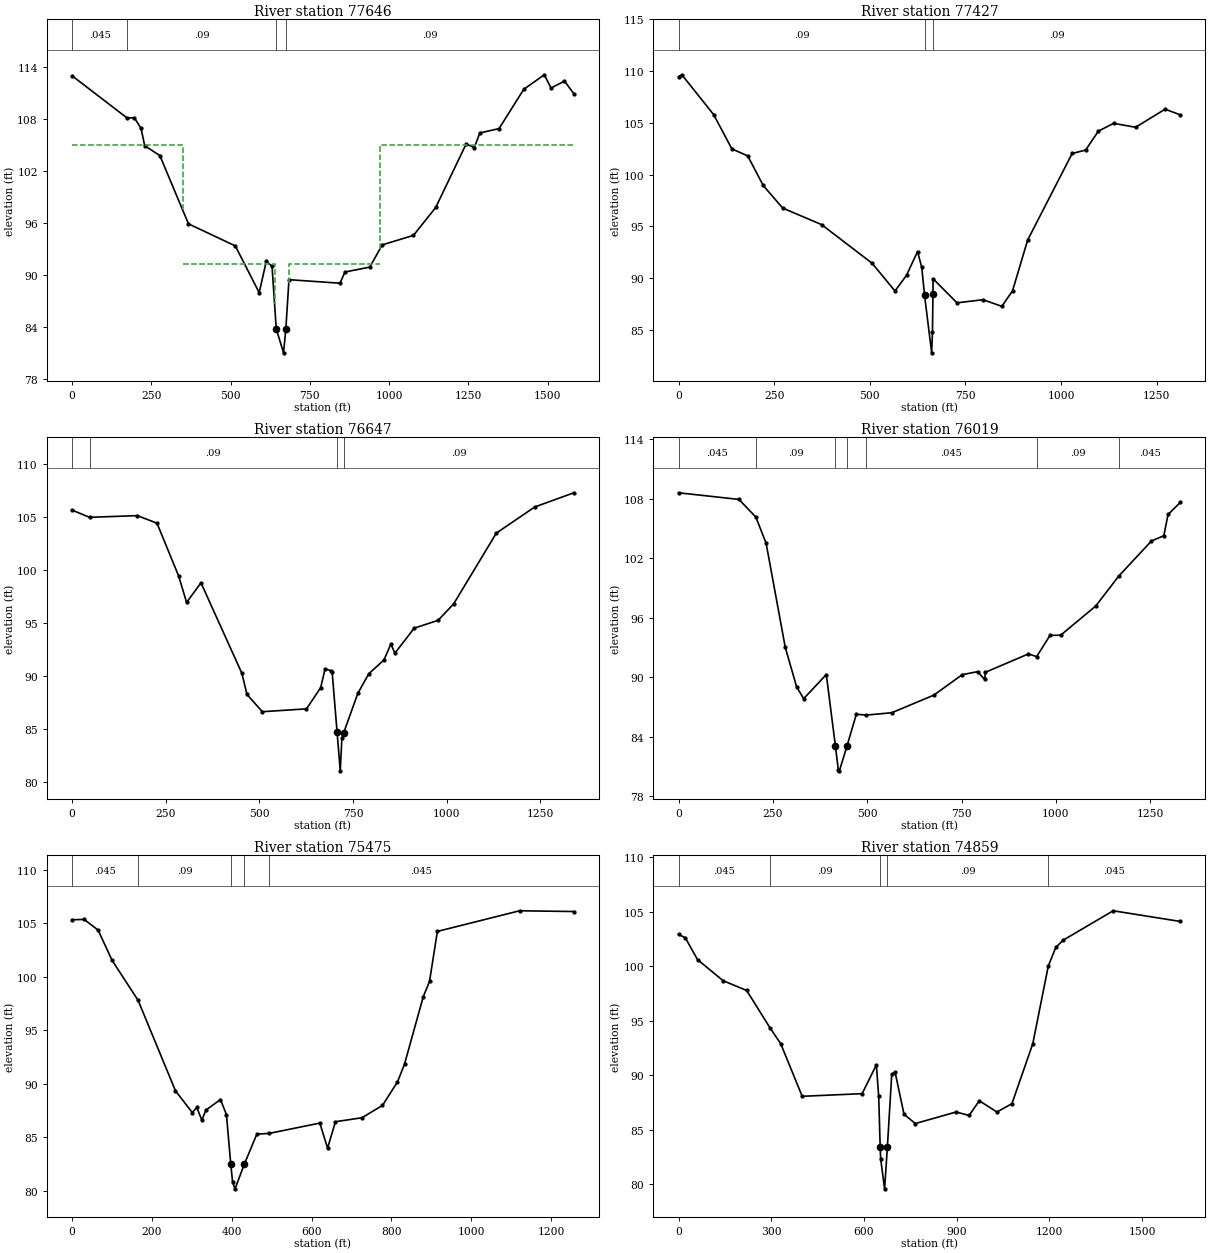
Type RM Length L Ch R = 1 ,77646   ,230.86,218.81,229.58
BEGIN DESCRIPTION:
Surveyed Section
END DESCRIPTION:
XS GIS Cut Line= 6
2356914.78631003604116.3469593822356718.35834529604041.517258525
2356396.85789999603964.808200017    2356350.1261603949.435600013
2355761.94123115603931.6111353932355359.73158903603910.565282032
#Sta/Elev= 30
       0  112.95  174.21  108.07  196.23  108.12  217.63  106.88  228.99  104.89
  276.88  103.75     367   95.88  514.78   93.33 590.084   87.94 612.429   91.56
 630.606   90.97 643.839   83.76  666.87      81  674.05   83.75 683.963   89.44
  844.77   89.03  860.53   90.32  938.91   90.89  977.99   93.45 1076.59   94.55
 1146.75   97.77 1242.51  105.08 1268.38  104.68 1285.81  106.36 1346.21  106.86
  1424.5   111.4  1489.1  113.07  1510.3  111.54 1552.77  112.34 1582.29  110.89
#Mann= 4 ,-1 , 0
       0    .045       0  174.21     .09       0 643.839     .05       0
  674.05     .09       0
#XS Ineff= 4 ,-1
       0     350     105     350  638.61   91.26  683.39     970   91.26
     970    1600     105
Permanent Ineff=
       F       F       F       F
Bank Sta=643.839,674.05
XS Rating Curve= 0 ,0
Exp/Cntr=0.5,0.3

Type RM Length L Ch R = 1 ,77427   ,798.36,779.84,775.35
XS GIS Cut Line= 4
2356922.22833841603893.7611636072356580.39108434603751.552167714
2356033.19889674603702.4451764822355695.69497076 603502.47444509
#Sta/Elev= 30
       0  109.46    8.76  109.65   91.92   105.8  139.48  102.49   180.9  101.82
  221.38   98.96  272.26   96.78  374.14   95.18  506.43   91.44  565.89   88.77
  596.06   90.29  624.87   92.58   635.9   91.05  643.13   88.39  661.79    82.8
  663.94    84.8  665.13   88.49  665.48   89.95  728.04   87.63  795.98   87.93
  845.31   87.29  873.27   88.79  912.75   93.69 1029.12  102.05  1064.3  102.38
 1097.67  104.21 1137.56  104.96 1194.95  104.58 1272.12  106.33 1311.93  105.78
#Mann= 3 , 0 , 0
       0     .09       0  643.13     .05       0  665.13     .09       0
#XS Ineff= 2 , 0
       0  624.87      89               0
Permanent Ineff=
       T       F
Bank Sta=643.13,665.13
XS Rating Curve= 0 ,0
Exp/Cntr=0.3,0.1

Type RM Length L Ch R = 1 ,76647   ,642.12,627.87,601.31
XS GIS Cut Line= 4
2357068.96085785602945.6433456542356588.43831325602943.801547602
2356112.83433707602953.4421687422355774.70478891603133.761960328
#Sta/Elev= 30
       0  105.67   46.61  104.99  174.51  105.15  226.75  104.43  284.59   99.43
  305.73   96.94  344.03    98.8  453.32   90.24  466.87   88.24  507.91   86.61
  625.76   86.88  663.65   88.89  675.37   90.66  690.27   90.49  694.31   90.33
  707.46   84.66  715.83   81.02  720.25   84.13  724.63   84.58  762.74   88.34
  792.01    90.2  832.67   91.51  850.93   93.01   861.7   92.14  913.28   94.51
  977.03   95.25 1018.67   96.81 1132.59   103.5 1235.14  105.97 1339.43  107.31
#Mann= 4 ,-1 , 0
       0    .045       0   46.61     .09       0  707.46     .05       0
  724.63     .09       0
#XS Ineff= 2 , 0
       0  676.15      89               0
Permanent Ineff=
       T       F
Bank Sta=707.46,724.63
XS Rating Curve= 0 ,0
Exp/Cntr=0.3,0.1

Type RM Length L Ch R = 1 ,76019   ,532.11,544.34,585.63
XS GIS Cut Line= 2
2356786.78293581602249.6044713712355477.47737773 602482.87155357
#Sta/Elev= 30
       0  108.62   160.1  107.95  205.07  106.16  232.16  103.52  282.82   93.04
  313.04   89.04  331.65   87.86  391.67   90.29  415.87   83.06  423.47   80.67
  426.32   80.58  446.34   83.07  471.25   86.29  497.26    86.2  565.14   86.44
  676.42   88.21  751.97   90.28  792.48   90.58  811.26    89.8  813.36   90.52
  927.24   92.37  949.17    92.1  984.55   94.24 1012.86   94.26 1105.72    97.2
 1166.74  100.22 1253.49  103.76 1286.17  104.29  1297.4  106.43 1329.92  107.65
#Mann= 7 ,-1 , 0
       0    .045       0  205.07     .09       0  415.87     .05       0
  446.34     .09       0  497.26    .045       0  949.17     .09       0
 1166.74    .045       0
#XS Ineff= 2 , 0
       0  391.67      89               0
Permanent Ineff=
       T       F
Bank Sta=415.87,446.34
XS Rating Curve= 0 ,0
Exp/Cntr=0.3,0.1

Type RM Length L Ch R = 1 ,75475   ,624.37,615.73,611.06
XS GIS Cut Line= 3
2356798.07005273601794.3574238722355906.38781917601764.258445531
2355579.06142965601926.040454149
#Sta/Elev= 30
       0  105.33   30.49  105.36   65.27  104.36  100.17  101.54  165.46   97.79
  259.07   89.33  301.12    87.3  312.67   87.77  325.12   86.58  335.43   87.53
  371.87   88.51  386.75   87.11  397.68   82.45  402.33   80.77  408.33   80.16
  431.44   82.45  463.01   85.28  493.12   85.34  620.75   86.31   640.2   83.97
  659.98   86.44   726.3   86.81  777.63   87.96  815.12   90.14  833.01   91.83
  879.95   98.13  895.62   99.56  915.31  104.24 1121.32  106.17 1257.31   106.1
#Mann= 5 ,-1 , 0
       0    .045       0  165.46     .09       0  397.68     .05       0
  431.44     .09       0  493.12    .045       0
#XS Ineff= 2 , 0
          371.87   88.51
Permanent Ineff=
       F       F
Bank Sta=397.68,431.44
XS Rating Curve= 0 ,0
Exp/Cntr=0.3,0.1

Type RM Length L Ch R = 1 ,74859   ,284.52,332.58,476.71
XS GIS Cut Line= 3
2357091.53509156601177.3283677552355952.80002613601159.322574779
2355473.71500544601263.862930506
#Sta/Elev= 30
       0  102.91   21.84  102.61   61.43   100.6  143.94   98.67  220.41   97.77
   296.2   94.33  330.38    92.9  400.17   88.06  594.08    88.3  640.06   90.94
  647.62   88.08  652.51   83.42  653.95   82.34  666.76   79.57  675.81   83.43
  689.88   90.06  700.92   90.25  729.59   86.41  766.19   85.56  898.33   86.62
  940.24    86.3  973.17   87.65 1030.23   86.62 1078.71   87.38 1146.15   92.87
 1196.51  100.02 1220.83  101.73 1244.92  102.39 1406.48  105.08 1623.66   104.1
#Mann= 5 ,-1 , 0
       0    .045       0   296.2     .09       0  652.51     .05       0
  675.81     .09       0 1196.51    .045       0
#XS Ineff= 2 , 0
          640.06   90.94
Permanent Ineff=
       F       F
Bank Sta=652.51,675.81
XS Rating Curve= 0 ,0
Exp/Cntr=0.3,0.1

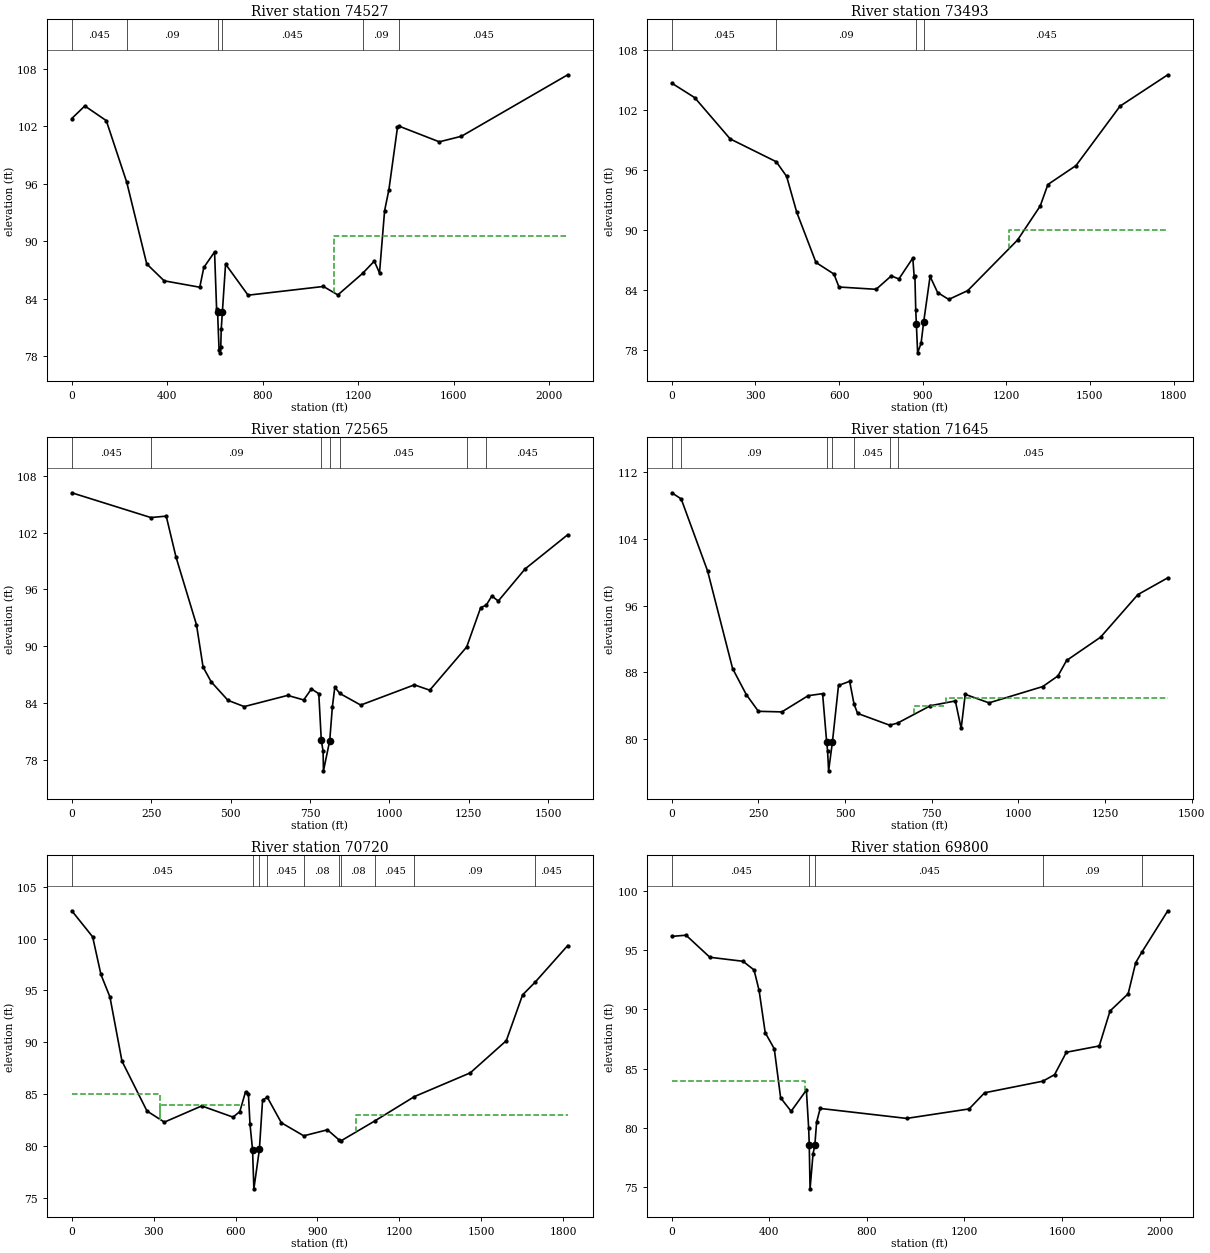
Type RM Length L Ch R = 1 ,74527   ,1053.58,1033.79,934.27
BEGIN DESCRIPTION:
Surveyed Section
END DESCRIPTION:
XS GIS Cut Line= 6
2357061.43611324600977.9226362112356535.05520003600874.176799998
    2356519.3795600867.7818000172356373.89430001600794.829999998
2355919.37920623600408.6395420732355567.77431279599728.815034792
#Sta/Elev= 30
       0  102.79   54.57   104.1  144.62  102.57   230.5   96.13  314.11   87.63
  387.06   85.87 536.393    85.2  553.32   87.26 598.375   88.88 606.931   82.91
 611.039   82.59 617.257   78.65 620.845   78.36  624.43   79.02 626.339   80.84
  630.98   82.58 644.512   87.61  738.73   84.37 1054.58   85.28 1115.08    84.4
 1218.59   86.64  1267.8   87.92 1289.61   86.69 1310.96   93.18 1328.92   95.36
 1364.88  101.86 1369.69  102.01 1540.14  100.36 1633.04  100.94 2078.44  107.35
#Mann= 6 ,-1 , 0
       0    .045       0   230.5     .09       0 611.039     .05       0
  630.98    .045       0 1218.59     .09       0 1369.69    .045       0
#XS Ineff= 2 , 0
       0  598.38      88    1100       0    90.5
Permanent Ineff=
       T       F
Bank Sta=611.039,630.98
XS Rating Curve= 0 ,0
Exp/Cntr=0.3,0.1

Type RM Length L Ch R = 1 ,73493   ,874.57,928.12,969.3
XS GIS Cut Line= 3
2357625.79195727599886.8346711252357112.24539514599932.714211851
2355876.28884083599668.617078096
#Sta/Elev= 30
       0  104.64   82.05   103.2  209.34   99.08  374.75    96.8  411.87   95.34
  448.02   91.77  517.09   86.75  581.69   85.59   599.6    84.3  732.97   84.07
  787.38   85.41  814.54    85.1  864.59   87.19  869.49   85.31  872.09    85.4
  875.08   82.04   877.4   80.58  881.86   77.73  894.24   78.68  903.72   80.84
  926.56   85.36  953.53   83.75  993.43   83.06 1061.64   83.94 1240.41   88.99
 1321.61   92.38 1349.27   94.53 1450.18   96.42 1608.14  102.35 1779.45  105.48
#Mann= 4 ,-1 , 0
       0    .045       0  374.75     .09       0   877.4     .05       0
  903.72    .045       0
#XS Ineff= 2 , 0
       0                    1210       0      90
Permanent Ineff=
       F       F
Bank Sta=877.4,903.72
XS Rating Curve= 0 ,0
Exp/Cntr=0.3,0.1

Type RM Length L Ch R = 1 ,72565   ,962.78,919.71,810.48
XS GIS Cut Line= 2
2357655.89093561599281.0927318932356229.95183641598645.251814306
#Sta/Elev= 30
       0  106.19  248.87  103.58  297.29  103.73  328.07   99.42  392.61   92.28
  413.31   87.83  438.82   86.27  491.67   84.32  542.87   83.66  679.71   84.84
  730.04   84.36  754.38   85.52  777.56   85.02  785.46   80.13  791.09   78.96
  792.32   76.89  812.02   80.08  820.39   83.65  827.98    85.7  844.03   85.04
  909.58   83.82 1078.42   85.95 1126.92   85.39 1243.09   89.94 1287.31    94.1
 1304.61   94.34 1322.45   95.32 1342.46   94.78 1427.14   98.17 1561.28  101.77
#Mann= 7 ,-1 , 0
       0    .045       0  248.87     .09       0  785.46     .05       0
  812.02     .09       0  844.03    .045       0 1243.09     .09       0
 1304.61    .045       0
Bank Sta=785.46,812.02
XS Rating Curve= 0 ,0
Exp/Cntr=0.3,0.1

Type RM Length L Ch R = 1 ,71645   ,923.36,925.42,918.91
XS GIS Cut Line= 2
2357758.16701148598171.6940837952356331.53588833598058.321736529
#Sta/Elev= 30
       0  109.49   27.05  108.75  103.29  100.12   175.4   88.46  214.88   85.35
  249.75   83.35  317.41   83.28  393.46   85.22  435.02   85.46  446.66   79.72
  449.41   78.61  452.41   76.23  463.48   79.72  480.94   86.44  513.12   86.94
  525.65   84.24  535.96    83.1  628.55   81.69  651.31   81.94  746.16   84.02
  818.12   84.59  834.86    81.3  846.63   85.38   915.2   84.36 1070.24   86.31
 1114.09   87.58 1139.09   89.43 1236.95   92.21 1344.81   97.31 1431.13   99.32
#Mann= 7 ,-1 , 0
       0    .045       0   27.05     .09       0  446.66     .05       0
  463.48     .09       0  525.65    .045       0  628.55     .07       0
  651.31    .045       0
#XS Ineff= 3 ,-1
       0     430      84     700     790      84     790    1450      85
Permanent Ineff=
       T       T       T
Bank Sta=446.66,463.48
XS Rating Curve= 0 ,0
Exp/Cntr=0.3,0.1

Type RM Length L Ch R = 1 ,70720   ,856.47,919.34,816.74
XS GIS Cut Line= 4
2358032.12816495597384.8570960022357789.74304186597256.058323294
2356697.29985043597164.1705782122356263.81318702597271.985927224
#Sta/Elev= 30
       0  102.68   76.47  100.17  106.83   96.54  139.85   94.37   183.9   88.19
  275.57   83.38  339.34   82.31  476.09   83.87  591.13   82.79  615.81   83.33
  636.71   85.23  647.16   85.06  653.16   82.09   662.4   79.67  667.28   75.88
  687.51   79.68  699.17   84.44  716.63    84.7  767.96   82.25  850.03   80.99
  936.86   81.57  981.07   80.56  984.89   80.48 1110.84   82.43 1255.51   84.77
 1460.38   87.06 1592.34   90.16 1651.92   94.57 1697.34   95.78 1817.47   99.33
#Mann= 10 ,-1 , 0
       0    .045       0   662.4     .05       0  687.51     .08       0
  716.63    .045       0  850.03     .08       0  981.07    .045       0
  984.89     .08       0 1110.84    .045       0 1255.51     .09       0
 1697.34    .045       0
#XS Ineff= 3 ,-1
       0     325      85     325     636      84    1040    1850      83
Permanent Ineff=
       T       T       T
Bank Sta=662.4,687.51
XS Rating Curve= 0 ,0
Exp/Cntr=0.3,0.1

Type RM Length L Ch R = 1 ,69800   ,915.01,847.54,722.28
XS GIS Cut Line= 4
2358127.72415511596722.3873725832357813.91057192596417.927416608
2357648.36619104596365.2542044822356226.18946412596410.402672008
#Sta/Elev= 30
       0   96.16   58.25   96.26  155.85    94.4  291.81   94.06  337.15   93.33
  357.83    91.6  382.95   88.04  420.07   86.68  446.21   82.54   489.2   81.41
  551.74    83.2   561.1      80  563.51   78.58  566.85   74.87   579.1   77.83
  586.36   78.53  593.64   80.48  608.33   81.65  962.75   80.81 1219.17   81.61
 1282.54   82.97 1521.52   83.95 1569.55    84.5 1617.95   86.39 1752.72   86.92
 1797.03   89.87 1871.28   91.32 1902.13   93.94 1926.87   94.81 2033.85   98.32
#Mann= 5 ,-1 , 0
       0    .045       0  563.51     .05       0  586.36    .045       0
 1521.52     .09       0 1926.87    .045       0
#XS Ineff= 2 , 0
       0     546      84               0
Permanent Ineff=
       T       F
Bank Sta=563.51,586.36
XS Rating Curve= 0 ,0
Exp/Cntr=0.3,0.1

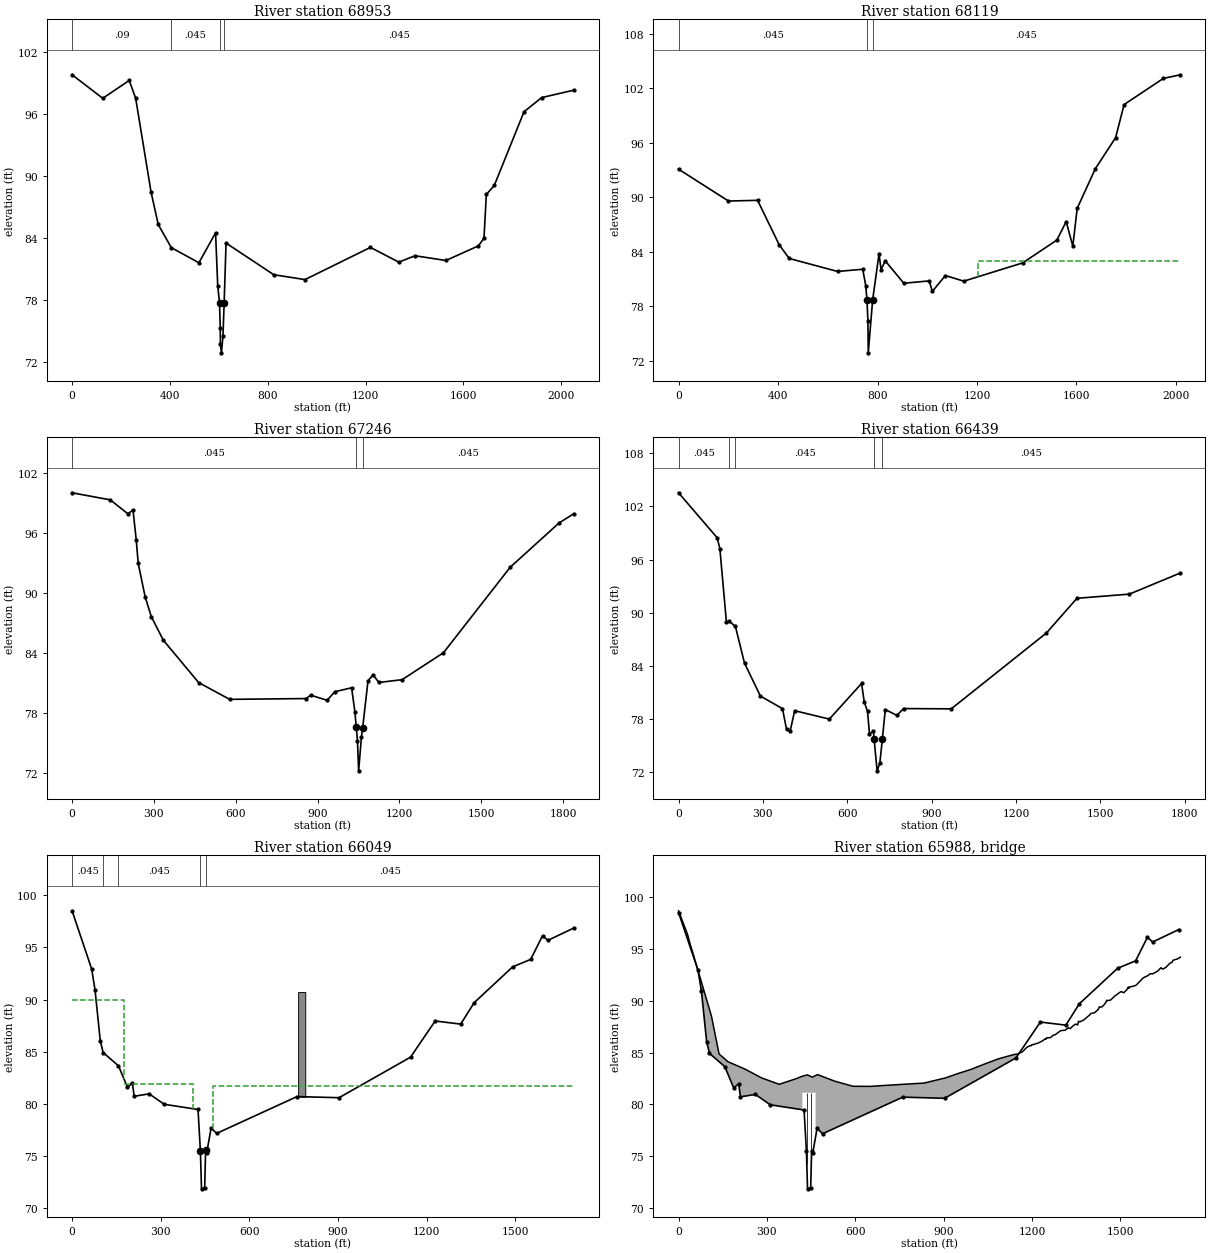
Type RM Length L Ch R = 1 ,68953   ,846.1,833.62,824.68
BEGIN DESCRIPTION:
Surveyed Section
END DESCRIPTION:
XS GIS Cut Line= 6
2358088.56374933 595255.354377942357812.79719789 595478.74724564
2357658.43639998595533.621100008    2357561.1943595550.625499994
2357433.48270002595583.2870000152356162.22913511595861.096317172
#Sta/Elev= 30
       0   99.83  125.58   97.55  233.69   99.28  260.02   97.56  322.95   88.47
  352.37   85.32  405.67   83.08 518.729   81.61 586.807   84.51 595.637   79.39
 602.915   77.73 606.074   75.25  606.42    73.7 610.843   72.88 617.039   74.52
  621.86   77.72 629.688   83.52  824.94   80.45  952.55   79.98  1220.1    83.1
 1336.11   81.67 1402.57   82.29 1528.82   81.83 1661.78   83.25 1684.47      84
 1694.03   88.23 1726.47    89.1 1848.18   96.25 1920.41   97.62 2051.97   98.34
#Mann= 4 ,-1 , 0
       0     .09       0  405.67    .045       0 602.915     .05       0
  621.86    .045       0
#XS Ineff= 2 , 0
       0     586      84               0
Permanent Ineff=
       T       F
Bank Sta=602.915,621.86
XS Rating Curve= 0 ,0
Exp/Cntr=0.3,0.1

Type RM Length L Ch R = 1 ,68119   ,790.98,873.24,797.44
XS GIS Cut Line= 4
2357907.96987927594299.7118154172357594.75748101594660.076120794
2357286.89897642594772.3162005842356102.03117843595029.612040341
#Sta/Elev= 30
       0   93.09  200.88   89.58  317.79   89.66  404.82   84.76  444.88   83.26
  639.15   81.83  740.63   82.07  752.76   80.27  757.62    78.7  761.38   76.42
  762.78   72.87  780.41   78.69   806.2   83.79   814.2   82.02  830.97      83
  905.74   80.53 1007.98   80.79 1020.31   79.63 1072.98   81.38 1146.71   80.76
 1383.57   82.77 1520.97   85.28 1558.61   87.31 1585.29   84.62 1602.88   88.78
 1676.08   93.15 1757.38   96.56 1791.41   100.2 1949.35  103.08 2017.52  103.48
#Mann= 3 ,-1 , 0
       0    .045       0  757.62     .05       0  780.41    .045       0
#XS Ineff= 2 , 0
       0                    1205       0      83
Permanent Ineff=
       F       T
Bank Sta=757.62,780.41
XS Rating Curve= 0 ,0
Exp/Cntr=0.3,0.1

Type RM Length L Ch R = 1 ,67246   ,816.52,807.23,764.25
XS GIS Cut Line= 4
2358002.02918661593825.652906448 2357553.0683085593864.774984002
2356389.45199433594177.3034839332356248.76369788594295.949443102
#Sta/Elev= 30
       0  100.04  140.09   99.33  204.81   97.93  223.35   98.32   235.2   95.34
  242.51   92.96  267.66   89.65  290.47   87.63  334.38   85.28  464.01   81.03
  577.74   79.35  858.04   79.43  874.62   79.77  935.29   79.25  962.76   80.11
 1024.78   80.51 1036.69   78.13 1041.89   76.54 1046.34   75.18 1050.58   72.19
 1060.93   75.62 1065.38   76.52  1084.9   81.21 1103.42   81.81 1124.68   81.04
 1209.92   81.32 1361.59   84.02 1606.15   92.58 1785.06   97.01 1839.56   97.95
#Mann= 3 , 0 , 0
       0    .045       0 1041.89     .05       0 1065.38    .045       0
Bank Sta=1041.89,1065.38
XS Rating Curve= 0 ,0
Exp/Cntr=0.3,0.1

Type RM Length L Ch R = 1 ,66439   ,309.62,390.09,318.44
XS GIS Cut Line= 3
2357484.13796775592954.8139463372357261.88547297593080.056483313
2355834.90274559593630.009547174
#Sta/Elev= 30
       0  103.55  137.25   98.47  146.96   97.24   170.3   88.91  179.15   89.05
  202.17   88.45  234.58   84.29  291.08   80.57  369.61   79.14   384.1    76.8
  396.97    76.6  412.89   78.91  536.28   77.96  650.94   81.99   660.3   79.91
  672.05   78.82  679.08   76.27  692.75   76.59  695.33   75.75  706.11   72.11
  715.95   73.01  724.93   75.73   735.2   79.04  776.67   78.38  800.03   79.15
  969.77   79.12  1308.3    87.7 1416.78   91.62 1603.12   92.09  1784.4   94.48
#Mann= 5 ,-1 , 0
       0    .045       0  179.15    .035       0  202.17    .045       0
  695.33     .05       0  724.93    .045       0
Bank Sta=695.33,724.93
XS Rating Curve= 0 ,0
Exp/Cntr=0.5,0.3

Type RM Length L Ch R = 1 ,66049   ,111.15,99.28,96.8
BEGIN DESCRIPTION:
Surveyed Section
END DESCRIPTION:
XS GIS Cut Line= 6
2357293.85789485592870.8668553532357163.27353114592908.176673591
2357056.21950002592843.3553999962356871.21790002592887.103400007
2356739.99170001592934.2530000212355715.94279085593352.066773295
#Sta/Elev= 30
       0   98.51   66.35   92.92   77.73   90.91   95.39   86.05  105.09   84.91
  157.04   83.64  187.36   81.58  204.14   81.98  210.12   80.72  260.96   80.95
 311.702   79.95 426.182   79.45  434.16   75.47  437.92   71.84 448.683   71.94
 451.765   75.52 455.512   75.29 470.394   77.67  489.32   77.16  761.16   80.69
  903.22   80.58 1145.25   84.47  1228.4   87.94  1314.9   87.64 1360.57    89.7
 1490.62   93.13 1551.78   93.85 1591.76   96.12 1609.74   95.67 1697.73   96.86
#Mann= 5 ,-1 , 0
       0    .045       0  105.09    .035       0  157.04    .045       0
  434.16     .05       0 451.765    .045       0
#XS Ineff= 3 ,-1
       0     175      90     175   410.4   81.93   475.4    1700   81.73
Permanent Ineff=
       F       F       F
#Block Obstruct= 1 ,-1
  764.79  788.95  90.714
Bank Sta=434.16,451.765
XS Rating Curve= 0 ,0
Exp/Cntr=0.5,0.3

Type RM Length L Ch R = 3 ,65988   ,,,
Bridge Culvert--1,0,-1,-1, 0
Deck Dist Width WeirC Skew NumUp NumDn MinLoCord MaxHiCord MaxSubmerge Is_Ogee
46,22.5,2.6,0, 110, 110, , , 0.98, 0, 1,1,,
       0    4.54    9.82   28.52   30.84    40.7   49.53   54.04  111.88   137.6
 167.701 224.682 282.591 341.663 399.174 419.839   420.4   420.4 437.321 454.283
   465.4   465.4 471.654 529.445 592.471 651.137 710.223  833.45   906.5  948.62
  991.79 1034.68 1085.96 1140.44 1148.34 1166.95 1173.28 1182.69 1191.81 1197.87
 1199.37 1202.61 1219.54 1226.44 1235.33 1246.49 1248.41 1249.95 1262.67 1272.23
 1278.29 1280.98 1297.51  1297.7 1299.97 1312.53 1314.72 1322.03 1329.77 1334.46
 1344.22 1348.32 1354.92 1357.65 1363.07 1376.25 1387.96 1395.56 1399.45 1412.34
 1416.64 1424.97 1428.38 1434.09 1441.74  1450.7  1453.7 1456.27 1466.83 1477.63
 1479.96 1482.23 1495.25 1502.52 1511.48 1522.17    1527 1528.37 1531.36  1541.2
 1552.36 1553.27 1554.08 1576.71 1577.42 1593.19 1601.62 1609.42 1623.42 1625.08
 1627.53 1637.44 1644.16 1654.58 1668.56 1675.54 1678.53  1692.9 1697.97 1703.48
   98.68   98.36   97.95   96.56   96.37   95.33   94.55   94.09    88.5   84.86
   84.11   83.41   82.54   81.93   82.47   82.71   82.71   82.71   82.84   82.62
   82.78   82.78   82.87   82.24   81.74   81.73   81.84   82.05   82.55   82.97
   83.36   83.84   84.39   84.82   84.83   85.06   85.24   85.51   85.64   85.67
   85.76   85.75    85.9   85.99   86.12   86.35    86.3   86.41   86.44   86.67
   86.71   86.77   87.11   87.11   87.12   87.15    87.2   87.38   87.31   87.44
   87.68   87.74   87.66      88   87.97   88.15   88.44   88.62   88.76   88.84
   88.95   89.16   89.41   89.37    89.5   89.84   90.05      90   90.07   90.35
   90.44   90.47   90.75   90.88   90.77   91.07   91.32   91.18   91.33   91.38
   91.48    91.5   91.52   92.18    92.2   92.42   92.61   92.59   92.81   92.85
   92.88   93.18   93.05   93.22   93.63    93.7    93.9   94.03    94.1   94.21
                                                                                
                                                       0   81.12   81.12   81.12
   81.12       0
                                                                                
                                                                                
                                                                                
                                                                                
                                                                                
                                                                                
                                                                                
                                                                                
       0    4.54    9.82   28.52   30.84    40.7   49.53   54.04  111.88   137.6
 167.701 224.682 282.591 341.663 399.174 419.839   426.9   426.9 437.321 454.283
 471.654   471.9   471.9 529.445 592.471 651.137 710.223  833.45   906.5  948.62
  991.79 1034.68 1085.96 1140.44 1148.34 1166.95 1173.28 1182.69 1191.81 1197.87
 1199.37 1202.61 1219.54 1226.44 1235.33 1246.49 1248.41 1249.95 1262.67 1272.23
 1278.29 1280.98 1297.51  1297.7 1299.97 1312.53 1314.72 1322.03 1329.77 1334.46
 1344.22 1348.32 1354.92 1357.65 1363.07 1376.25 1387.96 1395.56 1399.45 1412.34
 1416.64 1424.97 1428.38 1434.09 1441.74  1450.7  1453.7 1456.27 1466.83 1477.63
 1479.96 1482.23 1495.25 1502.52 1511.48 1522.17    1527 1528.37 1531.36  1541.2
 1552.36 1553.27 1554.08 1576.71 1577.42 1593.19 1601.62 1609.42 1623.42 1625.08
 1627.53 1637.44 1644.16 1654.58 1668.56 1675.54 1678.53  1692.9 1697.97 1703.48
   98.68   98.36   97.95   96.56   96.37   95.33   94.55   94.09    88.5   84.86
   84.11   83.41   82.54   81.93   82.47   82.71   82.76   82.76   82.84   82.62
   82.87   82.87   82.87   82.24   81.74   81.73   81.84   82.05   82.55   82.97
   83.36   83.84   84.39   84.82   84.83   85.06   85.24   85.51   85.64   85.67
   85.76   85.75    85.9   85.99   86.12   86.35    86.3   86.41   86.44   86.67
   86.71   86.77   87.11   87.11   87.12   87.15    87.2   87.38   87.31   87.44
   87.68   87.74   87.66      88   87.97   88.15   88.44   88.62   88.76   88.84
   88.95   89.16   89.41   89.37    89.5   89.84   90.05      90   90.07   90.35
   90.44   90.47   90.75   90.88   90.77   91.07   91.32   91.18   91.33   91.38
   91.48    91.5   91.52   92.18    92.2   92.42   92.61   92.59   92.81   92.85
   92.88   93.18   93.05   93.22   93.63    93.7    93.9   94.03    94.1   94.21
                                                                                
                                                       0   81.12   81.12   81.12
   81.12   81.12       0
                                                                                
                                                                                
                                                                                
                                                                                
                                                                                
                                                                                
                                                                                
                                                                                
Pier Skew, UpSta & Num, DnSta & Num=  ,435.4, 2 ,441.9, 2 , 0 , 0 , 0 ,,
       1       1
      71   81.12
       1       1
      71   81.12
Pier Skew, UpSta & Num, DnSta & Num=  ,450.4, 2 ,456.9, 2 , 0 , 0 , 0 ,,
       1       1
      71   81.12
       1       1
      71   81.12
BR Coef=-1 , 1 , 0 ,0.9, 0 ,,,0.8,0,1.2,0,
WSPro=,,,, 1 ,,,, 0 ,,,, 0 ,,,,-1 ,-1 ,-1 , 0 , 0 , 0 , 0 , 0
BC Design=,, 0 ,, 0 ,,,,,,
BC Use User HTab Curves=0
BC User HTab FreeFlow(D)= 0

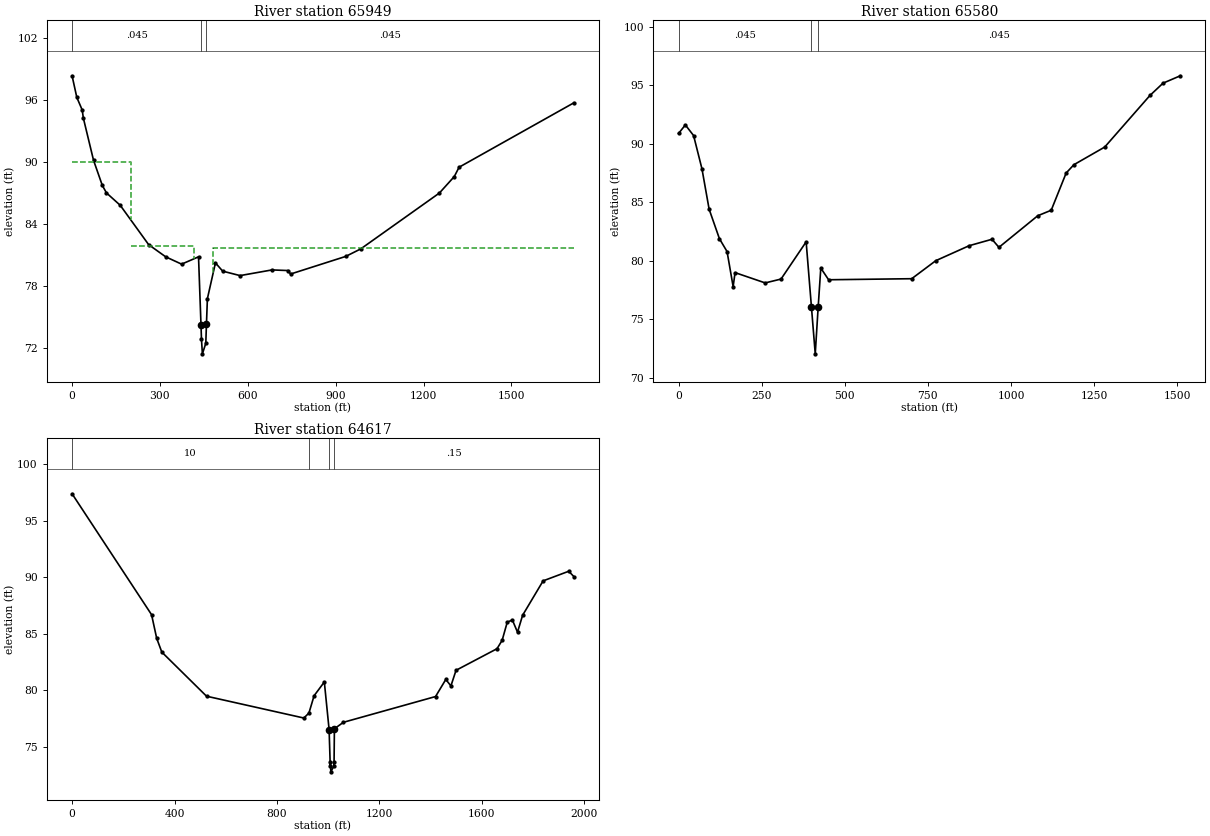
Type RM Length L Ch R = 1 ,65949   ,374.55,369.3,346.46
BEGIN DESCRIPTION:
Surveyed Section
END DESCRIPTION:
XS GIS Cut Line= 6
2357260.27905849592768.2648552662357144.61862203592801.843691662
2357025.64730001592726.0021000062356843.81310003     592795.8882
    2356812.5715592801.491099998 2355677.9333588593259.572000042
#Sta/Elev= 30
       0   98.37   16.25   96.27   34.59   95.06   38.61   94.26   73.23   90.19
  103.38   87.74  117.53   87.02  164.49   85.82  261.47   82.01 319.691   80.83
 374.013   80.12 431.799   80.83  440.16   74.27 441.839   72.85 444.983   71.43
 456.639   72.45  458.82   74.28 462.103   76.78 489.513   80.24 514.384   79.44
 573.636   79.01  682.64   79.56  737.91    79.5  745.87   79.16  934.47   80.87
   985.9    81.6 1254.27   87.01  1305.2   88.61 1321.45   89.51 1713.39   95.75
#Mann= 3 , 0 , 0
       0    .045       0  440.16     .05       0  458.82    .045       0
#XS Ineff= 3 ,-1
       0     200      90     200   416.9   81.85   481.9    1800   81.73
Permanent Ineff=
       F       F       F
Bank Sta=440.16,458.82
XS Rating Curve= 0 ,0
Exp/Cntr=0.5,0.3

Type RM Length L Ch R = 1 ,65580   ,955.7,962.66,884.4
XS GIS Cut Line= 4
2356979.68184374592315.5411970022356643.60297626592482.297886953
 2356605.1206632592515.6492249522355609.16040798592941.495417491
#Sta/Elev= 30
       0   90.86   20.53   91.59   45.31   90.68   70.44   87.84      92   84.39
  122.97   81.87  145.95   80.77  164.22   77.78  170.07   78.97  260.66   78.09
  308.26   78.42  383.83    81.6  399.79   76.02  411.19   72.03  419.95   76.01
  427.87   79.36  451.39   78.36  701.35   78.45  773.74   79.99  874.11   81.27
  942.82   81.82  963.69   81.13 1080.44   83.83 1120.94    84.3 1165.86   87.48
 1189.14   88.19 1281.85    89.7 1417.97   94.11 1457.31   95.16 1509.28   95.79
#Mann= 3 ,-1 , 0
       0    .045       0  399.79     .05       0  419.95    .045       0
Bank Sta=399.79,419.95
XS Rating Curve= 0 ,0
Exp/Cntr=0.3,0.1

Type RM Length L Ch R = 1 ,64617   ,169.88,121.47,272.95
BEGIN DESCRIPTION:
tie in to Bear Creek DTL from Lenior Co. (XS 64617)
END DESCRIPTION:
XS GIS Cut Line= 6
2356831.93140335591067.8340153842356708.55985615591217.733681008
2356492.82600699591490.2395960692356075.86458333591717.645833328
2355478.14062501592199.4322916872355368.36858118592335.753478259
#Sta/Elev= 30
       0  97.373 310.425   86.68 330.425   84.59 350.425   83.37 525.025   79.47
 905.025   77.54 924.925   77.98 945.025   79.51 985.025   80.731003.675   76.52
1008.175   73.281008.275   73.691010.475   72.781021.675   73.271023.075   73.69
1024.375   76.591059.325   77.161419.325   79.441459.325   80.951479.325   80.38
1499.325   81.761659.325   83.671679.325   84.411699.325   86.021719.325   86.21
1739.325   85.131759.325   86.631839.325   89.671939.325   90.52 1959.39  90.052
#Mann= 4 ,-1 , 0
       0      10       0 924.925     .15       01003.675    .051       0
1024.375     .15       0
Bank Sta=1003.675,1024.375
XS Rating Curve= 0 ,0
Exp/Cntr=0.3,0.1
Stream Node=Bear Creek      ,Main            , 0 , 0 ,Upstream end
Stream Node=Bear Creek      ,Main            , 0 , 1 ,Downstream end

Chan Stop Cuts=-1
Use User Specified Reach Order=0

--- DTL_Bear_Creek.g01 (geometry) ---

Geom Title=DTL_Bear_Creek_OLD
Program Version=4.00

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
River Reach=Bear Creek      ,Main
Reach XY= 30
 2350129.0802441  610921.3457202 2350566.7315195   610572.727696
 2350757.3394496  610607.2366379 2350984.7753092  610476.9971481
 2351602.0646194  609061.3494774 2351778.9557018  608914.3737986
 2352041.6909859  608425.3219826  2352478.716013  608011.7090105
 2352889.6247796  607808.6303614 2353062.7167189   607802.301185
 2353125.1488656  607902.4527537 2353377.4787919  607819.2098914
 2354610.5136898    606649.90781 2354618.3177081  606471.7160579
 2354951.2891573  606388.4731956 2355219.2271203  606159.5553243
 2356098.4798534  604784.7474266 2356270.1682569  604143.5172529
 2356440.5559907  600913.9543296 2356923.1044581   598955.145726
 2357274.2852834  598293.1048367 2357410.8556044  596931.3036363
 2357707.4083013  596265.3607379 2357353.6261365  594824.2186843
 2357025.8573663  594441.8217856 2356835.9595866  593364.8672545
 2356917.9017792  593081.3212548 2356850.1364984  592791.6730858
 2356248.0568716   592040.785476 2356026.9430186  591606.3617884

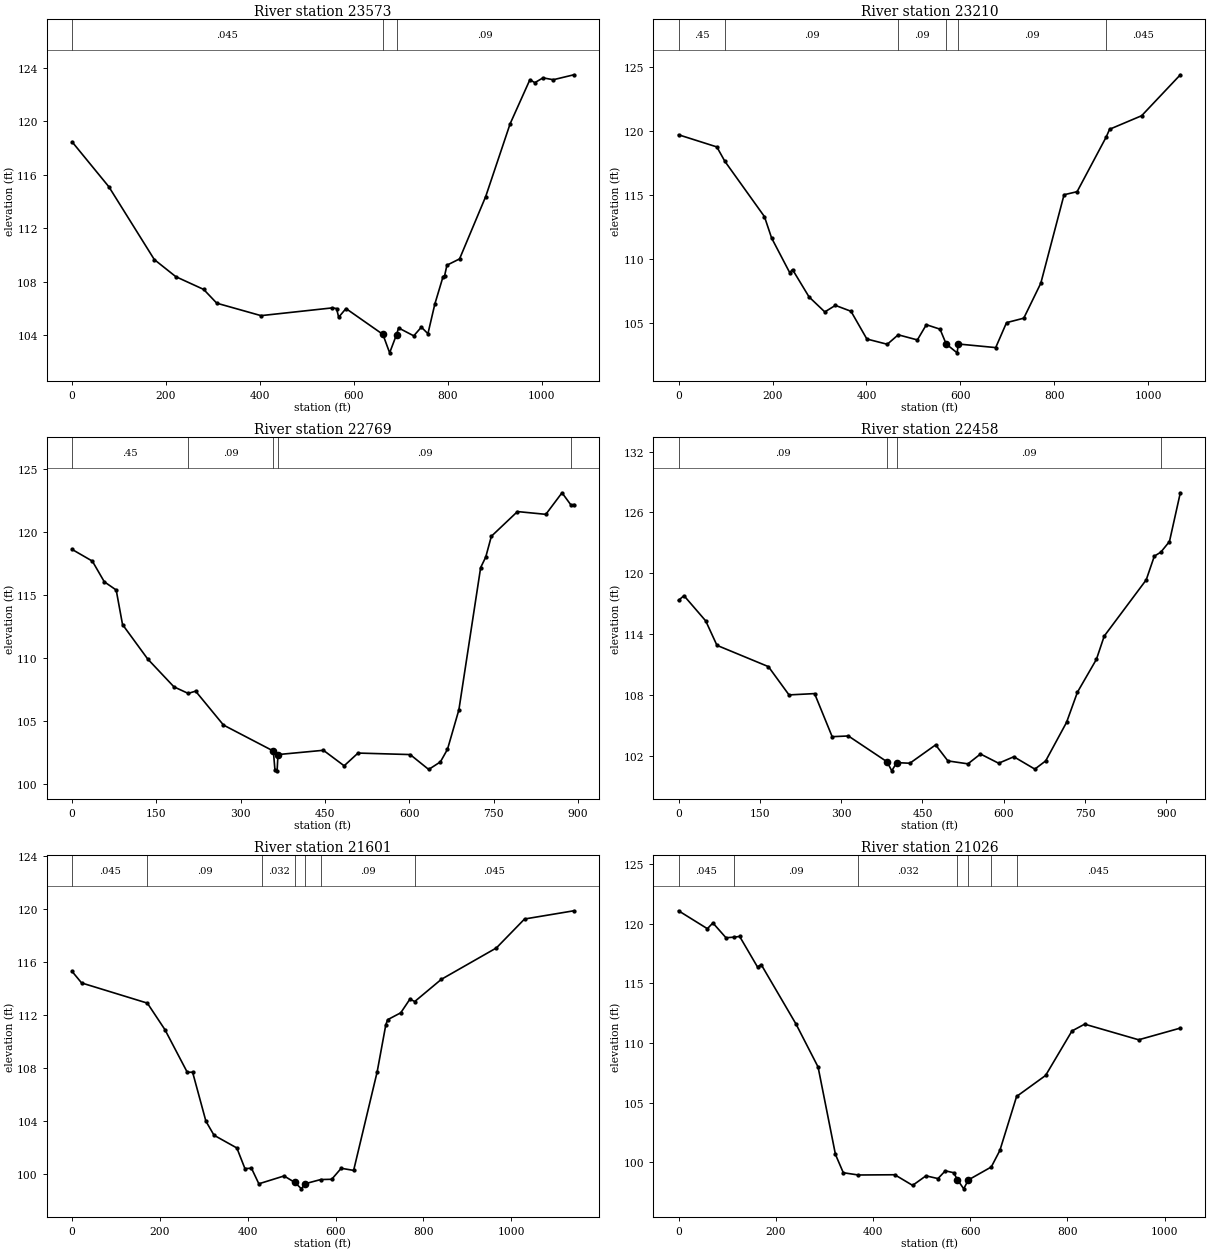
Type RM Length L Ch R = 1 ,23573   ,388.97,363.03,358.88
XS GIS Cut Line= 4
 2350432.1361322  611520.0898023 2350129.0802441  610921.3457202
 2349998.7733939  610740.7284884 2349837.6813099  610673.5560363
#Sta/Elev= 30
       0  118.45   78.36  115.09  175.11  109.65  220.98  108.37  280.15  107.42
  308.11  106.39  402.22  105.46  554.22  106.04   563.1  105.99  567.57  105.34
  583.14  105.99  661.72  104.06  676.11  102.68  690.87  104.05  695.17  104.54
  727.45  103.95  743.65   104.6  757.64  104.11  772.37  106.33  789.79  108.37
  793.14  108.44   798.1  109.23  824.97   109.7  880.62  114.36  932.65   119.8
  974.71  123.09  985.27  122.87 1002.58  123.23 1024.57  123.09 1068.32  123.46
#Mann= 3 , 0 , 0
       0    .045       0  661.72     .05       0  690.87     .09       0
Bank Sta=661.72,690.87
XS Rating Curve= 0 ,0
Exp/Cntr=0.3,0.1

Type RM Length L Ch R = 1 ,23210   ,354.87,441.09,394.49
XS GIS Cut Line= 3
 2350887.3831798  611098.7041055 2350572.5014763  610896.1517003
 2350131.1463488   610361.279136
#Sta/Elev= 30
       0  119.69    81.5  118.74   98.67  117.61  182.83  113.29  198.03  111.62
  236.45  108.92  242.58  109.15  277.79  107.01  311.27  105.84  333.81  106.35
  366.97  105.89  400.79  103.72  444.23  103.31  467.51  104.05  508.26  103.65
  527.36  104.84  556.51  104.49   569.6  103.33  592.82  102.64  595.54  103.33
  674.97  103.05     698     105  734.68  105.35  770.92  108.08  820.42     115
  848.19  115.24  910.03  119.51  917.33  120.12  985.58  121.18 1067.86  124.38
#Mann= 6 ,-1 , 0
       0     .45       0   98.67     .09       0  467.51     .09       0
   569.6     .05       0  595.54     .09       0  910.03    .045       0
Bank Sta=569.6,595.54
XS Rating Curve= 0 ,0
Exp/Cntr=0.3,0.1

Type RM Length L Ch R = 1 ,22769   ,327.77,310.51,243.08
BEGIN DESCRIPTION:
Surveyed Section
END DESCRIPTION:
XS GIS Cut Line= 6
 2350985.2048594  610899.2983739    2350835.9516     610675.0393
    2350806.9704     610624.8994 2350789.4349001     610596.3143
    2350747.1875     610521.1469 2350488.5717167  610158.1110321
#Sta/Elev= 30
       0  118.64    36.1  117.71   57.35  116.07   78.51  115.42    89.8  112.68
  134.55  109.95   181.3  107.74  206.61  107.22   219.8   107.4 269.431  104.71
 358.135  102.65 360.927  101.18  364.81  101.08 366.409  102.37 447.193  102.71
  484.14  101.48  508.82  102.49   601.6  102.37  634.55  101.19  655.41  101.79
     668  102.79  688.28  105.92  727.01   117.2  736.05  118.03  746.05  119.68
  792.51  121.64  842.98  121.42  871.77  123.13  887.85  122.15  892.85   122.2
#Mann= 5 ,-1 , 0
       0     .45       0  206.61     .09       0 358.135     .05       0
 366.409     .09       0  887.85    .045       0
Bank Sta=358.135,366.409
XS Rating Curve= 0 ,0
Exp/Cntr=0.3,0.1

Type RM Length L Ch R = 1 ,22458   ,835.1,857.38,798.14
XS GIS Cut Line= 4
 2351331.3431104   610643.457058 2351045.7993343  610422.8538424
 2350989.6770587  610400.4049321 2350631.5418638  610045.2398633
#Sta/Elev= 30
       0  117.32   10.03  117.78   50.16  115.29   70.88  112.88   165.8  110.78
  203.81  107.99  250.97  108.12   283.4  103.87  313.31  103.94  384.71  101.39
  393.37   100.5  402.46  101.31  426.74  101.25  474.25  103.06  496.88  101.48
  533.87  101.19  557.01  102.16  590.52  101.25  618.54  101.89  657.29  100.67
  677.28  101.48  715.76  105.28  735.86  108.26  770.87   111.5  785.25  113.79
  862.75  119.34  877.72  121.68  889.65  122.07  905.61  123.12  925.66  127.93
#Mann= 4 ,-1 , 0
       0     .09       0  384.71     .05       0  402.46     .09       0
  889.65    .045       0
Bank Sta=384.71,402.46
XS Rating Curve= 0 ,0
Exp/Cntr=0.3,0.1

Type RM Length L Ch R = 1 ,21601   ,544.26,574.78,545.25
XS GIS Cut Line= 3
 2351809.1643916  609898.5073439 2351004.9161768  609460.4209179
 2350785.7991279  609401.8742011
#Sta/Elev= 30
       0   115.3   21.72  114.43  171.39  112.91  211.44  110.91  262.26   107.7
  274.49   107.7  304.75  104.01  323.23  102.95  375.24  101.99  393.58  100.44
  408.54  100.46  425.33   99.29  482.65   99.88  507.48   99.39  522.27   98.91
  530.14   99.29  566.17   99.61  591.22   99.63  612.82  100.46  641.16   100.3
  694.68  107.72  714.47  111.28  718.58  111.66  748.44  112.18  769.32  113.21
   780.3  113.03  840.76   114.7  966.25  117.07 1030.37  119.25 1142.63  119.87
#Mann= 7 ,-1 , 0
       0    .045       0  171.39     .09       0  433.06    .032       0
  507.48     .05       0  530.14    .032       0  566.17     .09       0
   780.3    .045       0
Bank Sta=507.48,530.14
XS Rating Curve= 0 ,0
Exp/Cntr=0.3,0.1

Type RM Length L Ch R = 1 ,21026   ,561.05,573.95,554.78
XS GIS Cut Line= 4
 2352019.8572401    609514.74537 2351794.1149025  609266.4287986
 2351363.9542109   609054.511399  2351146.986868  609051.9735778
#Sta/Elev= 30
       0  121.07   59.28  119.57   70.68  120.05   97.59  118.81  114.56  118.86
   125.7  118.92  162.43  116.36  170.06  116.56  241.74  111.57  287.02  107.98
  322.76  100.65   338.9   99.12   369.8   98.93  444.77   98.95   481.5   98.06
  508.92   98.86  533.63   98.63   548.7   99.28  565.92   99.12  573.72   98.53
  586.64   97.77  595.86   98.51  643.21    99.6  660.96  100.99  695.33  105.51
  754.99  107.27  809.26     111  835.32  111.57  946.41  110.26  1032.1  111.24
#Mann= 7 ,-1 , 0
       0    .045       0  114.56     .09       0   369.8    .032       0
  573.72     .05       0  595.86    .032       0  643.21     .09       0
  695.33    .045       0
Bank Sta=573.72,595.86
XS Rating Curve= 0 ,0
Exp/Cntr=0.3,0.1