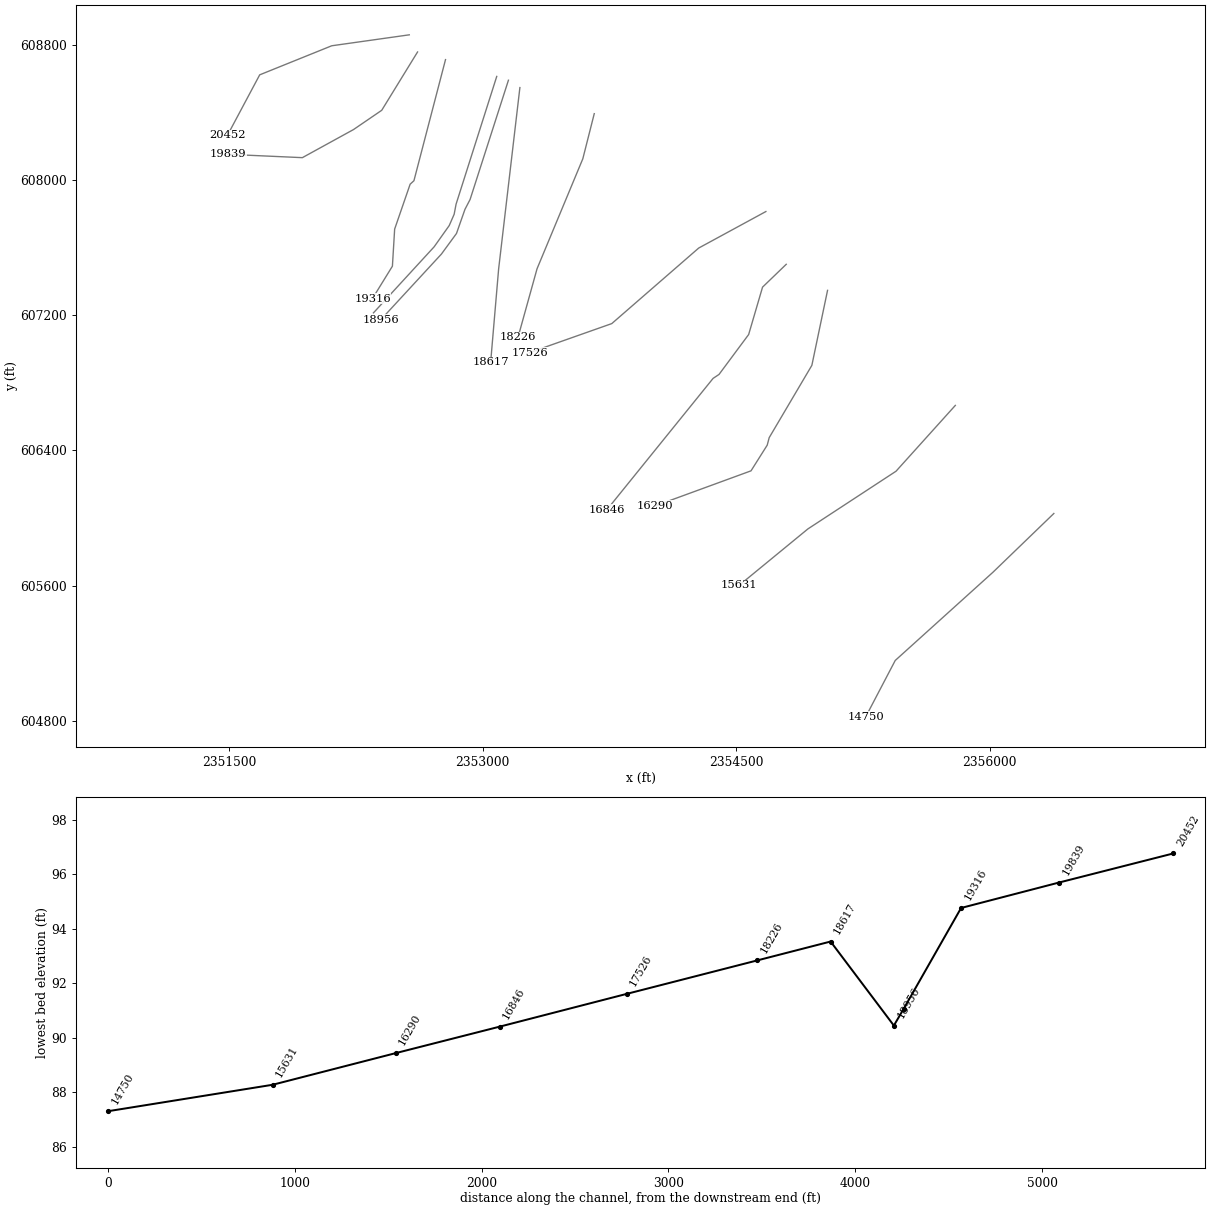
HEC-RAS study DTL_Bear_Creek.prj: DTL_Bear_Creek

--- DTL_Bear_Creek.g01 (geometry) --- (continued)

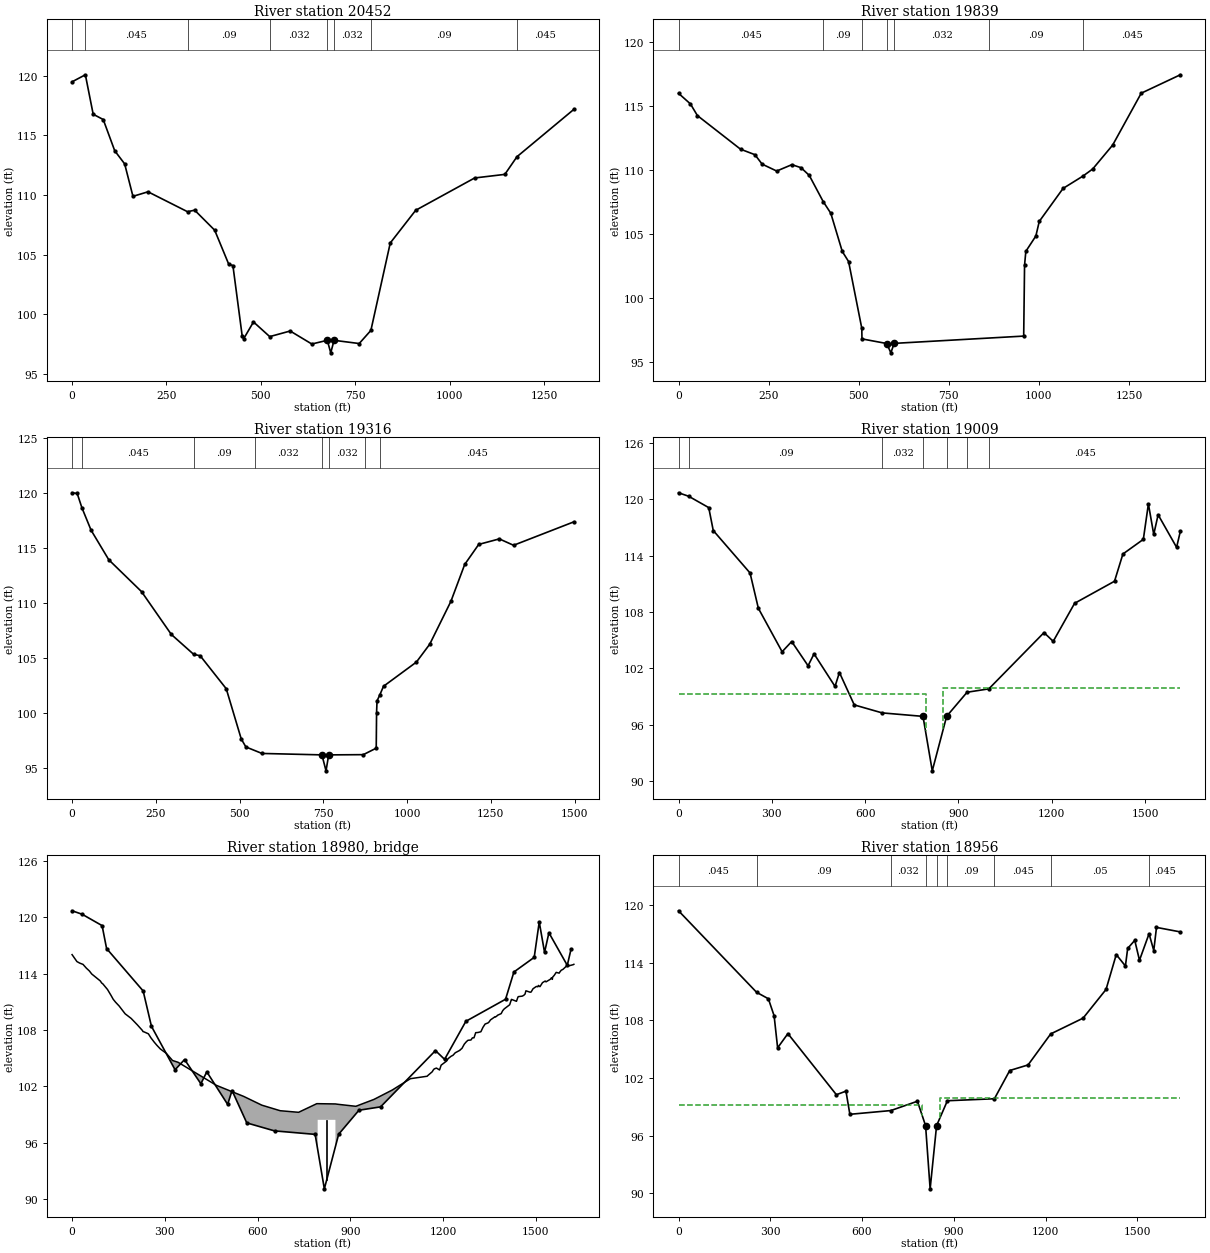
Type RM Length L Ch R = 1 ,20452   ,511.08,613.76,538.94
XS GIS Cut Line= 4
 2352565.4012227  608860.0925909  2352106.510344  608795.3078486
 2351679.9810491  608623.1995366 2351489.3627467  608265.6377685
#Sta/Elev= 30
       0  119.48   35.21  120.07   55.93  116.76    82.5  116.32  112.95   113.7
  139.24   112.6  161.21  109.88   201.1  110.26  305.71  108.59  324.57  108.72
  377.61  107.04   414.9  104.18  425.85  104.08  450.35   98.19  454.35   97.94
  480.31   99.35  523.33   98.12  577.48   98.59  634.76    97.5  675.74   97.81
   684.9   96.76  693.65   97.81  760.25   97.54  791.17   98.64  842.47  105.97
  909.81  108.71 1065.94  111.42  1145.8  111.72 1177.92   113.2 1328.58  117.17
#Mann= 8 ,-1 , 0
       0    .045       0   35.21    .045       0  305.71     .09       0
  523.33    .032       0  675.74     .05       0  693.65    .032       0
  791.17     .09       0 1177.92    .045       0
Bank Sta=675.74,693.65
XS Rating Curve= 0 ,0
Exp/Cntr=0.3,0.1

Type RM Length L Ch R = 1 ,19839   ,392.39,522.73,591.02
XS GIS Cut Line= 5
 2352614.3120625   608758.508539 2352402.2789108   608413.396332
  2352235.591578  608299.5610804 2351932.5312896   608133.064996
  2351493.125119  608152.7665997
#Sta/Elev= 30
       0  115.99   33.03  115.16   52.33  114.25  171.98  111.62  211.94  111.19
  231.99  110.45  272.43  109.91  314.52  110.41  340.12  110.17  362.77  109.57
  401.46  107.52  422.52  106.61   454.4  103.62  471.94  102.83  508.55   97.61
  509.04   96.78  577.62   96.42  589.22   95.69  598.37   96.43  957.85      97
  960.26  102.55  963.81  103.63  991.64  104.83 1001.06  105.97 1067.11  108.55
 1122.51  109.52 1149.33  110.07 1204.72  111.94 1284.05     116 1392.52  117.44
#Mann= 7 ,-1 , 0
       0    .045       0  401.46     .09       0  510.08    .032       0
  577.62     .05       0  598.37    .032       0  862.67     .09       0
 1122.51    .045       0
Bank Sta=577.62,598.37
XS Rating Curve= 0 ,0
Exp/Cntr=0.3,0.1

Type RM Length L Ch R = 1 ,19316   ,291.93,306.71,311.48
XS GIS Cut Line= 6
 2352779.8564433  608713.3600714 2352592.9033996  607996.5007919
 2352570.4544894  607975.9226242 2352478.7881058  607710.2771861
 2352465.5192322  607490.7135867 2352347.1836296  607298.7080891
#Sta/Elev= 30
       0  120.02    15.3  119.96   29.36  118.66   56.77  116.62  109.71  113.93
  207.39  111.04  296.31  107.15   363.1  105.34   382.3  105.22  460.22  102.22
  504.98   97.66  518.84   96.93  566.89   96.34  745.82   96.21  758.11   94.76
  766.05   96.21  869.43   96.23  907.96   96.82  909.01  100.03  910.36  101.11
  919.14  101.69  929.68  102.44 1027.92  104.64 1067.62  106.26 1130.95  110.16
  1172.1  113.51 1213.94  115.33 1275.46  115.83 1317.95  115.25 1497.94  117.38
#Mann= 8 ,-1 , 0
       0    .045       0   29.36    .045       0   363.1     .09       0
  544.65    .032       0  745.82     .05       0  766.05    .032       0
  874.05     .09       0  919.14    .045       0
Bank Sta=745.82,766.05
XS Rating Curve= 0 ,0
Exp/Cntr=0.5,0.3

Type RM Length L Ch R = 1 ,19009   ,68.36,53.08,62.92
BEGIN DESCRIPTION:
Surveyed Section
END DESCRIPTION:
XS GIS Cut Line= 6
 2353083.0379403   608613.845824     2352842.349     607857.7755
 2352830.9624001     607797.9835    2352801.8633      607731.276
  2352712.630921  607605.5156049 2352353.4483569  607214.5304179
#Sta/Elev= 30
       0  120.68   32.59  120.31   97.13   119.1  111.63  116.66  229.93  112.14
  256.68  108.38  333.08  103.75  363.83  104.84  416.53  102.26   435.7  103.53
  503.17  100.06  517.36  101.54  565.05   98.09 654.804   97.24 786.073   96.87
 815.856   91.07 862.099   96.88 927.783   99.44  997.76    99.8 1175.18  105.79
 1204.76  104.86 1273.55  108.91  1401.9  111.26 1428.86  114.16 1494.56  115.72
 1510.84  119.49 1528.01  116.25  1542.1  118.34 1601.51  114.87  1613.5  116.57
#Mann= 7 ,-1 , 0
       0    .045       0   32.59     .09       0 654.804    .032       0
 786.073     .05       0 862.099    .032       0 927.783    .035       0
  997.76    .045       0
#XS Ineff= 2 , 0
       0   794.3   99.22   851.7       0   99.86
Permanent Ineff=
       F       F
Bank Sta=786.073,862.099
XS Rating Curve= 0 ,0
Exp/Cntr=0.5,0.3

Type RM Length L Ch R = 3 ,18980   ,,,
BEGIN DESCRIPTION:
1140 Greene Co. & 1705 Wayne Co.
END DESCRIPTION:
Bridge Culvert--1,0,-1,-1, 0
Deck Dist Width WeirC Skew NumUp NumDn MinLoCord MaxHiCord MaxSubmerge Is_Ogee
12.98,27,2.6,0, 134, 134, , , 0.95, 0, 0,0,,
       0    3.35   15.75   24.53   35.47   46.23   56.02   63.54   76.01    91.6
   95.37   99.41  114.55  126.34  133.12  140.81  152.23  161.65  171.61  186.65
  191.02  207.48  210.67  227.55   229.5  231.62  246.79  254.79  265.69  273.92
  285.32  295.19  304.83  318.52  324.74  342.58  466.83 555.241 613.683 672.958
 732.544 791.373   794.3   794.3 850.517   851.7   851.7 860.616  917.76 976.112
1035.3141094.231  1146.9 1148.28    1151 1165.15 1167.35 1171.15 1178.27 1188.45
 1193.56 1207.46 1211.24 1216.37 1225.78 1231.85 1235.96 1239.18 1254.03 1254.61
 1254.84 1260.96 1268.48 1274.95 1280.35 1290.01  1294.7 1299.71 1302.01 1305.36
 1312.88 1322.11 1325.58 1328.67 1335.78 1345.28 1348.57 1353.21  1367.9 1369.35
 1375.11 1375.77 1387.74 1392.58 1396.66 1400.31 1414.83 1415.16 1420.83 1421.55
 1437.19 1442.06  1443.7 1455.86 1460.47  1464.9 1467.71 1481.12 1484.18  1485.1
  1490.8 1501.48 1506.49 1507.99 1513.18 1521.42 1530.15 1532.64 1546.85 1550.11
 1553.17 1554.35 1559.21 1565.64 1575.25    1577 1581.97 1587.47 1597.55 1604.12
 1604.71 1606.63 1620.63 1622.79
  116.01  115.85  115.27  115.11  114.97  114.57  114.27  113.95  113.61   113.2
     113   112.9   112.3  111.65  111.25  110.94  110.54  110.14  109.71  109.34
  109.22  108.65  108.55  107.93  107.81   107.8  107.58  107.16  106.69  106.37
  105.97  105.73   105.5  104.98  104.74  104.55  102.09  100.91   99.98   99.39
   99.22  100.14  100.14  100.14  100.12  100.11  100.11  100.07   99.86  100.59
  101.59   102.8  103.05  103.06  103.15  103.55  103.69  103.84  103.93  103.73
  104.24  104.59  104.68  104.94  105.19  105.29  105.44  105.56  105.83  105.83
  105.86  106.03  106.48  106.73  106.89  106.92  107.15  107.15  107.36   107.7
  107.72   107.8  108.05  108.26  108.62  108.74  108.84  109.06   109.4  109.37
  109.51  109.55  109.73  110.04   110.2   110.3  110.67  110.67  111.24  111.24
  111.04   111.5  111.54  111.59  111.67  111.81  112.16  112.01  112.02  112.06
  112.38  112.62  112.59  112.73   112.6  113.03   113.2  113.11  113.39  113.54
  113.38  113.62   113.8  114.12  114.04  114.14  114.35  114.44  114.75  114.82
  114.82  114.82  114.94  114.98
                                                                                
                                                                                
                                                                                
                                                                                
                       0   98.42   98.42   98.42       0
                                                                                
                                                                                
                                                                                
                                                                                
                                                                                
                                                                                
                                                                                
                                                                                
                                
       0    3.35   15.75   24.53   35.47   46.23   56.02   63.54   76.01    91.6
   95.37   99.41  114.55  126.34  133.12  140.81  152.23  161.65  171.61  186.65
  191.02  207.48  210.67  227.55   229.5  231.62  246.79  254.79  265.69  273.92
  285.32  295.19  304.83  318.52  324.74  342.58  466.83 555.241 613.683 672.958
 732.544 791.373   797.3   797.3 850.517   854.7   854.7 860.616  917.76 976.112
1035.3141094.231  1146.9 1148.28    1151 1165.15 1167.35 1171.15 1178.27 1188.45
 1193.56 1207.46 1211.24 1216.37 1225.78 1231.85 1235.96 1239.18 1254.03 1254.61
 1254.84 1260.96 1268.48 1274.95 1280.35 1290.01  1294.7 1299.71 1302.01 1305.36
 1312.88 1322.11 1325.58 1328.67 1335.78 1345.28 1348.57 1353.21  1367.9 1369.35
 1375.11 1375.77 1387.74 1392.58 1396.66 1400.31 1414.83 1415.16 1420.83 1421.55
 1437.19 1442.06  1443.7 1455.86 1460.47  1464.9 1467.71 1481.12 1484.18  1485.1
  1490.8 1501.48 1506.49 1507.99 1513.18 1521.42 1530.15 1532.64 1546.85 1550.11
 1553.17 1554.35 1559.21 1565.64 1575.25    1577 1581.97 1587.47 1597.55 1604.12
 1604.71 1606.63 1620.63 1622.79
  116.01  115.85  115.27  115.11  114.97  114.57  114.27  113.95  113.61   113.2
     113   112.9   112.3  111.65  111.25  110.94  110.54  110.14  109.71  109.34
  109.22  108.65  108.55  107.93  107.81   107.8  107.58  107.16  106.69  106.37
  105.97  105.73   105.5  104.98  104.74  104.55  102.09  100.91   99.98   99.39
   99.22  100.14  100.14  100.14  100.12   100.1   100.1  100.07   99.86  100.59
  101.59   102.8  103.05  103.06  103.15  103.55  103.69  103.84  103.93  103.73
  104.24  104.59  104.68  104.94  105.19  105.29  105.44  105.56  105.83  105.83
  105.86  106.03  106.48  106.73  106.89  106.92  107.15  107.15  107.36   107.7
  107.72   107.8  108.05  108.26  108.62  108.74  108.84  109.06   109.4  109.37
  109.51  109.55  109.73  110.04   110.2   110.3  110.67  110.67  111.24  111.24
  111.04   111.5  111.54  111.59  111.67  111.81  112.16  112.01  112.02  112.06
  112.38  112.62  112.59  112.73   112.6  113.03   113.2  113.11  113.39  113.54
  113.38  113.62   113.8  114.12  114.04  114.14  114.35  114.44  114.75  114.82
  114.82  114.82  114.94  114.98
                                                                                
                                                                                
                                                                                
                                                                                
                       0   98.42   98.42   98.42       0
                                                                                
                                                                                
                                                                                
                                                                                
                                                                                
                                                                                
                                                                                
                                                                                
                                
Pier Skew, UpSta & Num, DnSta & Num=  ,823, 4 ,826, 4 , 3 , 3 , 0 ,,
       1       1     1.3     1.3
    90.4   97.12   97.12   98.42
       1       1     1.3     1.3
    90.4   97.12   97.12   98.42
BR Coef=-1 , 0 , 0 ,, 0 ,,,0.8,-1,,0,
WSPro=,,,, 1 ,,,, 0 ,,,, 0 ,,,,-1 ,-1 ,-1 , 0 , 0 , 0 , 0 , 0
BC Design=,, 0 ,, 0 ,,,,,,
BC Use User HTab Curves=0
BC User HTab FreeFlow(D)= 0

Type RM Length L Ch R = 1 ,18956   ,187.58,338.55,268.71
BEGIN DESCRIPTION:
Surveyed Section
END DESCRIPTION:
XS GIS Cut Line= 6
 2353152.2554136  608591.3969138    2352925.2586     607885.4524
    2352894.9844     607827.2074    2352844.7718     607684.2256
  2352755.657999  607562.4885269 2352396.4754349  607173.3740824
#Sta/Elev= 30
       0   119.4  255.29  110.91  293.73  110.24  312.52  108.47  323.97  105.13
  357.59  106.61  516.09  100.25  547.46  100.62  560.19   98.21 694.158    98.6
 781.096   99.57 807.733   97.03  822.67   90.45 843.746   97.03  879.09  99.622
 1032.81   99.83 1082.97  102.77 1142.86  103.35 1216.91  106.58 1322.73  108.22
 1397.82  111.21 1431.22  114.84 1461.18  113.65 1468.54  115.48 1491.68  116.32
 1507.17  114.25 1538.49  117.01 1553.85  115.26 1562.78  117.67 1640.71   117.2
#Mann= 9 ,-1 , 0
       0    .045       0  255.29     .09       0 694.158    .032       0
 807.733     .05       0 843.746    .032       0  879.09     .09       0
 1032.81    .045       0 1216.91     .05       0 1538.49    .045       0
#XS Ineff= 2 , 0
       0   797.3   99.22   854.7       0   99.86
Permanent Ineff=
       F       F
Bank Sta=807.733,843.746
XS Rating Curve= 0 ,0
Exp/Cntr=0.5,0.3

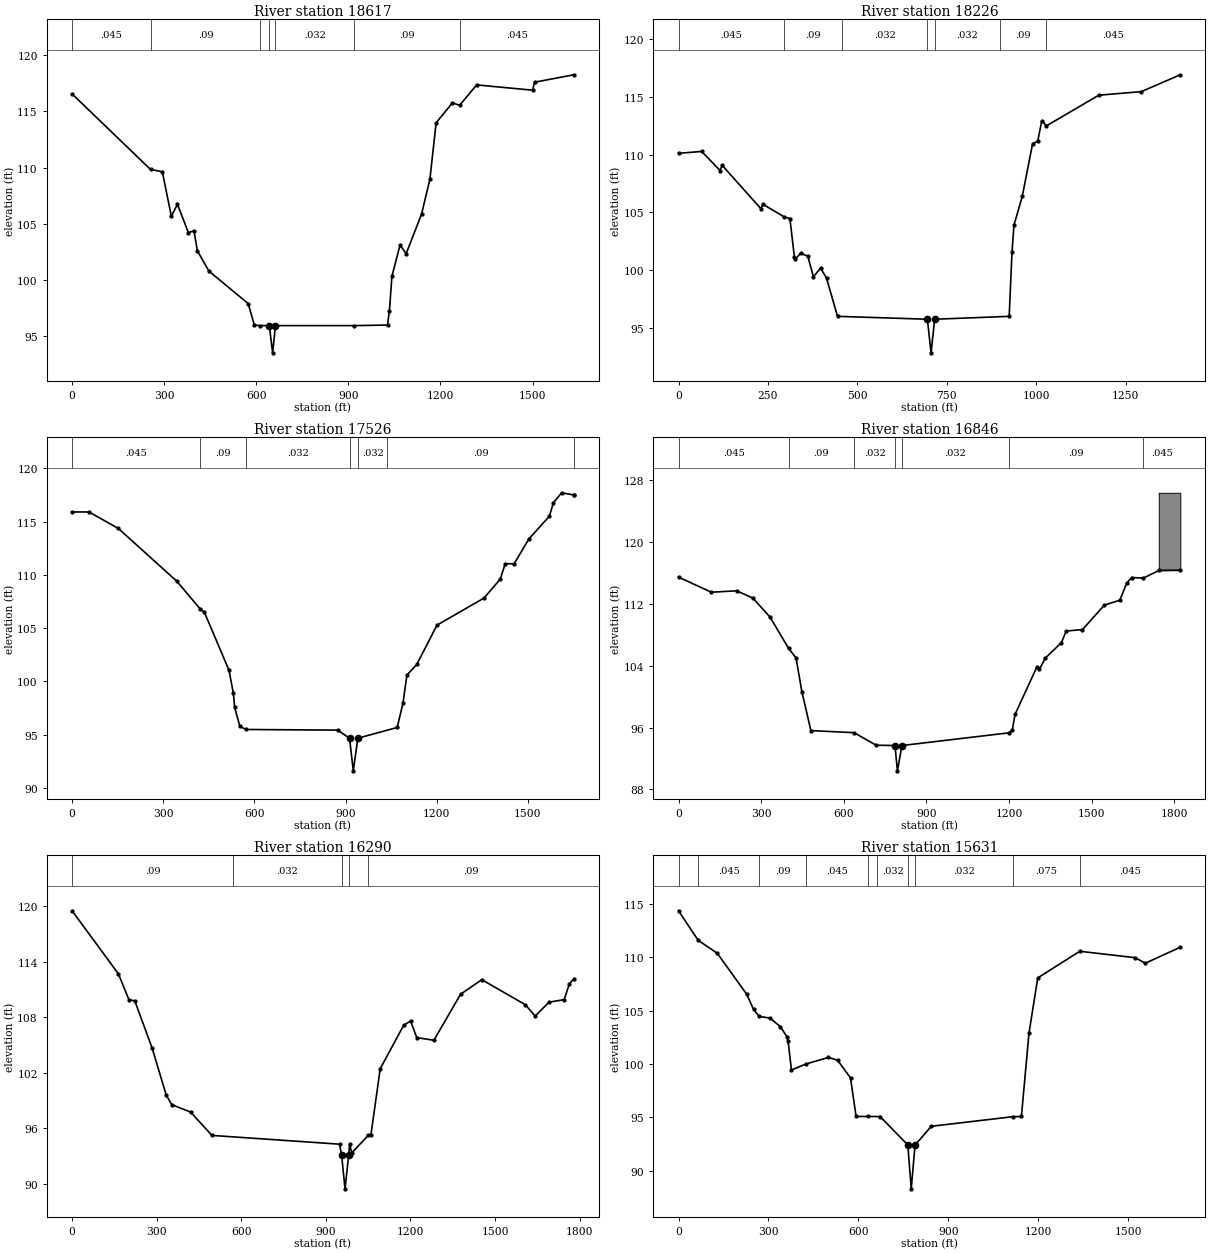
Type RM Length L Ch R = 1 ,18617   ,363.3,391.46,271.98
XS GIS Cut Line= 3
 2353220.0540017  608547.8156905 2353094.2623954  607474.5636284
 2353046.9848762  606922.4708598
#Sta/Elev= 30
       0  116.55  255.67  109.83  293.97  109.63  323.41  105.68  343.45  106.73
   378.8  104.22  397.17  104.37  408.29   102.6  445.65   100.8  573.62   97.91
  593.81      96  613.34   95.95  642.61   95.95  653.31   93.53  662.71   95.95
  919.36   95.95 1027.61      96  1033.9   97.29 1041.99  100.33 1068.55  103.12
 1088.36  102.34 1138.51  105.86 1165.68  108.96    1186  113.98 1239.12  115.75
 1262.65  115.54  1318.1  117.35 1500.09  116.88 1506.89  117.59 1634.71  118.25
#Mann= 7 ,-1 , 0
       0    .045       0  255.67     .09       0  613.34    .032       0
  642.61     .05       0  662.71    .032       0  919.36     .09       0
 1262.65    .045       0
Bank Sta=642.61,662.71
XS Rating Curve= 0 ,0
Exp/Cntr=0.3,0.1

Type RM Length L Ch R = 1 ,18226   ,745.45,700.47,614.78
XS GIS Cut Line= 4
   2353660.25156  608393.5584265 2353592.5288587  608126.4299937
 2353321.6380536  607475.5395869 2353208.7668848  607069.2033792
#Sta/Elev= 30
       0  110.12   64.56  110.28  116.38  108.63  121.67  109.09  230.01  105.33
  236.09   105.7  295.61  104.61  311.26  104.47  323.86  101.12  326.61  100.95
  341.11  101.47  361.31   101.2  376.91   99.43  397.08  100.18  413.59   99.31
  444.26      96  695.41   95.75  705.76   92.84  715.74   95.75  924.03      96
  931.95  101.58  937.47  103.91  960.63  106.39  989.28  110.93 1003.94  111.19
 1015.11  112.94 1028.31   112.5 1174.32  115.15 1293.08  115.46 1402.31  116.92
#Mann= 7 ,-1 , 0
       0    .045       0  295.61     .09       0  457.57    .032       0
  695.41     .05       0  715.74    .032       0  898.74     .09       0
 1028.31    .045       0
Bank Sta=695.41,715.74
XS Rating Curve= 0 ,0
Exp/Cntr=0.3,0.1

Type RM Length L Ch R = 1 ,17526   ,613.6,679.28,685.18
XS GIS Cut Line= 4
 2354676.0920792  607814.1530933 2354278.4424116  607598.0326348
 2353763.9882182  607150.9251722 2353276.4895861  606978.9064442
#Sta/Elev= 30
       0   115.9   55.82   115.9  152.44  114.35  344.63   109.4  422.53  106.77
  435.08  106.51  516.36  101.05  530.73   98.89  534.94   97.56  552.06    95.8
  571.79   95.49  873.94   95.43  913.02   94.67  925.36   91.61  940.26   94.67
 1069.85   95.68 1088.91   97.97 1101.82   100.6 1134.18  101.59  1200.8  105.28
 1355.97  107.83 1409.13  109.61 1425.26  111.05 1454.46  111.03  1503.4  113.38
 1570.65   115.5 1583.51  116.74 1610.73   117.7 1649.98   117.5 1651.14  117.47
#Mann= 7 ,-1 , 0
       0    .045       0  422.53     .09       0  571.79    .032       0
  913.02     .05       0  940.26    .032       0 1037.24     .09       0
 1649.98    .045       0
Bank Sta=913.02,940.26
XS Rating Curve= 0 ,0
Exp/Cntr=0.3,0.1

Type RM Length L Ch R = 1 ,16846   ,431.36,556.29,520.06
XS GIS Cut Line= 6
 2354796.4879926   607501.876193  2354656.311721  607366.7148592
   2354574.01973  607086.1507123 2354398.6376185   606849.969469
 2354363.5611963  606826.5851875 2353735.4990059  606049.6004877
#Sta/Elev= 30
       0  115.44  119.27  113.49  210.72  113.67  269.55  112.75  332.23  110.28
  399.86  106.23  426.91  104.99  447.83  100.66  480.76   95.61  637.52   95.34
  717.94   93.72   786.1   93.68  794.96   90.41  811.31   93.68 1199.77   95.32
 1212.07   95.68 1222.38   97.72 1301.14   103.8 1310.86  103.52 1331.66  104.96
 1390.73  106.98 1408.23  108.48 1467.06  108.66 1546.82  111.83 1602.68  112.45
 1628.01  114.68 1646.22  115.39 1687.84  115.31  1745.5  116.31 1822.53  116.34
#Mann= 7 ,-1 , 0
       0    .045       0  399.86     .09       0  637.52    .032       0
   786.1     .05       0  811.31    .032       0 1199.77     .09       0
 1687.84    .045       0
#Block Obstruct= 1 ,-1
 1744.22 1822.53 126.338
Bank Sta=786.1,811.31
XS Rating Curve= 0 ,0
Exp/Cntr=0.3,0.1

Type RM Length L Ch R = 1 ,16290   ,751.74,658.63,554.99
XS GIS Cut Line= 6
 2355041.0421917   607347.618929 2354948.1682343  606903.7533165
 2354695.6179939  606475.8209647 2354683.9258531  606431.3908298
 2354588.0502989  606279.3929999 2354021.4393002  606072.1747215
#Sta/Elev= 30
       0  119.52  164.42  112.69   201.3  109.92  222.56  109.77  284.19  104.64
  333.73   99.59  353.63   98.54  420.13   97.75  495.98   95.22   948.6   94.27
  955.74   93.11  967.91   89.44  980.92   93.09  984.11   94.29  991.68   93.34
 1050.52   95.22 1059.43   95.22 1092.73  102.44 1176.03  107.14 1200.28  107.59
 1222.36   105.8  1282.9  105.51 1377.61  110.49 1452.97  112.07 1607.61  109.35
  1642.1  108.13 1691.06  109.63 1745.05  109.91 1763.75  111.65 1779.34  112.14
#Mann= 5 ,-1 , 0
       0     .09       0  569.92    .032       0  955.74     .05       0
  980.92    .032       0 1050.52     .09       0
Bank Sta=955.74,980.92
XS Rating Curve= 0 ,0
Exp/Cntr=0.3,0.1

Type RM Length L Ch R = 1 ,15631   ,841.98,881.68,911.52
XS GIS Cut Line= 4
 2355797.2790227  606666.6295438 2355446.2534307  606277.0545718
 2354924.7839527  605935.6440616 2354518.0724429  605601.8781848
#Sta/Elev= 30
       0  114.37   65.61   111.6  129.27  110.38   227.9  106.52   250.1  105.12
  268.98  104.46  304.88   104.3  340.06   103.5  361.82  102.52  365.52  102.13
  376.63   99.43  424.81   99.99  499.64  100.61  530.57  100.35  573.62   98.69
  592.29   95.07  630.86   95.07  672.55   95.06  764.86   92.39  776.22   88.28
  788.96   92.39  843.27   94.15 1115.43   95.05 1143.69   95.07 1168.96  102.89
 1198.23  108.07 1338.38  110.57 1522.87  109.97 1557.06  109.45 1673.81  110.95
#Mann= 10 ,-1 , 0
       0    .045       0   65.61    .045       0  268.98     .09       0
  424.81    .045       0  630.86     .09       0  663.33    .032       0
  764.86     .05       0  788.96    .032       0 1115.43    .075       0
 1338.38    .045       0
Bank Sta=764.86,788.96
XS Rating Curve= 0 ,0
Exp/Cntr=0.3,0.1

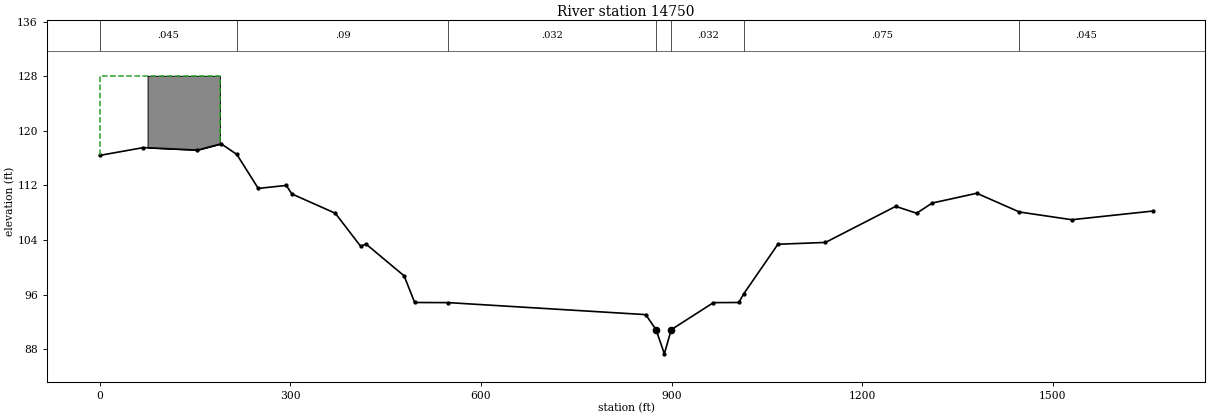
Type RM Length L Ch R = 1 ,14750   ,792.77,693.76,648.83
XS GIS Cut Line= 4
 2356380.4467281   606027.026254 2356019.1683278  605678.4169649
 2355441.5765744   605156.947487 2355266.7845293  604823.0671201
#Sta/Elev= 30
       0  116.41   68.94  117.56  153.88  117.19  191.24  118.11  215.75  116.57
   249.6  111.57  293.68  112.01  302.51  110.76  370.81  107.93  410.75  103.08
  419.08  103.42  479.08   98.75  495.71   94.84  548.87   94.82  859.28   93.06
  875.51   90.85  888.61   87.31  899.35   90.85  965.79   94.82  1005.7   94.84
 1013.64   96.13 1067.26  103.38 1142.11  103.65 1252.64  108.94 1285.56  107.93
 1309.82  109.42 1380.16  110.86 1447.29  108.11 1529.66  106.98 1657.08  108.25
#Mann= 7 ,-1 , 0
       0    .045       0  215.75     .09       0  548.87    .032       0
  875.51     .05       0  899.35    .032       0 1013.64    .075       0
 1447.29    .045       0
#XS Ineff= 2 , 0
       0  189.29  128.09               0
Permanent Ineff=
       F       F
#Block Obstruct= 1 ,-1
   75.41  189.29 128.085
Bank Sta=875.51,899.35
XS Rating Curve= 0 ,0
Exp/Cntr=0.3,0.1