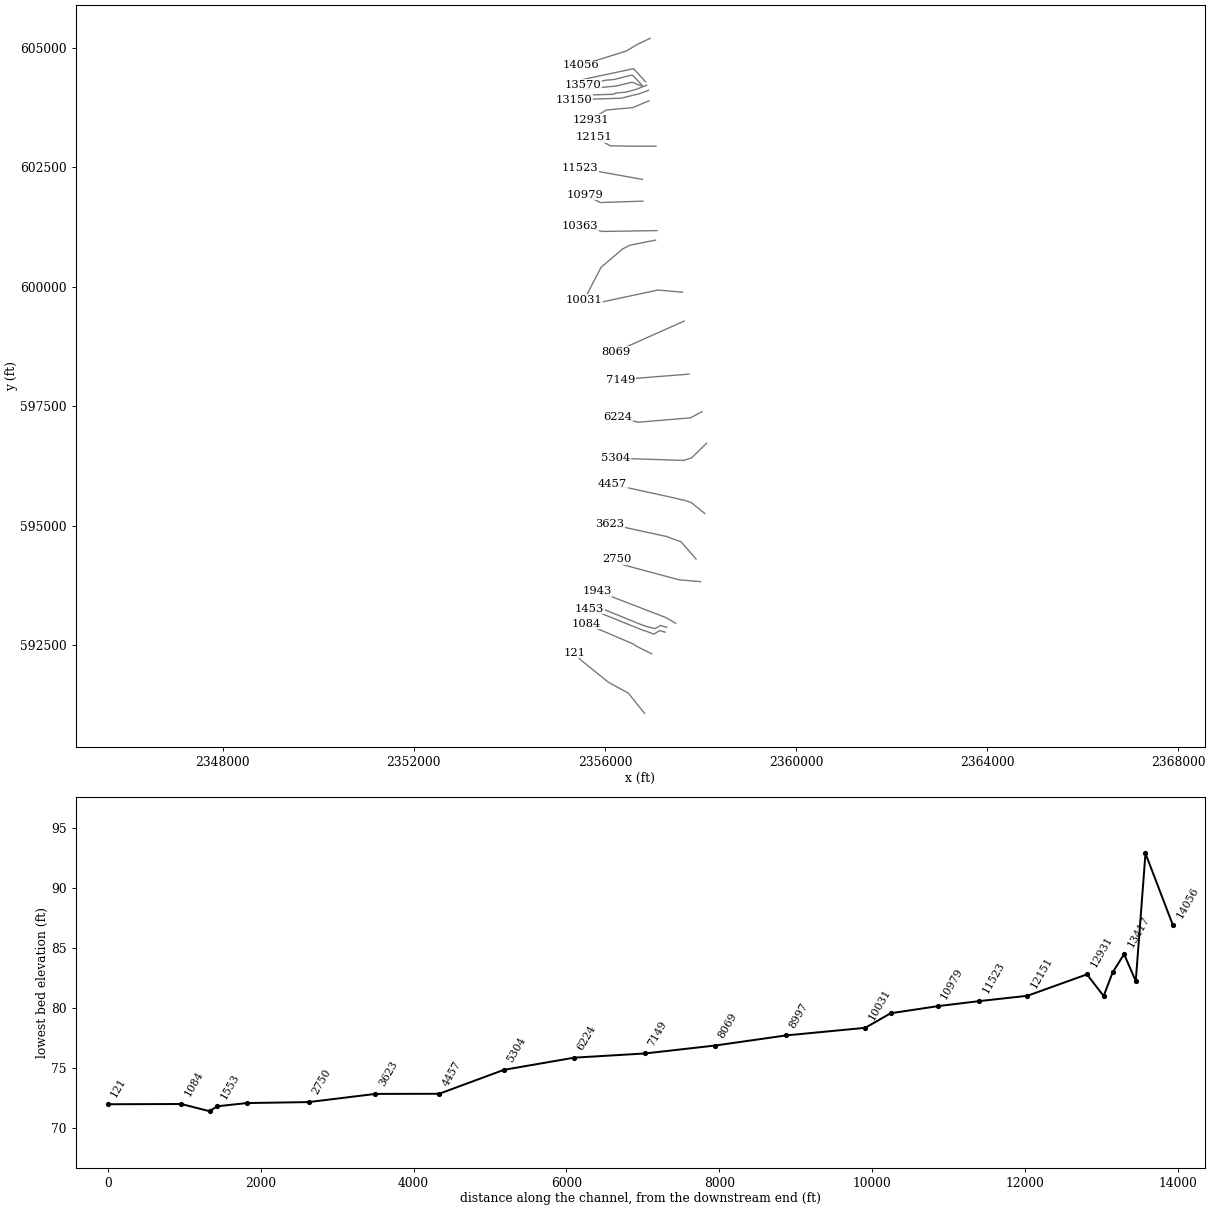
HEC-RAS study DTL_Bear_Creek.prj: DTL_Bear_Creek

--- DTL_Bear_Creek.g01 (geometry) --- (continued)

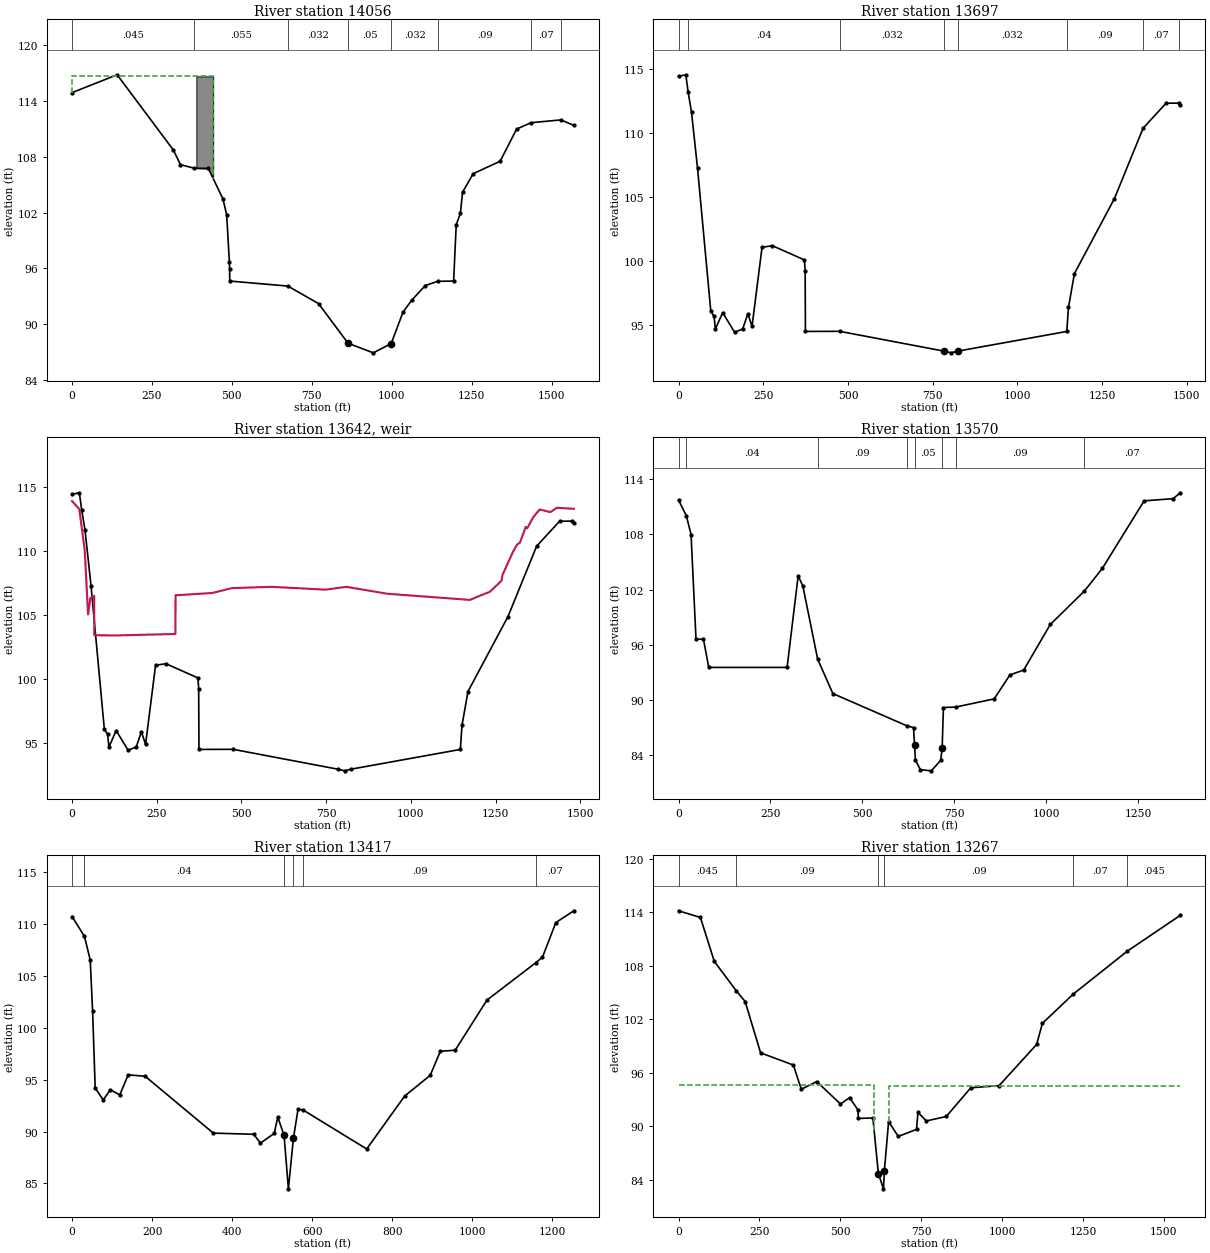
Type RM Length L Ch R = 1 ,14056   ,380.26,358.8,346.75
XS GIS Cut Line= 4
 2356944.8025721  605203.0667217 2356670.1493948  605071.3836914
 2356451.9318017  604939.7006612 2355488.7644946  604634.9485054
#Sta/Elev= 30
       0  114.91  141.03  116.83   316.6  108.74  339.14  107.15  382.22  106.77
  426.25  106.74   471.7  103.49  483.65  101.76  492.15   96.63  492.85    95.9
  493.26   94.62  674.89   94.08  771.02   92.19  863.44   87.92  942.28   86.89
  998.42   87.89 1035.07   91.26 1062.63   92.56 1104.92   94.14 1144.02   94.59
 1193.58   94.62 1201.71   100.7 1214.79   101.9 1221.39  104.18  1254.8  106.18
 1339.13  107.52 1390.55  110.98 1435.64  111.67 1529.19  111.97 1569.69  111.38
#Mann= 8 ,-1 , 0
       0    .045       0  382.22    .055       0  674.89    .032       0
  863.44     .05       0  998.42    .032       0 1144.02     .09       0
 1435.64     .07       0 1529.19    .045       0
#XS Ineff= 2 , 0
       0  441.49  116.66               0
Permanent Ineff=
       F       F
#Block Obstruct= 1 ,-1
  388.82  441.49 116.657
Bank Sta=863.44,998.42
XS Rating Curve= 0 ,0
Exp/Cntr=0.5,0.3

Type RM Length L Ch R = 1 ,13697   ,121.17,127.15,117.83
XS GIS Cut Line= 3
 2356852.6221824   604291.665787 2356599.8990836  604568.0816763
  2355517.928317  604336.4188357
#Sta/Elev= 30
       0  114.43   21.52  114.55   28.44  113.19   38.32  111.62   55.99  107.28
   95.24    96.1  104.69   95.71  108.83   94.71  130.25   95.99  165.35   94.46
  189.29   94.71   204.6    95.9  216.94   94.91  246.46  101.09  277.03  101.21
  371.59   100.1  373.68   99.23  374.54   94.52  475.26   94.53  784.18   92.98
  804.43   92.85  823.56   92.98 1145.94   94.52 1150.89    96.4 1168.51   99.04
 1286.58  104.89 1371.13  110.38 1438.81  112.33 1476.14  112.34 1481.03  112.16
#Mann= 8 ,-1 , 0
       0    .045       0   28.44     .04       0  475.26    .032       0
  784.18     .05       0  823.56    .032       0 1145.94     .09       0
 1371.13     .07       0 1476.14    .045       0
Bank Sta=784.18,823.56
XS Rating Curve= 0 ,0
Exp/Cntr=0.5,0.3

Type RM Length L Ch R = 5 ,13642   ,,,
BEGIN DESCRIPTION:
Earthen Dam
END DESCRIPTION:
IW Pilot Flow=0
#Inline Weir SE= 30
       0   113.9   21.23  113.28   37.34  110.08   47.28  105.06      54  106.33
    65.2   106.5    65.6  103.43  133.27  103.42   304.9  103.53  305.45  106.55
 413.758  106.73 472.354  107.11 588.216  107.21 748.638  106.99  809.62  107.21
 930.272  106.671173.876  106.191232.906  106.82  1267.7  107.69 1270.29  108.13
 1299.83  109.86 1313.39  110.51 1321.95  110.66 1338.92  111.89 1343.08  111.77
 1360.98  112.64 1380.32  113.25 1411.84  113.04 1431.02  113.38 1481.03   113.3
IW Dist,WD,Coef,Skew,MaxSub,Min_El,Is_Ogee,SpillHt,DesHd
53,13,2.6,0,0.95,, 0 ,,,0,0,

Type RM Length L Ch R = 1 ,13570   ,155.21,152.77,143.57
BEGIN DESCRIPTION:
Surveyed Section
END DESCRIPTION:
XS GIS Cut Line= 6
 2356781.5438109  604215.3223509    2356582.4223     604430.6201
 2356552.4139001     604431.1575    2356177.6109     604338.5476
    2356034.1484     604328.4795 2355537.6723091  604231.1175445
#Sta/Elev= 30
       0  111.75   21.29  110.03   34.06  107.98    47.5   96.59    67.8   96.58
   82.12   93.51   295.2   93.51  325.28  103.49   338.1  102.37  378.22   94.42
 419.638   90.66  620.27  87.157 638.997   86.95 641.689   85.06 644.161   83.43
 657.518   82.37  687.39   82.24 712.939   83.39 716.843   84.73 720.249   89.14
  753.44  89.189 858.228   90.08  901.27    92.7  938.52   93.22 1010.86   98.19
 1103.55  101.83 1152.22  104.29 1265.93  111.66 1344.83   111.9 1364.43  112.54
#Mann= 8 ,-1 , 0
       0    .045       0   21.29     .04       0  378.22     .09       0
  620.27     .04       0 641.689     .05       0 716.843     .04       0
  753.44     .09       0 1103.55     .07       0
Bank Sta=641.689,716.843
XS Rating Curve= 0 ,0
Exp/Cntr=0.5,0.3

Type RM Length L Ch R = 1 ,13417   ,171.25,150.12,159.69
XS GIS Cut Line= 4
 2356777.5950125  604200.8434234 2356572.2574948  604285.0844563
 2356237.9258953  604204.7922218 2355552.7248236  604138.3153627
#Sta/Elev= 30
       0  110.72   30.98  108.81   45.39  106.54   51.34  101.59   57.78    94.2
   77.93   93.05   95.59   94.03  119.28   93.53  140.22   95.47  182.67   95.33
  353.07   89.85  453.95   89.74  470.81   88.89  505.25   89.82   514.2   91.39
  529.87   89.64  540.72   84.48  553.17   89.34  564.89   92.16  578.31   92.06
  736.42   88.32  831.21   93.42  895.17   95.42  920.46   97.74  957.53   97.84
 1036.96  102.67 1158.88  106.27 1175.76  106.81 1209.11  110.14  1254.2  111.28
#Mann= 6 ,-1 , 0
       0    .045       0   30.98     .04       0  529.87     .05       0
  553.17     .04       0  578.31     .09       0 1158.88     .07       0
Bank Sta=529.87,553.17
XS Rating Curve= 0 ,0
Exp/Cntr=0.5,0.3

Type RM Length L Ch R = 1 ,13267   ,104.27,117.04,92.84
BEGIN DESCRIPTION:
Surveyed Section
END DESCRIPTION:
XS GIS Cut Line= 6
 2356872.6946033  604221.5762262 2356662.2360697  604137.3928127
 2356440.0853952  604076.5936808    2356239.1913     604057.9506
    2356169.9935     604031.0974 2355355.0547327  604008.7792644
#Sta/Elev= 30
       0  114.16   67.61  113.41  110.54  108.48   178.7  105.17  205.86  103.98
  253.67   98.22  354.94   96.85  379.43   94.13  427.28      95  500.61   92.48
  528.99   93.19  554.67   91.81  555.82   90.86 600.746   90.91  617.82   84.68
 633.461   82.96 636.284   84.98 649.411   90.51 679.251   88.84 735.631   89.63
  740.17   91.53  766.15   90.58  827.79   91.08   903.5    94.3  990.91   94.54
    1107   99.16 1124.81  101.53 1219.55  104.79 1386.93  109.62  1551.2  113.65
#Mann= 6 ,-1 , 0
       0    .045       0   178.7     .09       0  617.82     .05       0
 636.284     .09       0 1219.55     .07       0 1386.93    .045       0
#XS Ineff= 2 , 0
       0  604.61   94.64  649.39       0   94.48
Permanent Ineff=
       F       F
Bank Sta=617.82,636.284
XS Rating Curve= 0 ,0
Exp/Cntr=0.5,0.3

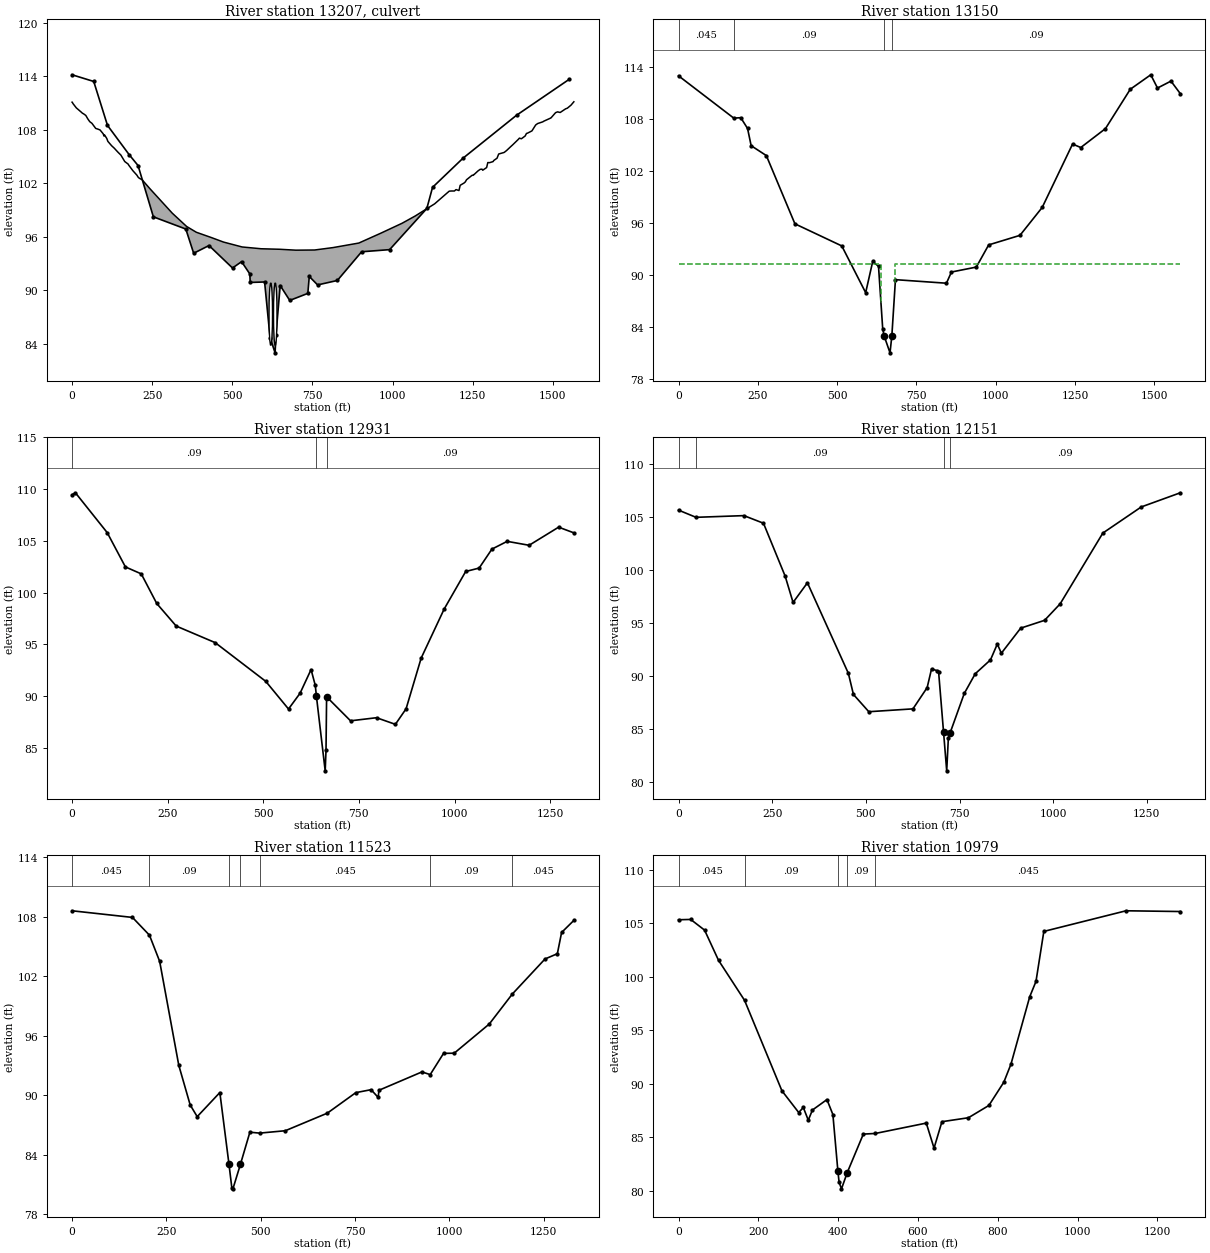
Type RM Length L Ch R = 2 ,13207   ,,,
BEGIN DESCRIPTION:
SR 1716
END DESCRIPTION:
Bridge Culvert--1,0,-1,-1, 0
Deck Dist Width WeirC Skew NumUp NumDn MinLoCord MaxHiCord MaxSubmerge Is_Ogee
50.51,20.08,2.6,0, 109, 109, , , 0.95, 0, 0,0,,
       0     .87    3.01   13.39   18.96   27.95   32.57   35.44    42.8    49.3
   55.15   62.05   73.79   80.07   87.24   97.07    99.5  101.31  108.35  111.66
  123.41  131.75  139.65   144.4  152.29  164.63  164.73  165.13  174.66   177.2
  189.89  202.19  206.38   209.9  219.18  221.46  242.84  312.69  357.39  387.77
  435.08 472.506 530.623  589.76 648.633 698.361 756.839 814.278  894.75  964.26
 1029.73 1070.95 1131.36 1176.77 1183.45 1193.07 1198.02 1207.23 1211.06  1222.9
 1227.02 1230.81  1248.1 1251.72 1253.08 1254.21 1266.56 1273.44 1279.16  1281.3
 1293.56 1297.24 1302.92 1312.81 1313.48 1316.16 1326.05 1331.15 1347.76 1349.15
  1355.8 1371.16 1374.31  1387.2 1392.66 1395.79 1401.99 1413.73 1417.96 1421.17
 1434.69 1435.03 1446.67  1452.9 1468.85  1471.8 1493.77 1494.24 1494.61  1508.7
 1515.02 1520.36 1523.18  1526.8 1540.08 1545.38 1556.07  1556.5 1565.75
  111.09  111.06  110.92  110.44  110.27  109.99  109.84  109.79   109.6   109.2
   108.9  108.71  108.14  108.07  107.97  107.54  107.29  107.41  107.01  106.69
   106.2  105.92  105.61  105.43  105.15  104.41  104.41   104.4  104.15     104
  103.39   102.9  102.66  102.55  102.37  102.26  101.38   98.63   97.14   96.49
   95.89   95.39   94.84   94.64   94.58   94.48    94.5   94.77   95.28    96.4
    97.5   98.32   99.68   101.1  101.12  101.12  101.28  101.17  101.76  102.01
  102.14  102.38  102.88  102.88  102.96  102.96  103.37  103.55  103.57  103.45
  103.75  104.31   104.3  104.41  104.41  104.55   104.8  105.27  105.44  105.47
  105.66  106.18  106.28  106.73  106.92  107.05  106.98  107.29  107.58  107.61
  107.86  107.87  108.53  108.69  108.88  108.95  109.31  109.31  109.33  109.91
     110  109.95  109.93  110.02  110.34  110.41  110.73  110.74  111.13
                                                                                
                                                                                
                                                                                
                                                                                
                                                                                
                                                                                
                                                                                
                                                                                
                                                                                
                                                                                
                                                                        
       0     .87    3.01   13.39   18.96   27.95   32.57   35.44    42.8    49.3
   55.15   62.05   73.79   80.07   87.24   97.07    99.5  101.31  108.35  111.66
  123.41  131.75  139.65   144.4  152.29  164.63  164.73  165.13  174.66   177.2
  189.89  202.19  206.38   209.9  219.18  221.46  242.84  312.69  357.39  387.77
  435.08 472.506 530.623  589.76 648.633 698.361 756.839 814.278  894.75  964.26
 1029.73 1070.95 1131.36 1176.77 1183.45 1193.07 1198.02 1207.23 1211.06  1222.9
 1227.02 1230.81  1248.1 1251.72 1253.08 1254.21 1266.56 1273.44 1279.16  1281.3
 1293.56 1297.24 1302.92 1312.81 1313.48 1316.16 1326.05 1331.15 1347.76 1349.15
  1355.8 1371.16 1374.31  1387.2 1392.66 1395.79 1401.99 1413.73 1417.96 1421.17
 1434.69 1435.03 1446.67  1452.9 1468.85  1471.8 1493.77 1494.24 1494.61  1508.7
 1515.02 1520.36 1523.18  1526.8 1540.08 1545.38 1556.07  1556.5 1565.75
  111.09  111.06  110.92  110.44  110.27  109.99  109.84  109.79   109.6   109.2
   108.9  108.71  108.14  108.07  107.97  107.54  107.29  107.41  107.01  106.69
   106.2  105.92  105.61  105.43  105.15  104.41  104.41   104.4  104.15     104
  103.39   102.9  102.66  102.55  102.37  102.26  101.38   98.63   97.14   96.49
   95.89   95.39   94.84   94.64   94.58   94.48    94.5   94.77   95.28    96.4
    97.5   98.32   99.68   101.1  101.12  101.12  101.28  101.17  101.76  102.01
  102.14  102.38  102.88  102.88  102.96  102.96  103.37  103.55  103.57  103.45
  103.75  104.31   104.3  104.41  104.41  104.55   104.8  105.27  105.44  105.47
  105.66  106.18  106.28  106.73  106.92  107.05  106.98  107.29  107.58  107.61
  107.86  107.87  108.53  108.69  108.88  108.95  109.31  109.31  109.33  109.91
     110  109.95  109.93  110.02  110.34  110.41  110.73  110.74  111.13
                                                                                
                                                                                
                                                                                
                                                                                
                                                                                
                                                                                
                                                                                
                                                                                
                                                                                
                                                                                
                                                                        
BR Coef=-1 , 0 , 0 ,, 0 ,,,0.8,-1,,0,
WSPro=,,,, 1 ,,,, 0 ,,,, 0 ,,,,-1 ,-1 ,-1 , 0 , 0 , 0 , 0 , 0
Multiple Barrel Culv=3,7,10.79,70,0.024,0.9,1,34,3,83.8,84.26, 2,Culvert #1  , 0 ,23
     620     654     634     668
Culvert Bottom n=0.024
BC Design=,, 0 ,, 0 ,,,,,,
BC Use User HTab Curves=0
BC User HTab FreeFlow(D)= 0

Type RM Length L Ch R = 1 ,13150   ,230.86,218.81,230.03
BEGIN DESCRIPTION:
Surveyed Section
END DESCRIPTION:
XS GIS Cut Line= 6
   2356914.78631  604116.3469594 2356718.3583453  604041.5172585
    2356396.8579     603964.8082    2356350.1261     603949.4356
 2355761.9412312  603931.6111354  2355359.731589   603910.565282
#Sta/Elev= 30
       0  112.95  174.21  108.07  196.23  108.12  217.63  106.88  228.99  104.89
  276.88  103.75     367   95.88  514.78   93.33 590.084   87.94 612.429   91.56
 630.606   90.97 643.839   83.76 648.513   82.93  666.87      81 672.675   82.98
 683.963   89.44  844.77   89.03  860.53   90.32  938.91   90.89  977.99   93.45
 1076.59   94.55 1146.75   97.77 1242.51  105.08 1268.38  104.68 1346.21  106.86
  1424.5   111.4  1489.1  113.07  1510.3  111.54 1552.77  112.34 1582.29  110.89
#Mann= 4 ,-1 , 0
       0    .045       0  174.21     .09       0 648.513     .05       0
 672.675     .09       0
#XS Ineff= 2 , 0
       0  638.61   91.26  683.39       0   91.26
Permanent Ineff=
       F       F
Bank Sta=648.513,672.675
XS Rating Curve= 0 ,0
Exp/Cntr=0.5,0.3

Type RM Length L Ch R = 1 ,12931   ,798.36,779.84,775.35
XS GIS Cut Line= 4
 2356922.2283384  603893.7611636 2356580.3910843  603751.5521677
 2356033.1988967  603702.4451765 2355695.6949708  603502.4744451
#Sta/Elev= 30
       0  109.46    8.76  109.65   91.92   105.8  139.48  102.49   180.9  101.82
  221.38   98.96  272.26   96.78  374.14   95.18  506.43   91.44  565.89   88.77
  596.06   90.29  624.87   92.58   635.9   91.05  638.89   89.99  661.79    82.8
  663.94    84.8  665.48   89.95  728.04   87.63  795.98   87.93  845.31   87.29
  873.27   88.79  912.75   93.69  972.79   98.42 1029.12  102.05  1064.3  102.38
 1097.67  104.21 1137.56  104.96 1194.95  104.58 1272.12  106.33 1311.93  105.78
#Mann= 3 , 0 , 0
       0     .09       0  638.89     .05       0  665.48     .09       0
Bank Sta=638.89,665.48
XS Rating Curve= 0 ,0
Exp/Cntr=0.3,0.1

Type RM Length L Ch R = 1 ,12151   ,642.12,627.87,601.31
XS GIS Cut Line= 4
 2357068.9608579  602945.6433457 2356588.4383133  602943.8015476
 2356112.8343371  602953.4421687 2355774.7047889  603133.7619603
#Sta/Elev= 30
       0  105.67   46.61  104.99  174.51  105.15  226.75  104.43  284.59   99.43
  305.73   96.94  344.03    98.8  453.32   90.24  466.87   88.24  507.91   86.61
  625.76   86.88  663.65   88.89  675.37   90.66  690.27   90.49  694.31   90.33
  707.46   84.66  715.83   81.02  720.25   84.13  724.63   84.58  762.74   88.34
  792.01    90.2  832.67   91.51  850.93   93.01   861.7   92.14  913.28   94.51
  977.03   95.25 1018.67   96.81 1132.59   103.5 1235.14  105.97 1339.43  107.31
#Mann= 4 ,-1 , 0
       0    .045       0   46.61     .09       0  707.46     .05       0
  724.63     .09       0
Bank Sta=707.46,724.63
XS Rating Curve= 0 ,0
Exp/Cntr=0.3,0.1

Type RM Length L Ch R = 1 ,11523   ,532.11,544.34,585.63
XS GIS Cut Line= 2
 2356786.7829358  602249.6044714 2355477.4773777  602482.8715536
#Sta/Elev= 30
       0  108.62   160.1  107.95  205.07  106.16  232.16  103.52  282.82   93.04
  313.04   89.04  331.65   87.86  391.67   90.29  415.87   83.06  423.47   80.67
  426.32   80.58  446.34   83.07  471.25   86.29  497.26    86.2  565.14   86.44
  676.42   88.21  751.97   90.28  792.48   90.58  811.26    89.8  813.36   90.52
  927.24   92.37  949.17    92.1  984.55   94.24 1012.86   94.26 1105.72    97.2
 1166.74  100.22 1253.49  103.76 1286.17  104.29  1297.4  106.43 1329.92  107.65
#Mann= 7 ,-1 , 0
       0    .045       0  205.07     .09       0  415.87     .05       0
  446.34     .09       0  497.26    .045       0  949.17     .09       0
 1166.74    .045       0
Bank Sta=415.87,446.34
XS Rating Curve= 0 ,0
Exp/Cntr=0.3,0.1

Type RM Length L Ch R = 1 ,10979   ,624.37,615.73,611.06
XS GIS Cut Line= 3
 2356798.0700527  601794.3574239 2355906.3878192  601764.2584455
 2355579.0614297  601926.0404541
#Sta/Elev= 30
       0  105.33   30.49  105.36   65.27  104.36  100.17  101.54  165.46   97.79
  259.07   89.33  301.12    87.3  312.67   87.77  325.12   86.58  335.43   87.53
  371.87   88.51  386.75   87.11  399.36   81.79  402.33   80.77  408.33   80.16
  422.71   81.68  463.01   85.28  493.12   85.34  620.75   86.31   640.2   83.97
  659.98   86.44   726.3   86.81  777.63   87.96  815.12   90.14  833.01   91.83
  879.95   98.13  895.62   99.56  915.31  104.24 1121.32  106.17 1257.31   106.1
#Mann= 5 ,-1 , 0
       0    .045       0  165.46     .09       0  399.36     .05       0
  422.71     .09       0  493.12    .045       0
Bank Sta=399.36,422.71
XS Rating Curve= 0 ,0
Exp/Cntr=0.3,0.1

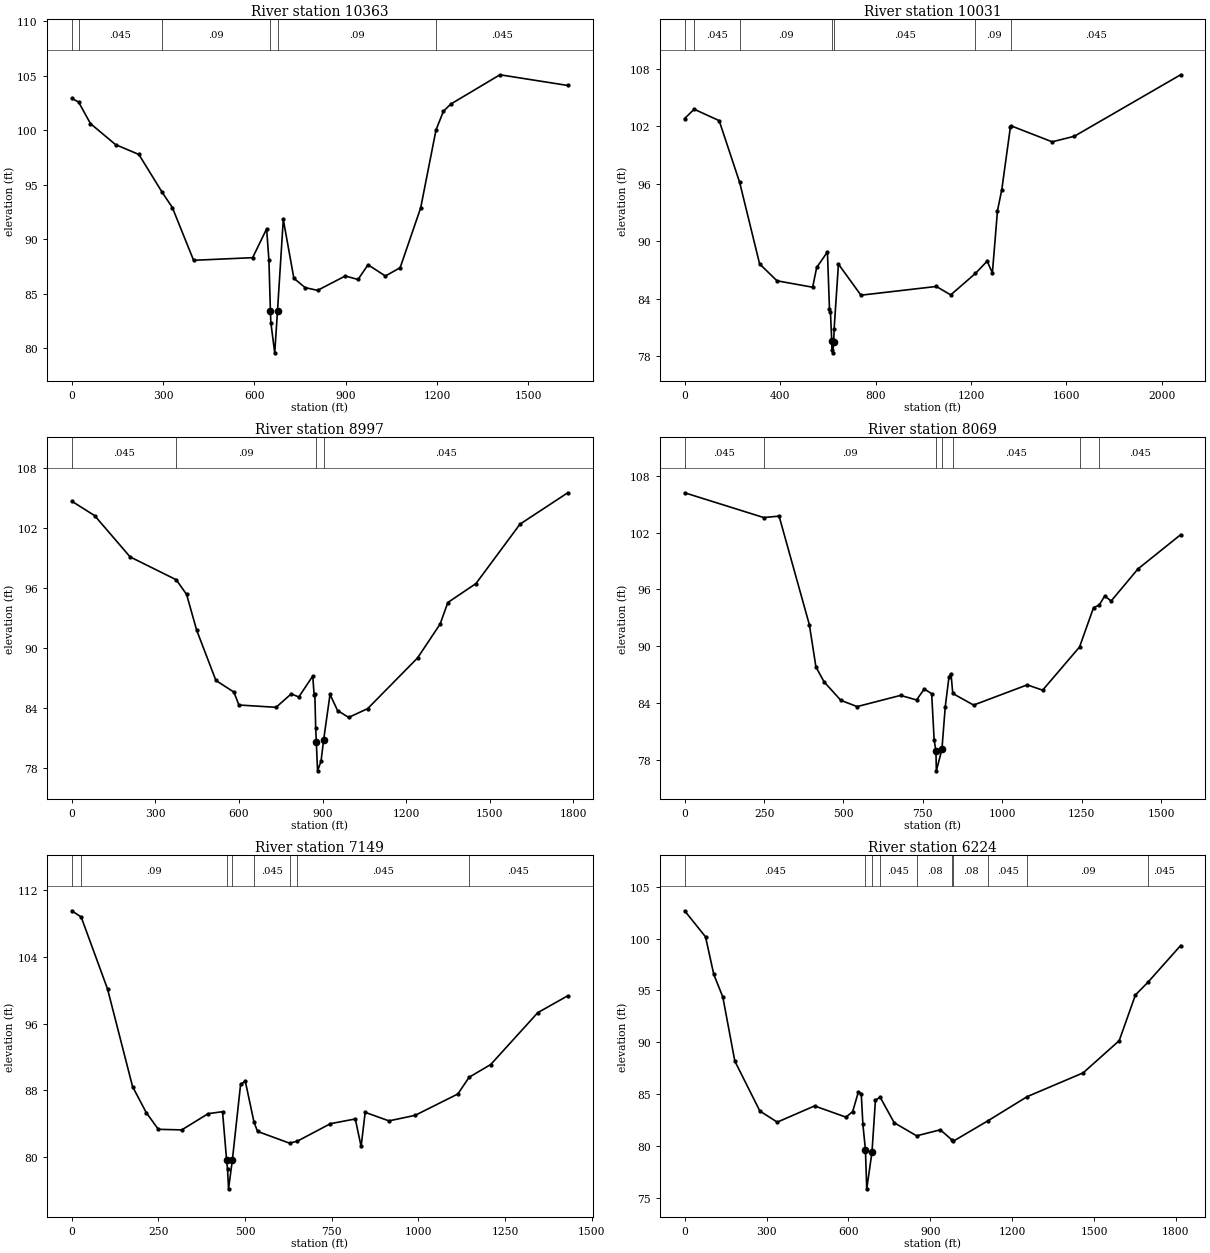
Type RM Length L Ch R = 1 ,10363   ,284.52,332.58,476.71
XS GIS Cut Line= 3
 2357091.5350916  601177.3283678 2355952.8000261  601159.3225748
 2355473.7150054  601263.8629305
#Sta/Elev= 30
       0  102.91   22.32  102.58   61.43   100.6  143.94   98.67  220.41   97.77
   296.2   94.33  330.38    92.9  400.17   88.06  594.08    88.3  640.06   90.94
  647.62   88.08  652.51   83.42  653.95   82.34  666.76   79.57  675.81   83.43
   694.8   91.81  729.59   86.41  766.19   85.56  807.31    85.3  898.33   86.62
  940.24    86.3  973.17   87.65 1030.23   86.62 1078.71   87.38 1146.15   92.87
 1196.51  100.02 1220.83  101.73 1244.92  102.39 1406.48  105.08 1629.24   104.1
#Mann= 6 ,-1 , 0
       0    .045       0   22.32    .045       0   296.2     .09       0
  652.51     .05       0  675.81     .09       0 1196.51    .045       0
Bank Sta=652.51,675.81
XS Rating Curve= 0 ,0
Exp/Cntr=0.3,0.1

Type RM Length L Ch R = 1 ,10031   ,1053.58,1033.79,934.27
BEGIN DESCRIPTION:
Surveyed Section
END DESCRIPTION:
XS GIS Cut Line= 6
 2357061.4361132  600977.9226362    2356535.0552     600874.1768
    2356519.3795     600867.7818    2356373.8943       600794.83
 2355919.3792062  600408.6395421 2355567.7743128  599728.8150348
#Sta/Elev= 30
       0  102.79    39.7  103.76  144.62  102.57   230.5   96.13  314.11   87.63
  387.06   85.87 536.393    85.2  553.32   87.26 598.375   88.88 606.931   82.91
 611.039   82.59 616.429   79.58 617.257   78.65 620.845   78.36 624.729   79.52
 626.339   80.84 644.512   87.61  738.73   84.37 1054.58   85.28 1115.08    84.4
 1218.59   86.64  1267.8   87.92 1289.61   86.69 1310.96   93.18 1328.92   95.36
 1364.88  101.86 1369.69  102.01 1540.14  100.36 1633.04  100.94 2078.44  107.35
#Mann= 7 ,-1 , 0
       0    .045       0    39.7    .045       0   230.5     .09       0
 616.429     .05       0 624.729    .045       0 1218.59     .09       0
 1369.69    .045       0
Bank Sta=616.429,624.729
XS Rating Curve= 0 ,0
Exp/Cntr=0.3,0.1

Type RM Length L Ch R = 1 ,8997    ,874.57,928.12,969.3
XS GIS Cut Line= 3
 2357625.7919573  599886.8346711 2357112.2453951  599932.7142119
 2355876.2888408  599668.6170781
#Sta/Elev= 30
       0  104.64   82.05   103.2  209.34   99.08  374.75    96.8  411.87   95.34
  448.02   91.77  517.09   86.75  581.69   85.59   599.6    84.3  732.97   84.07
  787.38   85.41  814.54    85.1  864.59   87.19  869.49   85.31  872.09    85.4
  875.08   82.04   877.4   80.58  881.86   77.73  894.24   78.68  903.72   80.84
  926.56   85.36  953.53   83.75  993.43   83.06 1061.64   83.94 1240.41   88.99
 1321.61   92.38 1349.27   94.53 1450.18   96.42 1608.14  102.35 1779.45  105.48
#Mann= 4 ,-1 , 0
       0    .045       0  374.75     .09       0   877.4     .05       0
  903.72    .045       0
Bank Sta=877.4,903.72
XS Rating Curve= 0 ,0
Exp/Cntr=0.3,0.1

Type RM Length L Ch R = 1 ,8069    ,962.78,919.71,810.48
XS GIS Cut Line= 2
 2357655.8909356  599281.0927319 2356229.9518364  598645.2518143
#Sta/Elev= 30
       0  106.19  248.87  103.58  297.29  103.73  392.61   92.28  413.31   87.83
  438.82   86.27  491.67   84.32  542.87   83.66  679.71   84.84  730.04   84.36
  754.38   85.52  777.56   85.02  785.46   80.13  791.09   78.96  792.32   76.89
  809.86   79.16  820.39   83.65  832.17   86.81   838.5   87.14  844.03   85.04
  909.58   83.82 1078.42   85.95 1126.92   85.39 1243.09   89.94 1287.31    94.1
 1304.61   94.34 1322.45   95.32 1342.46   94.78 1427.14   98.17 1561.28  101.77
#Mann= 7 ,-1 , 0
       0    .045       0  248.87     .09       0  791.09     .05       0
  809.86     .09       0  844.03    .045       0 1243.09     .09       0
 1304.61    .045       0
Bank Sta=791.09,809.86
XS Rating Curve= 0 ,0
Exp/Cntr=0.3,0.1

Type RM Length L Ch R = 1 ,7149    ,923.36,925.42,918.91
XS GIS Cut Line= 2
 2357758.1670115  598171.6940838 2356331.5358883  598058.3217365
#Sta/Elev= 30
       0  109.49   27.05  108.75  103.29  100.12   175.4   88.46  214.88   85.35
  249.75   83.35  317.41   83.28  393.46   85.22  435.02   85.46  446.66   79.72
  449.41   78.61  452.41   76.23  463.48   79.72   487.2   88.75  500.82   89.08
  525.65   84.24  535.96    83.1  628.55   81.69  651.31   81.94  746.16   84.02
  818.12   84.59  834.86    81.3  846.63   85.38   915.2   84.36  990.61   85.02
 1114.09   87.58 1146.62   89.58  1208.9    91.1 1344.81   97.31 1431.13   99.32
#Mann= 8 ,-1 , 0
       0    .045       0   27.05     .09       0  446.66     .05       0
  463.48     .09       0  525.65    .045       0  628.55     .07       0
  651.31    .045       0 1146.62    .045       0
Bank Sta=446.66,463.48
XS Rating Curve= 0 ,0
Exp/Cntr=0.3,0.1

Type RM Length L Ch R = 1 ,6224    ,856.47,919.34,816.74
XS GIS Cut Line= 4
  2358032.128165   597384.857096 2357789.7430419  597256.0583233
 2356697.2998504  597164.1705782  2356263.813187  597271.9859272
#Sta/Elev= 30
       0  102.68   76.47  100.17  106.83   96.54  139.85   94.37   183.9   88.19
  275.57   83.38  339.34   82.31  476.09   83.87  591.13   82.79  615.81   83.33
  636.71   85.23  647.16   85.06  653.16   82.09   662.4   79.67  667.28   75.88
  686.46   79.42  699.17   84.44  716.63    84.7  767.96   82.25  850.03   80.99
  936.86   81.57  981.07   80.56  984.89   80.48 1110.84   82.43 1255.51   84.77
 1460.38   87.06 1592.34   90.16 1651.92   94.57 1697.34   95.78 1817.47   99.33
#Mann= 10 ,-1 , 0
       0    .045       0   662.4     .05       0  686.46     .08       0
  716.63    .045       0  850.03     .08       0  981.07    .045       0
  984.89     .08       0 1110.84    .045       0 1255.51     .09       0
 1697.34    .045       0
Bank Sta=662.4,686.46
XS Rating Curve= 0 ,0
Exp/Cntr=0.3,0.1

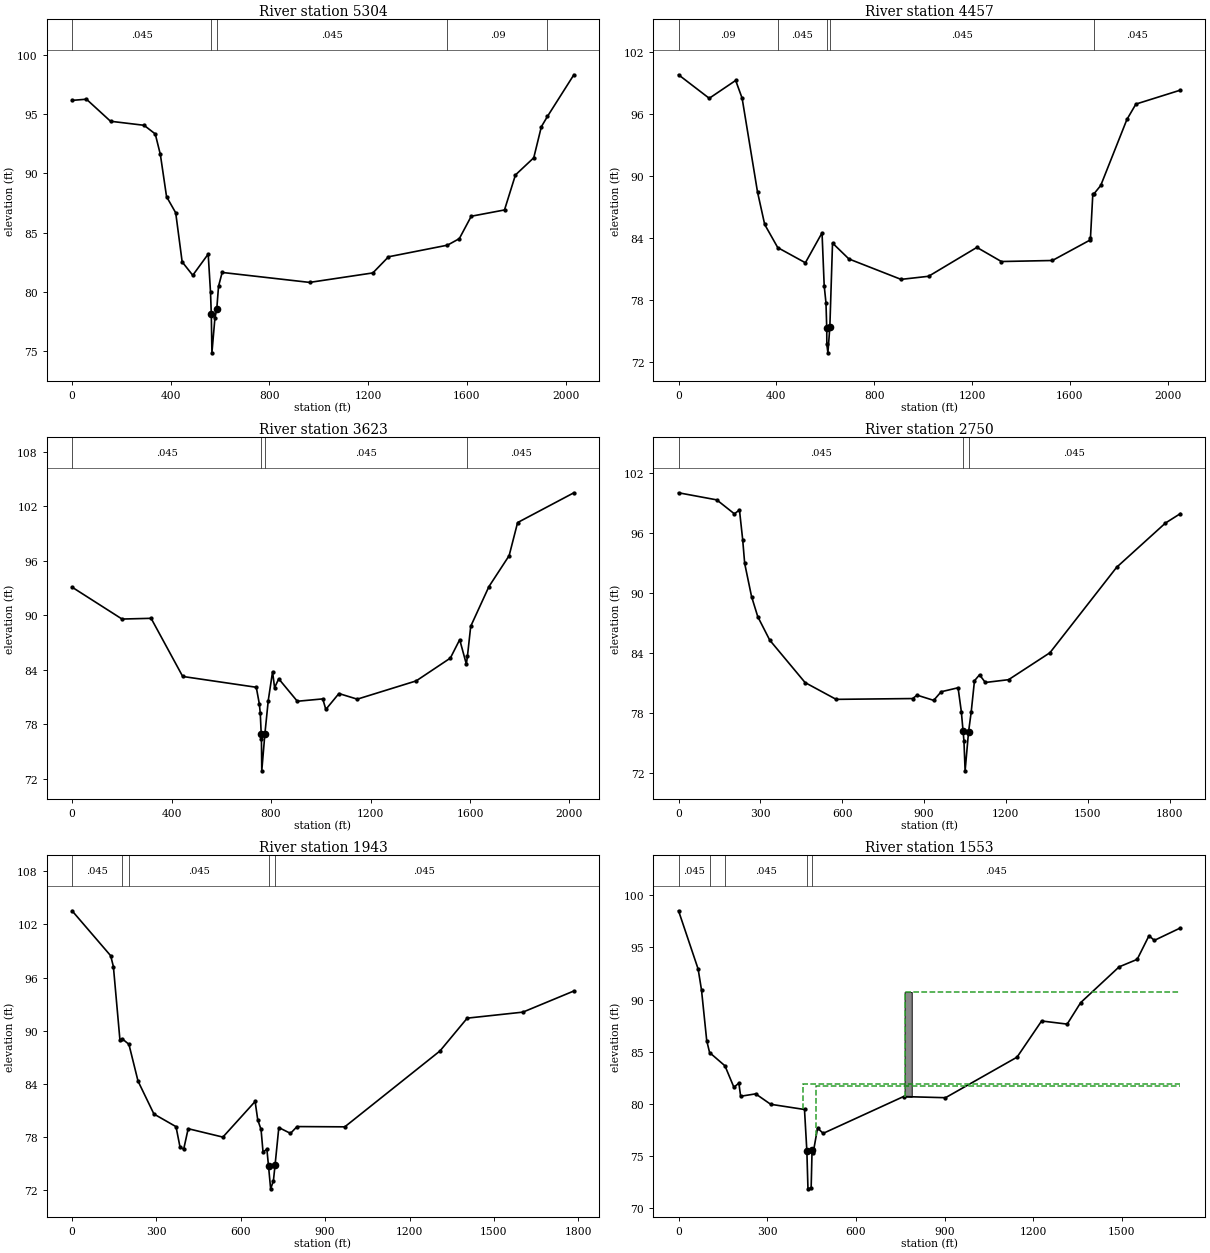
Type RM Length L Ch R = 1 ,5304    ,915.01,847.54,722.28
XS GIS Cut Line= 4
 2358127.7241551  596722.3873726 2357813.9105719  596417.9274166
  2357648.366191  596365.2542045 2356226.1894641   596410.402672
#Sta/Elev= 30
       0   96.16   58.25   96.26  155.85    94.4  291.81   94.06  337.15   93.33
  357.83    91.6  382.95   88.04  420.07   86.68  446.21   82.54   489.2   81.41
  551.74    83.2   561.1      80   564.3   78.15  566.85   74.87   579.1   77.83
  586.36   78.53  593.64   80.48  608.33   81.65  962.75   80.81 1219.17   81.61
 1282.54   82.97 1521.52   83.95 1569.55    84.5 1617.95   86.39 1752.72   86.92
 1797.03   89.87 1871.28   91.32 1902.13   93.94 1926.87   94.81 2033.85   98.32
#Mann= 5 ,-1 , 0
       0    .045       0   564.3     .05       0  586.36    .045       0
 1521.52     .09       0 1926.87    .045       0
Bank Sta=564.3,586.36
XS Rating Curve= 0 ,0
Exp/Cntr=0.3,0.1

Type RM Length L Ch R = 1 ,4457    ,846.1,833.62,824.68
BEGIN DESCRIPTION:
Surveyed Section
END DESCRIPTION:
XS GIS Cut Line= 6
 2358088.5637493  595255.3543779 2357812.7971979  595478.7472456
    2357658.4364     595533.6211    2357561.1943     595550.6255
    2357433.4827      595583.287 2356162.2291351  595861.0963172
#Sta/Elev= 30
       0   99.83  125.58   97.55  233.69   99.28  260.02   97.56  322.95   88.47
  352.37   85.32  405.67   83.08 518.729   81.61 586.807   84.51 595.637   79.39
 602.915   77.73 606.074   75.25  606.42    73.7 610.843   72.88 618.762   75.39
 629.688   83.52 696.622   81.98  909.85      80 1022.54    80.3  1220.1    83.1
  1320.2   81.73 1528.82   81.83 1681.94    83.8 1684.47      84 1694.03   88.23
 1697.39   88.25 1726.47    89.1 1833.55    95.5 1870.31   96.99 2051.97   98.34
#Mann= 5 ,-1 , 0
       0     .09       0  405.67    .045       0 606.074     .05       0
 618.762    .045       0 1697.39    .045       0
Bank Sta=606.074,618.762
XS Rating Curve= 0 ,0
Exp/Cntr=0.3,0.1

Type RM Length L Ch R = 1 ,3623    ,790.98,873.24,797.44
XS GIS Cut Line= 4
 2357907.9698793  594299.7118154  2357594.757481  594660.0761208
 2357286.8989764  594772.3162006 2356102.0311784  595029.6120403
#Sta/Elev= 30
       0   93.09  200.88   89.58  317.79   89.66  444.88   83.26  740.63   82.07
  752.76   80.27  756.69   79.24  760.44   76.98  761.38   76.42  762.78   72.87
  775.37   76.96  788.83   80.61   806.2   83.79   814.2   82.02  830.97      83
  905.74   80.53 1007.98   80.79 1020.31   79.63 1072.98   81.38 1146.71   80.76
 1383.57   82.77 1520.97   85.28 1558.61   87.31 1585.29   84.62 1589.68   85.47
 1602.88   88.78 1676.08   93.15 1757.38   96.56 1791.41   100.2 2017.62  103.48
#Mann= 4 ,-1 , 0
       0    .045       0  760.44     .05       0  775.37    .045       0
 1589.68    .045       0
Bank Sta=760.44,775.37
XS Rating Curve= 0 ,0
Exp/Cntr=0.3,0.1

Type RM Length L Ch R = 1 ,2750    ,816.52,807.23,764.25
XS GIS Cut Line= 4
 2358002.0291866  593825.6529064 2357553.0683085   593864.774984
 2356389.4519943  594177.3034839 2356248.7636979  594295.9494431
#Sta/Elev= 30
       0  100.04  140.09   99.33  204.81   97.93  223.35   98.32   235.2   95.34
  242.51   92.96  267.66   89.65  290.47   87.63  334.38   85.28  464.01   81.03
  577.74   79.35  858.04   79.43  874.62   79.77  935.29   79.25  962.76   80.11
 1024.78   80.51 1036.69   78.13 1043.03   76.19 1046.34   75.18 1050.58   72.19
 1063.08   76.06 1073.03   78.11  1084.9   81.21 1103.42   81.81 1124.68   81.04
 1209.92   81.32 1361.59   84.02 1606.15   92.58 1785.06   97.01 1839.56   97.95
#Mann= 3 ,-1 , 0
       0    .045       0 1043.03     .05       0 1063.08    .045       0
Bank Sta=1043.03,1063.08
XS Rating Curve= 0 ,0
Exp/Cntr=0.3,0.1

Type RM Length L Ch R = 1 ,1943    ,309.62,390.09,318.44
XS GIS Cut Line= 3
 2357484.1379678  592954.8139463  2357261.885473  593080.0564833
 2355834.9027456  593630.0095472
#Sta/Elev= 30
       0  103.55  137.25   98.47  146.96   97.24   170.3   88.91  179.15   89.05
  202.17   88.45  234.58   84.29  291.08   80.57  369.61   79.14   384.1    76.8
  396.97    76.6  412.89   78.91  536.28   77.96  650.94   81.99   660.3   79.91
  672.05   78.82  679.08   76.27  692.75   76.59   698.6   74.68  706.11   72.11
  715.95   73.01  721.97   74.83   735.2   79.04  776.67   78.38  800.03   79.15
  969.77   79.12  1308.3    87.7 1405.15   91.41 1603.12   92.09  1784.4   94.48
#Mann= 5 ,-1 , 0
       0    .045       0  179.15    .035       0  202.17    .045       0
   698.6     .05       0  721.97    .045       0
Bank Sta=698.6,721.97
XS Rating Curve= 0 ,0
Exp/Cntr=0.5,0.3

Type RM Length L Ch R = 1 ,1553    ,111.15,99.28,96.8
BEGIN DESCRIPTION:
Surveyed Section
END DESCRIPTION:
XS GIS Cut Line= 6
 2357293.8578949  592870.8668554 2357163.2735311  592908.1766736
    2357056.2195     592843.3554    2356871.2179     592887.1034
    2356739.9917      592934.253 2355715.9427909  593352.0667733
#Sta/Elev= 30
       0   98.51   66.35   92.92   77.73   90.91   95.39   86.05  105.09   84.91
  157.04   83.64  187.36   81.58  204.14   81.98  210.12   80.72  260.96   80.95
 311.702   79.95 426.182   79.45  434.16   75.47  437.92   71.84 448.683   71.94
 451.765   75.52 455.512   75.29 470.394   77.67  489.32   77.16  761.16   80.69
  903.22   80.58 1145.25   84.47  1228.4   87.94  1314.9   87.64 1360.57    89.7
 1490.62   93.13 1551.78   93.85 1591.76   96.12 1609.74   95.67 1697.73   96.86
#Mann= 5 ,-1 , 0
       0    .045       0  105.09    .035       0  157.04    .045       0
  434.16     .05       0 451.765    .045       0
#XS Ineff= 3 ,-1
   420.4   420.4   81.93   465.4   465.4   81.73  764.79  764.79   90.71
Permanent Ineff=
       F       F       F
#Block Obstruct= 1 ,-1
  764.79  788.95  90.714
Bank Sta=434.16,451.765
XS Rating Curve= 0 ,0
Exp/Cntr=0.5,0.3

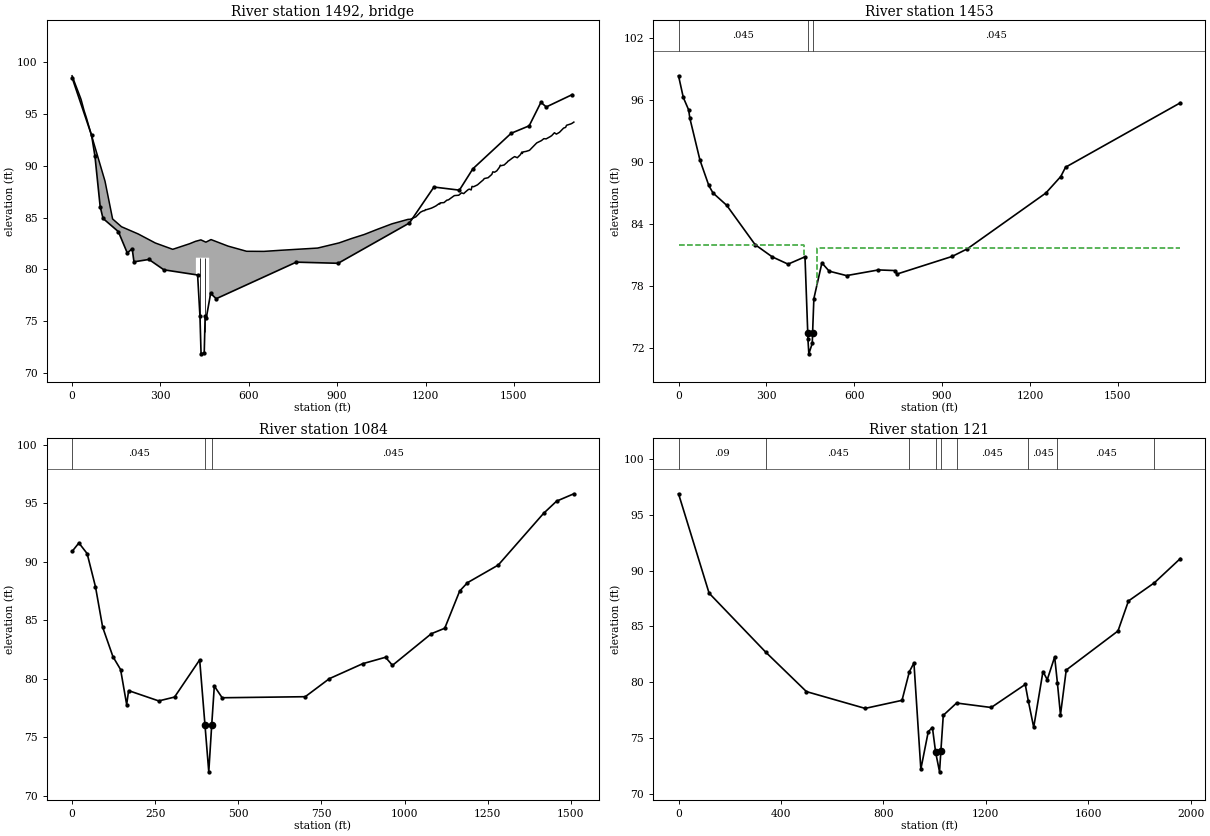
Type RM Length L Ch R = 3 ,1492    ,,,
BEGIN DESCRIPTION:
Parkstown Road
END DESCRIPTION:
Bridge Culvert--1,0,-1,-1, 0
Deck Dist Width WeirC Skew NumUp NumDn MinLoCord MaxHiCord MaxSubmerge Is_Ogee
46,22.5,2.6,0, 110, 110, , , 0.95, 0, 0,0,,
       0    4.54    9.82   28.52   30.84    40.7   49.53   54.04  111.88   137.6
 167.701 224.682 282.591 341.663 399.174 419.839   420.4   420.4 437.321 454.283
   465.4   465.4 471.654 529.445 592.471 651.137 710.223  833.45   906.5  948.62
  991.79 1034.68 1085.96 1140.44 1148.34 1166.95 1173.28 1182.69 1191.81 1197.87
 1199.37 1202.61 1219.54 1226.44 1235.33 1246.49 1248.41 1249.95 1262.67 1272.23
 1278.29 1280.98 1297.51  1297.7 1299.97 1312.53 1314.72 1322.03 1329.77 1334.46
 1344.22 1348.32 1354.92 1357.65 1363.07 1376.25 1387.96 1395.56 1399.45 1412.34
 1416.64 1424.97 1428.38 1434.09 1441.74  1450.7  1453.7 1456.27 1466.83 1477.63
 1479.96 1482.23 1495.25 1502.52 1511.48 1522.17    1527 1528.37 1531.36  1541.2
 1552.36 1553.27 1554.08 1576.71 1577.42 1593.19 1601.62 1609.42 1623.42 1625.08
 1627.53 1637.44 1644.16 1654.58 1668.56 1675.54 1678.53  1692.9 1697.97 1703.48
   98.68   98.36   97.95   96.56   96.37   95.33   94.55   94.09    88.5   84.86
   84.11   83.41   82.54   81.93   82.47   82.71   82.71   82.71   82.84   82.62
   82.78   82.78   82.87   82.24   81.74   81.73   81.84   82.05   82.55   82.97
   83.36   83.84   84.39   84.82   84.83   85.06   85.24   85.51   85.64   85.67
   85.76   85.75    85.9   85.99   86.12   86.35    86.3   86.41   86.44   86.67
   86.71   86.77   87.11   87.11   87.12   87.15    87.2   87.38   87.31   87.44
   87.68   87.74   87.66      88   87.97   88.15   88.44   88.62   88.76   88.84
   88.95   89.16   89.41   89.37    89.5   89.84   90.05      90   90.07   90.35
   90.44   90.47   90.75   90.88   90.77   91.07   91.32   91.18   91.33   91.38
   91.48    91.5   91.52   92.18    92.2   92.42   92.61   92.59   92.81   92.85
   92.88   93.18   93.05   93.22   93.63    93.7    93.9   94.03    94.1   94.21
                                                                                
                                                       0   81.12   81.12   81.12
   81.12       0
                                                                                
                                                                                
                                                                                
                                                                                
                                                                                
                                                                                
                                                                                
                                                                                
       0    4.54    9.82   28.52   30.84    40.7   49.53   54.04  111.88   137.6
 167.701 224.682 282.591 341.663 399.174 419.839   426.9   426.9 437.321 454.283
 471.654   471.9   471.9 529.445 592.471 651.137 710.223  833.45   906.5  948.62
  991.79 1034.68 1085.96 1140.44 1148.34 1166.95 1173.28 1182.69 1191.81 1197.87
 1199.37 1202.61 1219.54 1226.44 1235.33 1246.49 1248.41 1249.95 1262.67 1272.23
 1278.29 1280.98 1297.51  1297.7 1299.97 1312.53 1314.72 1322.03 1329.77 1334.46
 1344.22 1348.32 1354.92 1357.65 1363.07 1376.25 1387.96 1395.56 1399.45 1412.34
 1416.64 1424.97 1428.38 1434.09 1441.74  1450.7  1453.7 1456.27 1466.83 1477.63
 1479.96 1482.23 1495.25 1502.52 1511.48 1522.17    1527 1528.37 1531.36  1541.2
 1552.36 1553.27 1554.08 1576.71 1577.42 1593.19 1601.62 1609.42 1623.42 1625.08
 1627.53 1637.44 1644.16 1654.58 1668.56 1675.54 1678.53  1692.9 1697.97 1703.48
   98.68   98.36   97.95   96.56   96.37   95.33   94.55   94.09    88.5   84.86
   84.11   83.41   82.54   81.93   82.47   82.71   82.76   82.76   82.84   82.62
   82.87   82.87   82.87   82.24   81.74   81.73   81.84   82.05   82.55   82.97
   83.36   83.84   84.39   84.82   84.83   85.06   85.24   85.51   85.64   85.67
   85.76   85.75    85.9   85.99   86.12   86.35    86.3   86.41   86.44   86.67
   86.71   86.77   87.11   87.11   87.12   87.15    87.2   87.38   87.31   87.44
   87.68   87.74   87.66      88   87.97   88.15   88.44   88.62   88.76   88.84
   88.95   89.16   89.41   89.37    89.5   89.84   90.05      90   90.07   90.35
   90.44   90.47   90.75   90.88   90.77   91.07   91.32   91.18   91.33   91.38
   91.48    91.5   91.52   92.18    92.2   92.42   92.61   92.59   92.81   92.85
   92.88   93.18   93.05   93.22   93.63    93.7    93.9   94.03    94.1   94.21
                                                                                
                                                       0   81.12   81.12   81.12
   81.12   81.12       0
                                                                                
                                                                                
                                                                                
                                                                                
                                                                                
                                                                                
                                                                                
                                                                                
Pier Skew, UpSta & Num, DnSta & Num=  ,435.4, 2 ,441.9, 2 , 0 , 0 , 0 ,,
       1       1
      71   81.12
       1       1
      71   81.12
Pier Skew, UpSta & Num, DnSta & Num=  ,450.4, 2 ,456.9, 2 , 0 , 0 , 0 ,,
       1       1
      71   81.12
       1       1
      71   81.12
BR Coef=-1 , 0 , 0 ,, 0 ,,,0.8,-1,,0,
WSPro=,,,, 1 ,,,, 0 ,,,, 0 ,,,,-1 ,-1 ,-1 , 0 , 0 , 0 , 0 , 0
BC Design=,, 0 ,, 0 ,,,,,,
BC Use User HTab Curves=0
BC User HTab FreeFlow(D)= 0

Type RM Length L Ch R = 1 ,1453    ,374.55,369.3,346.46
BEGIN DESCRIPTION:
Surveyed Section
END DESCRIPTION:
XS GIS Cut Line= 6
 2357260.2790585  592768.2648553  2357144.618622  592801.8436917
    2357025.6473     592726.0021    2356843.8131     592795.8882
    2356812.5715     592801.4911 2355677.9333588      593259.572
#Sta/Elev= 30
       0   98.37   16.25   96.27   34.59   95.06   38.61   94.26   73.23   90.19
  103.38   87.74  117.53   87.02  164.49   85.82  261.47   82.01 319.691   80.83
 374.013   80.12 431.799   80.83 441.193   73.48 441.839   72.85 444.983   71.43
 456.639   72.45  457.78   73.49 462.103   76.78 489.513   80.24 514.384   79.44
 573.636   79.01  682.64   79.56  737.91    79.5  745.87   79.16  934.47   80.87
   985.9    81.6 1254.27   87.01  1305.2   88.61 1321.45   89.51 1713.39   95.75
#Mann= 3 ,-1 , 0
       0    .045       0 441.193     .05       0  457.78    .045       0
#XS Ineff= 2 , 0
       0   426.9   81.93   471.9       0   81.73
Permanent Ineff=
       F       F
Bank Sta=441.193,457.78
XS Rating Curve= 0 ,0
Exp/Cntr=0.5,0.3

Type RM Length L Ch R = 1 ,1084    ,955.7,962.66,884.4
XS GIS Cut Line= 4
 2356979.6818437   592315.541197 2356643.6029763   592482.297887
 2356605.1206632   592515.649225  2355609.160408  592941.4954175
#Sta/Elev= 30
       0   90.86   20.53   91.59   45.31   90.68   70.44   87.84      92   84.39
  122.97   81.87  145.95   80.77  164.22   77.78  170.07   78.97  260.66   78.09
  308.26   78.42  383.83    81.6  399.79   76.02  411.19   72.03  419.95   76.01
  427.87   79.36  451.39   78.36  701.35   78.45  773.74   79.99  874.11   81.27
  942.82   81.82  963.69   81.13 1080.44   83.83 1120.94    84.3 1165.86   87.48
 1189.14   88.19 1281.85    89.7 1417.97   94.11 1457.31   95.16 1509.28   95.79
#Mann= 3 , 0 , 0
       0    .045       0  399.79     .05       0  419.95    .045       0
Bank Sta=399.79,419.95
XS Rating Curve= 0 ,0
Exp/Cntr=0.3,0.1

Type RM Length L Ch R = 1 ,121     ,169.88,121.47,272.95
XS GIS Cut Line= 6
 2356831.9314034  591067.8340154 2356708.5598562   591217.733681
  2356492.826007  591490.2395961 2356075.8645833  591717.6458333
  2355478.140625  592199.4322917 2355368.3685812  592335.7534783
#Sta/Elev= 30
       0   96.86  119.31   87.98  340.35   82.71  499.49   79.18  728.69   77.68
  872.65    78.4  901.32   80.96  919.22   81.74  946.16   72.25  975.23   75.61
  991.38   75.97 1003.81   73.77 1019.22   72.01 1024.24   73.83 1033.76   77.06
  1085.7   78.16 1220.91   77.76 1353.84   79.82 1365.69   78.36 1386.86   75.99
 1422.97   80.97 1439.84   80.25  1468.7   82.28 1479.34   79.97 1491.41   77.11
 1513.87   81.11 1715.98    84.6 1756.84   87.28 1858.29   88.91 1959.39   91.07
#Mann= 9 ,-1 , 0
       0     .09       0  340.35    .045       0  901.32     .08       0
 1003.81     .05       0 1024.24     .09       0  1085.7    .045       0
 1365.69    .045       0 1479.34    .045       0 1858.29    .045       0
Bank Sta=1003.81,1024.24
XS Rating Curve= 0 ,0
Exp/Cntr=0.3,0.1