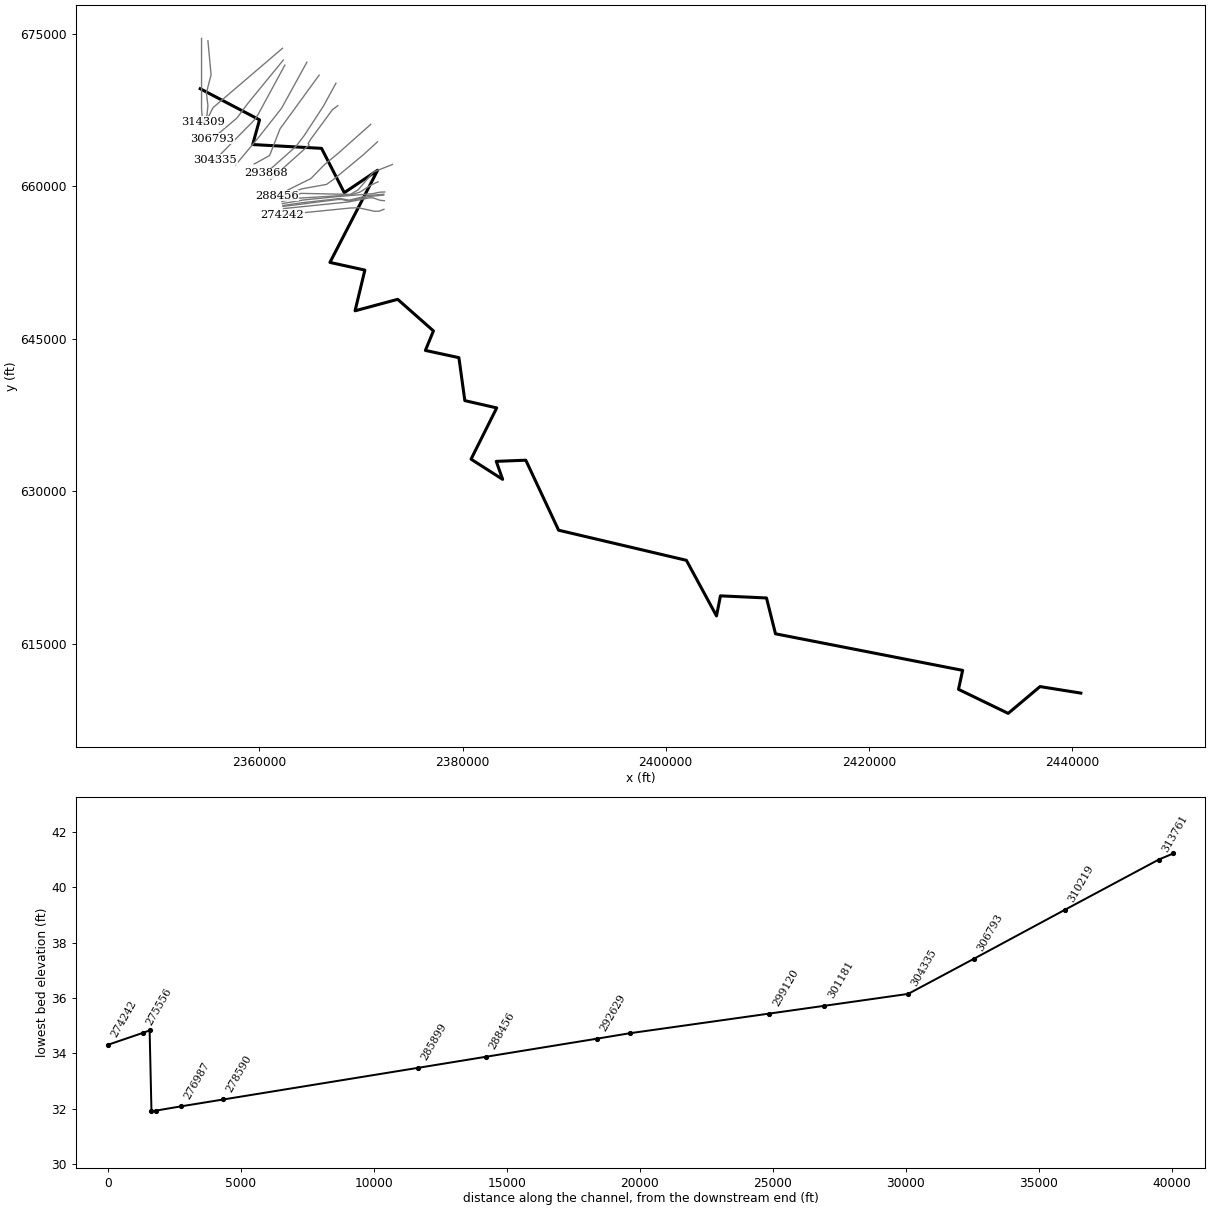
--- DTL_ContentneaCrk.prj (project) ---

Proj Title=DTL_Contentnea_Crk
Current Plan=p02
Default Exp/Contr=0.3,0.1
English Units
Geom File=g01
Flow File=f01
Flow File=f02
Plan File=p02
Plan File=p03
Y Axis Title=Elevation
X Axis Title(PF)=Main Channel Distance
X Axis Title(XS)=Station
BEGIN DESCRIPTION:
END DESCRIPTION:
DSS File=dss
DSS Export Rating Curves= 0
DSS Export Rating Curve Sorted= 0
DSS Export Volume Flow Curves= 0
DXF OffsetX= 0
DXF OffsetY= 0
DXF ScaleX= 1
DXF ScaleY= 10

--- DTL_ContentneaCrk.p02 (plan) ---

Plan Title=Multi_Profile
Program Version=4.00
Short Identifier=Multi_Profil
Geom File=g01
Flow File=f01
Subcritical Flow
K Sum by GR= 0
Std Step Tol= 0.01
Critical Tol= 0.01
Num of Std Step Trials= 20
Max Error Tol= 0.3
Flow Tol Ratio= 0.001
Split Flow NTrial= 30
Split Flow Tol= 0.02
Split Flow Ratio= 0.02
Log Output Level= 0
Friction Slope Method= 1
Unsteady Friction Slope Method= 2
Unsteady Bridges Friction Slope Method= 1
Parabolic Critical Depth
Global Vel Dist= 0 , 0 , 0
Global Log Level= 0
CheckData=True
Encroach Param=-1 ,10,10, 2
Encroach River=Contentnea Creek
Encroach Reach=Main
Encroach Node=314309
       1 2339.28 5138.74
Encroach Node=313761
       1 2389.82 5233.77
Encroach Node=310219
       1 5592.75  8054.7
Encroach Node=306793
       1    5000 7707.69
Encroach Node=304335
       1 5708.85    8300
Encroach Node=301181
       1    8481    9975
Encroach Node=299120
       1  6542.5 8838.11
Encroach Node=293868
       1 5707.05 7706.99
Encroach Node=292629
       1 4215.46    5045
Encroach Node=288456
       1  5513.3  7261.5
Encroach Node=285899
       1 5166.86    7000
Encroach Node=278590
       1    1500    3227
Encroach Node=276987
       1     425    1639
Encroach Node=276069
       1  793.55    2300
Encroach Node=275890
       1  765.37    2900
Encroach Node=275820
       1  769.67    2900
Encroach Node=275556
       1  990.33    3008
Encroach Node=274242
       1    1483    2610
Encroach Node=273104
       1 2829.81  3980.5
Encroach Node=270458
       4       1
Encroach Node=267563
       4       1
Encroach Node=264683
       1    5600 7638.65
Encroach Node=260545
       1    1200    3000
Encroach Node=257454
       1    2900    4300
Encroach Node=256186
       4       1
Encroach Node=250127
       1 1989.94    4800
Encroach Node=247512
       4       1
Encroach Node=245136
       1    2000    5075
Encroach Node=242538
       4       1
Encroach Node=240751
       4     1.9
Encroach Node=237333
       1    1937    4042
Encroach Node=235600
       1    1357    3477
Encroach Node=232974
       4       1
Encroach Node=231649
       4       1
Encroach Node=231243
       1  2211.5 3201.23
Encroach Node=231181
       1 2159.25 3201.23
Encroach Node=230792
       4      .9
Encroach Node=227503
       4       1
Encroach Node=224098
       4       1
Encroach Node=222562
       4       1
Encroach Node=216766
       1    3610    5680
Encroach Node=212952
       1    2540    4670
Encroach Node=202601
       1    1490    4130
Encroach Node=200071
       4       1
Encroach Node=194536
       4       1
Encroach Node=190764
       1    6226    9115
Encroach Node=185318
       4       1
Encroach Node=181846
       4       1
Encroach Node=179346
       4       1
Encroach Node=177148
       1 8404.52 8843.96
Encroach Node=176983
       1 8404.52 8843.96
Encroach Node=175469
       1    7700    8550
Encroach Node=174029
       1 7332.07    7771
Encroach Node=173835
       1 7332.07    7771
Encroach Node=173339
       4       1
Encroach Node=171690
       4       1
Encroach Node=170755
       4     1.9
Encroach Node=164285
       4       1
Encroach Node=160284
       4       1
Encroach Node=158148
       4       1
Encroach Node=153959
       4       1
Encroach Node=148790
       4       1
Encroach Node=146164
       4       1
Encroach Node=143234
       1    3235    5012
Encroach Node=141904
       4       1
Encroach Node=135399
       1    3630    5499
Encroach Node=133511
       4       1
Encroach Node=131914
       4       1
Encroach Node=130490
       1    3750    5345
Encroach Node=129163
       4       1
Encroach Node=125550
       1    4235 5912.35
Encroach Node=124195
       4     1.6
Encroach Node=121029
       4       1
Encroach Node=119241
       4       1
Encroach Node=118927
       1    3596 6482.74
Encroach Node=118808
       1    3590 6487.74
Encroach Node=118470
       1    3200    6730
Encroach Node=116974
       4       1
Encroach Node=115394
       1    5300    8300
Encroach Node=113057
       1    4840    7128
Encroach Node=111488
       4       1
Encroach Node=109606
       1    3444    6011
Encroach Node=107613
       1 3793.17    6550
Encroach Node=105591
       4       1
Encroach Node=104435
       1    4580    7425
Encroach Node=101373
       1    5010    7460
Encroach Node=96819
       4       1
Encroach Node=95250
       1    5140 6774.85
Encroach Node=93160
       4       1
Encroach Node=91310
       4       1
Encroach Node=87246
       4       1
Encroach Node=84436
       1    1186    3086
Computation Interval=1HOUR
Output Interval=1HOUR
Run HTab= 0
Run UNet= 0
Run PostProcess= 0
Run WQNet= 0
UNET Theta= 1
UNET Theta Warmup= 1
UNET ZTol= 0.02
UNET ZSATol= 0.05
UNET MxIter= 20
UNET MaxInSteps= 0
UNET DtIC= 0
UNET DtMin= 0
UNET MaxCRTS= 20
UNET WFStab= 2
UNET SFStab= 1
UNET WFX= 1
UNET SFX= 1
UNET DSS MLevel= 4
UNET DZMax Abort= 100
UNET Convert EG Bridges= 0
UNET Use Existing IB Tables=-1
UNET Froude Reduction=False
UNET Froude Limit= 1
UNET Froude Power= 10
UNET Time Slicing=0,0, 5
Instantaneous Interval=1HOUR
DSS File=dss
Write IC File= 0
Echo Input=False
Echo Output=False
Write Detailed= 0
Detailed Automatic Start=False, 10
WQ ULTIMATE=-1
WQ Max Comp Step=1HOUR
WQ Output Interval=15MIN
WQ Output Selected Increments= 0
WQ Output face flow=0
WQ Output face velocity=0
WQ Output face area=0
WQ Output face dispersion=0
WQ Output cell volume=0
WQ Output cell surface area=0
WQ Output cell continuity=0
WQ Output face conc=0
WQ Output face dconc_dx=0
WQ Output face courant=0
WQ Output face peclet=0
WQ Output face adv mass=0
WQ Output face disp mass=0
WQ Output cell mass=0
WQ Output cell source sink temp=0
WQ Output cell source sink nsm=0
WQ Output MaxMinRange=-1
WQ Daily Max Min Mean=-1
WQ Daily Range=0
WQ Daily Time=0
WQ Create Restart=0
WQ Fixed Restart=0
WQ System Summary=False
Sorting and Armoring Iterations= 10
XS Update Threshold= 0.02
Hydraulics Update Threshold= 0.02
Energy Slope Method= 1
Volume Change Method= 0
XS Weighting Method= 0
Number of US Weighted Cross Sections= 1
Number of DS Weighted Cross Sections= 1
Upstream XS Weight=0.25
Main XS Weight=0.5
Downstream XS Weight=0.25
Number of DS XS's Weighted with US Boundary= 1
Upstream Boundary Weight= 1
Weight of XSs Associated with US Boundary= 0
Number of US XS's Weighted with DS Boundary= 1
Downstream Boundary Weight= 0.5
Weight of XSs Associated with DS Boundary= 0.5
Sediment Output Level= 4
Mass or Volume Output= 0
Output Increment Type= 1
Profile and TS Output Increment= 10
XS Output Flag= 0
XS Output Increment= 10
Disregard all LS=0
Disregard all Conn=0
Disregard all Breaches=0
Disregard all Pumps=0

--- DTL_ContentneaCrk.p03 (plan) ---

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Plan Title=Future
Short Identifier=Future
Geom File=g01
Flow File=f02
Encroach Param=-1 ,0,0, 0

--- DTL_ContentneaCrk.f01 (steady flow) ---

Flow Title=Multi_Profile
Program Version=4.00
Number of Profiles= 6
Profile Names=100-yr,FW,10-yr,25-yr,50-yr,500-yr
River Rch & RM=Contentnea Creek,Main            ,314309
   15580   15580    8190   10860   13120   22220
River Rch & RM=Contentnea Creek,Main            ,306793
   15680   15680    8230   10920   13200   22370
River Rch & RM=Contentnea Creek,Main            ,301181
   15690   15690    8240   10930   13210   22390
River Rch & RM=Contentnea Creek,Main            ,293868
   15790   15790    8280   10990   13290   22550
River Rch & RM=Contentnea Creek,Main            ,285899
   15800   15800    8290   11000   13300   22560
River Rch & RM=Contentnea Creek,Main            ,278590
   15810   15810    8290   11000   13300   22570
River Rch & RM=Contentnea Creek,Main            ,276069
   15830   15830    8300   11010   13320   22610
River Rch & RM=Contentnea Creek,Main            ,267563
   15860   15860    8310   11030   13340   22650
River Rch & RM=Contentnea Creek,Main            ,264683
   15900   15900    8330   11060   13380   22720
River Rch & RM=Contentnea Creek,Main            ,260545
   16020   16020    8380   11130   13470   22910
River Rch & RM=Contentnea Creek,Main            ,247512
   16060   16060    8390   11160   13500   22970
River Rch & RM=Contentnea Creek,Main            ,240751
   17290   17290    8860   11890   14470   24990
River Rch & RM=Contentnea Creek,Main            ,235600
   17300   17300    8870   11900   14480   25020
River Rch & RM=Contentnea Creek,Main            ,231649
   17310   17310    8870   11900   14480   25020
River Rch & RM=Contentnea Creek,Main            ,227503
   17450   17450    8920   11990   14590   25270
River Rch & RM=Contentnea Creek,Main            ,222562
   17470   17470    8920   12000   14600   25300
River Rch & RM=Contentnea Creek,Main            ,216766
   17480   17480    8930   12000   14610   25310
River Rch & RM=Contentnea Creek,Main            ,212952
   17510   17510    8940   12020   14630   25360
River Rch & RM=Contentnea Creek,Main            ,194536
   17540   17540    8950   12030   14660   25410
River Rch & RM=Contentnea Creek,Main            ,190764
   17730   17730    9010   12140   14800   25740
River Rch & RM=Contentnea Creek,Main            ,185318
   17740   17740    9010   12150   14810   25760
River Rch & RM=Contentnea Creek,Main            ,181846
   17770   17770    9020   12170   14830   25810
River Rch & RM=Contentnea Creek,Main            ,173339
   17790   17790    9030   12180   14850   25840
River Rch & RM=Contentnea Creek,Main            ,164285
   17870   17870    9060   12220   14910   25990
River Rch & RM=Contentnea Creek,Main            ,148790
   17900   17900    9060   12240   14930   26030
River Rch & RM=Contentnea Creek,Main            ,146164
   17930   17930    9070   12250   14950   26090
River Rch & RM=Contentnea Creek,Main            ,135399
   17940   17940    9080   12260   14960   26110
River Rch & RM=Contentnea Creek,Main            ,133511
   17950   17950    9080   12260   14970   26120
River Rch & RM=Contentnea Creek,Main            ,130490
   17960   17960    9080   12270   14970   26130
River Rch & RM=Contentnea Creek,Main            ,125550
   17960   17960    9080   12270   14980   26150
River Rch & RM=Contentnea Creek,Main            ,121029
   18120   18120    9130   12360   15100   26420
River Rch & RM=Contentnea Creek,Main            ,119241
   18180   18180    9150   12390   15140   26520
River Rch & RM=Contentnea Creek,Main            ,115394
   18390   18390    9290   12560   15330   26780
River Rch & RM=Contentnea Creek,Main            ,109606
   18410   18410    9300   12570   15350   26800
River Rch & RM=Contentnea Creek,Main            ,105591
   18410   18410    9300   12570   15350   26800
River Rch & RM=Contentnea Creek,Main            ,104435
   18940   18940    9680   13010   15830   27420
River Rch & RM=Contentnea Creek,Main            ,93160
   18950   18950    9680   13020   15840   27430
River Rch & RM=Contentnea Creek,Main            ,87246
   19120   19120    9800   13160   16000   27620
River Rch & RM=Contentnea Creek,Main            ,84436
   19800   19800   10100   13600   16600   28700
Boundary for River Rch & Prof#=Contentnea Creek,Main            , 1
Up Type= 0
Dn Type= 1
Dn Known WS=33.55
Boundary for River Rch & Prof#=Contentnea Creek,Main            , 2
Up Type= 0
Dn Type= 1
Dn Known WS=34.49
Boundary for River Rch & Prof#=Contentnea Creek,Main            , 3
Up Type= 0
Dn Type= 1
Dn Known WS=29.72
Boundary for River Rch & Prof#=Contentnea Creek,Main            , 4
Up Type= 0
Dn Type= 1
Dn Known WS=31.34
Boundary for River Rch & Prof#=Contentnea Creek,Main            , 5
Up Type= 0
Dn Type= 1
Dn Known WS=32.54
Boundary for River Rch & Prof#=Contentnea Creek,Main            , 6
Up Type= 0
Dn Type= 1
Dn Known WS=35.74
DSS Import GetInterval= 0
DSS Import GetPeak= 0
DSS Import FillOption= 0

--- DTL_ContentneaCrk.f02 (steady flow) ---

Flow Title=Future
Program Version=4.00
Number of Profiles= 3
Profile Names=100-yr-10%,100-yr-20%,100-yr-35%
River Rch & RM=Contentnea Creek,Main            ,314309
   25200   32300   39500
River Rch & RM=Contentnea Creek,Main            ,306793
   25400   32500   39800
River Rch & RM=Contentnea Creek,Main            ,301181
   25400   32600   39800
River Rch & RM=Contentnea Creek,Main            ,293868
   25600   32800   40100
River Rch & RM=Contentnea Creek,Main            ,285899
   25600   32900   40100
River Rch & RM=Contentnea Creek,Main            ,278590
   25600   32900   40200
River Rch & RM=Contentnea Creek,Main            ,276069
   25700   32900   40200
River Rch & RM=Contentnea Creek,Main            ,267563
   25700   33000   40300
River Rch & RM=Contentnea Creek,Main            ,264683
   25800   33100   40400
River Rch & RM=Contentnea Creek,Main            ,260545
   26100   33400   40800
River Rch & RM=Contentnea Creek,Main            ,247512
   26100   33500   40900
River Rch & RM=Contentnea Creek,Main            ,240751
   28600   36700   44800
River Rch & RM=Contentnea Creek,Main            ,235600
   28600   36700   44900
River Rch & RM=Contentnea Creek,Main            ,231649
   28700   36700   44900
River Rch & RM=Contentnea Creek,Main            ,227503
   29000   37100   45400
River Rch & RM=Contentnea Creek,Main            ,222562
   29000   37200   45400
River Rch & RM=Contentnea Creek,Main            ,216766
   29000   37200   45400
River Rch & RM=Contentnea Creek,Main            ,212952
   29100   37300   45500
River Rch & RM=Contentnea Creek,Main            ,194536
   29100   37300   45600
River Rch & RM=Contentnea Creek,Main            ,190764
   29500   37900   46300
River Rch & RM=Contentnea Creek,Main            ,185318
   29600   37900   46300
River Rch & RM=Contentnea Creek,Main            ,181846
   29600   38000   46400
River Rch & RM=Contentnea Creek,Main            ,173339
   29700   38000   46500
River Rch & RM=Contentnea Creek,Main            ,164285
   29900   38300   46800
River Rch & RM=Contentnea Creek,Main            ,148790
   29900   38300   46800
River Rch & RM=Contentnea Creek,Main            ,146164
   30000   38400   47000
River Rch & RM=Contentnea Creek,Main            ,135399
   30000   38500   47000
River Rch & RM=Contentnea Creek,Main            ,133511
   30000   38500   47000
River Rch & RM=Contentnea Creek,Main            ,130490
   30000   38500   47000
River Rch & RM=Contentnea Creek,Main            ,125550
   30100   38500   47100
River Rch & RM=Contentnea Creek,Main            ,121029
   30400   39000   47600
River Rch & RM=Contentnea Creek,Main            ,119241
   30500   39100   47800
River Rch & RM=Contentnea Creek,Main            ,115394
   30800   39500   48300
River Rch & RM=Contentnea Creek,Main            ,109606
   30800   39500   48300
River Rch & RM=Contentnea Creek,Main            ,105591
   30800   39500   48300
River Rch & RM=Contentnea Creek,Main            ,104435
   31500   40400   49300
River Rch & RM=Contentnea Creek,Main            ,93160
   31500   40400   49400
River Rch & RM=Contentnea Creek,Main            ,87246
   31700   40700   49700
River Rch & RM=Contentnea Creek,Main            ,84436
   32000   41000   50100
Boundary for River Rch & Prof#=Contentnea Creek,Main            , 1
Up Type= 0
Dn Type= 1
Dn Known WS=36.76
Boundary for River Rch & Prof#=Contentnea Creek,Main            , 2
Up Type= 0
Dn Type= 1
Dn Known WS=38.32
Boundary for River Rch & Prof#=Contentnea Creek,Main            , 3
Up Type= 0
Dn Type= 1
Dn Known WS=39.34
DSS Import GetInterval= 0
DSS Import GetPeak= 0
DSS Import FillOption= 0

--- DTL_ContentneaCrk.g01 (geometry) ---

Geom Title=DTL_Contentnea_Crk
Program Version=4.00

River Reach=Contentnea Creek,Main
Reach XY= 30
2354184.39331055669615.2404785162360019.62567139666554.018493652
2359346.88269043664123.4628906252366124.22650146663748.028930664
2368361.63970947659383.8795166022371645.05987549661595.251098633
2366948.87927246652521.9005126952370386.37927246651766.692077637
2369422.83752441647760.6157226562373617.71612549648889.087890625
 2377135.5112915 645781.449096682376343.41052246643860.876098633
2379642.02148438643149.0704956052380225.78887939638919.469909668
2383363.80987549 638203.324096682380837.76812744633157.751098633
2383945.40710449 631172.074096682383320.40710449632942.907287598
 2386226.2230835633055.7545166022389455.38970947626165.563476563
2402031.34448242 623203.324096682404995.75427246617730.233703613
2405384.20910645619705.0601196292409915.45910645 619496.72668457
2410800.87567139615970.2510986332429218.84448242612372.160888672
2428813.02850342610503.6713256842433702.35150146608138.219909668
2436836.03210449610774.9384765632440853.88470459610133.156494141

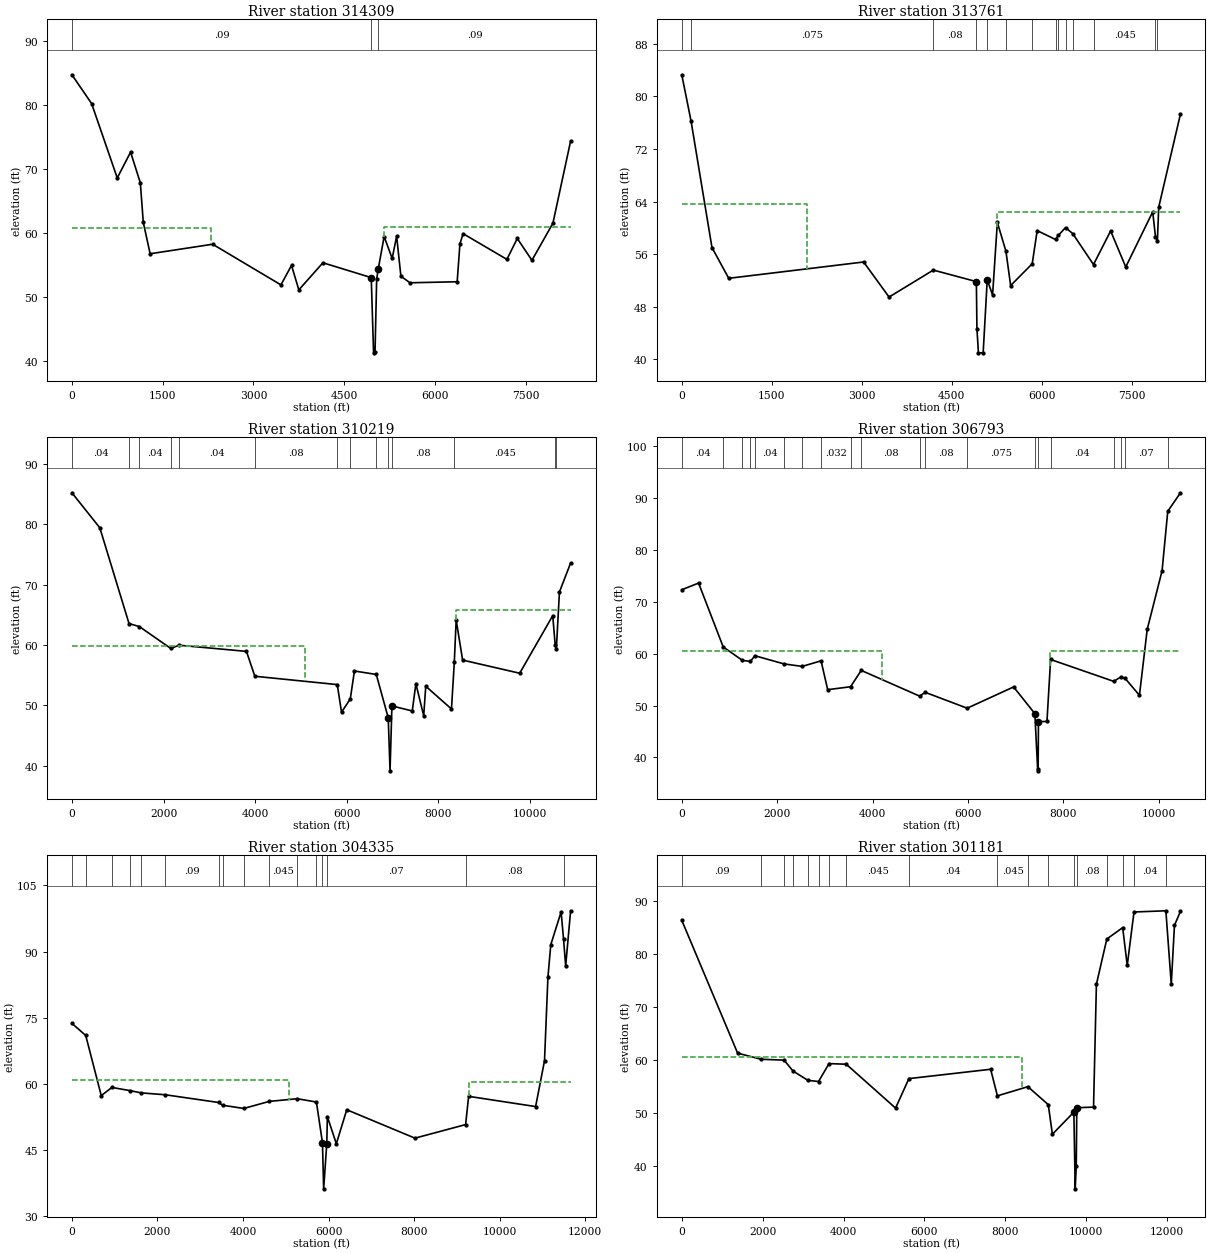
Type RM Length L Ch R = 1 ,314309  ,896.52,547.53,519.59
BEGIN DESCRIPTION:
Tie in to DTL_Contentnea_DS - Wilson Co.
END DESCRIPTION:
XS GIS Cut Line= 3
 2354313.5256958674576.454711914 2354313.5256958667644.889099121
2354414.73931885666339.720703125
#Sta/Elev= 30
       0   84.72  325.44   80.22  749.22   68.58  969.57   72.62 1130.61   67.81
 1179.44   61.63 1292.38   56.72 2325.75   58.21 3453.97   51.85 3628.72    54.9
 3749.74   51.07 4147.69   55.31 4946.04   52.99 4984.81   41.22 5008.71   41.29
 5035.67   52.73 5061.41   54.31 5159.19   59.41 5291.98   55.99 5365.77   59.46
 5436.45    53.2 5587.61   52.18 6366.06   52.34 6411.97   58.29 6464.76   59.86
 7187.86   55.84 7359.16   59.11 7601.78    55.7 7948.35    61.5 8240.65   74.35
#Mann= 3 , 0 , 0
       0     .09       0 4946.04     .05       0 5061.41     .09       0
#XS Ineff= 2 , 0
         2305.61   60.74 5162.75            60.9
Permanent Ineff=
       F       F
Bank Sta=4946.04,5061.41
XS Rating Curve= 0 ,0
Exp/Cntr=0.3,0.1

Type RM Length L Ch R = 1 ,313761  ,2812.59,3542.53,1916.8
XS GIS Cut Line= 6
2354939.47668457674335.718688965 2355251.8203125670987.394470215
2354789.55169678669213.2824707032354939.47668457667963.907714844
2354852.02050781667026.876708984 2354489.7019043666189.795715332
#Sta/Elev= 30
       0   83.27   155.4   76.19  502.89   57.01  782.19   52.33  3030.2   54.81
 3454.13   49.48 4191.73   53.58 4908.77   51.83 4918.39   44.67 4943.44      41
 5022.17      41 5090.17   52.09 5179.13   49.79 5258.65   60.82 5401.71   56.45
  5480.2   51.23 5839.67   54.54 5922.41   59.58 6228.59   58.23 6273.47   58.84
  6394.8   60.04  6515.3   59.12 6861.01   54.42 7146.35   59.53  7398.2   54.05
 7847.29   62.43 7893.98   58.64 7925.56   58.06 7947.98   63.16 8310.33   77.32
#Mann= 14 ,-1 , 0
       0    .045       0   155.4    .075       0 4191.73     .08       0
 4908.77     .05       0 5090.17     .09       0 5401.71    .032       0
 5839.67     .07       0 6228.59    .045       0 6273.47     .04       0
  6394.8    .032       0  6515.3     .04       0 6861.01    .045       0
 7893.98    .035       0 7925.56    .045       0
#XS Ineff= 2 , 0
       0 2079.57   63.58 5253.16       0   62.41
Permanent Ineff=
       F       F
Bank Sta=4908.77,5090.17
XS Rating Curve= 0 ,0
Exp/Cntr=0.3,0.1

Type RM Length L Ch R = 1 ,310219  ,2465.4,3425.18,2890.41
XS GIS Cut Line= 3
2362278.12231445673597.3408813482355444.47772217667756.477478027
2354585.63171387666061.137878418
#Sta/Elev= 30
       0   85.22  609.39   79.42 1246.92   63.57 1473.44   63.06 2160.61   59.44
 2337.03   59.98 3811.67   58.96 3994.51   54.84 5794.66   53.46 5887.68   48.89
 6078.89   51.09 6169.31   55.71 6646.27   55.14 6907.63   47.96    6947   39.18
 6988.22   49.93 7432.06   49.09  7511.4   53.62 7682.17   48.29 7726.82   53.19
 8288.58   49.42 8350.58   57.21 8391.11   64.16 8531.69   57.52 9777.95   55.34
10499.78   64.8710553.66   59.96 10578.7   59.3410646.17    68.810890.16   73.59
#Mann= 14 ,-1 , 0
       0     .04       0 1246.92     .09       0 1473.44     .04       0
 2160.61     .09       0 2337.03     .04       0 3994.51     .08       0
 5794.66    .032       0 6078.89     .08       0 6646.27     .08       0
 6907.63     .05       0 6988.22     .08       0 8350.58    .045       0
10553.66    .035       0 10578.7    .045       0
#XS Ineff= 2 , 0
         5100.17   59.91 8391.11           65.75
Permanent Ineff=
       F       F
Bank Sta=6907.63,6988.22
XS Rating Curve= 0 ,0
Exp/Cntr=0.3,0.1

Type RM Length L Ch R = 1 ,306793  ,1746.19,2458.77,2282.95
XS GIS Cut Line= 4
2362360.85412598672439.096130371 2358853.0269165668153.590087891
2357794.06011963666730.6035156252355394.83868408664695.401916504
#Sta/Elev= 30
       0   72.31  352.35    73.6  869.06   61.28  1271.7    58.7 1439.02   58.49
 1531.06    59.6 2147.03   58.01 2524.57   57.54 2920.93   58.61 3059.65   53.05
 3540.04   53.62  3762.8   56.77 4992.66   51.79 5102.47   52.55 5985.13   49.48
  6958.2   53.58 7404.28   48.44 7464.16   37.41 7473.02   37.71 7479.58    46.9
 7657.79   46.92 7734.76   58.87 9056.65   54.66 9200.97   55.46 9290.91   55.29
  9597.5   51.97 9760.48   64.6810071.88   75.9610191.35   87.4410458.03      91
#Mann= 20 ,-1 , 0
       0     .04       0  869.06     .09       0  1271.7     .04       0
 1439.02     .09       0 1531.06     .04       0 2147.03     .09       0
 2524.57     .04       0 2920.93    .032       0 3540.04    .032       0
  3762.8     .08       0 4992.66    .032       0 5102.47     .08       0
 5985.13    .075       0 7404.28     .05       0 7479.58     .08       0
 7734.76     .04       0 9056.65     .07       0 9200.97     .04       0
 9290.91     .07       010191.35    .045       0
#XS Ineff= 2 , 0
       0    4200    60.5 7726.88       0    60.5
Permanent Ineff=
       F       F
Bank Sta=7404.28,7479.58
XS Rating Curve= 0 ,0
Exp/Cntr=0.3,0.1

Type RM Length L Ch R = 1 ,304335  ,2648.85,3153.06,3033.34
BEGIN DESCRIPTION:
Surveyed Section
END DESCRIPTION:
XS GIS Cut Line= 6
2362511.71472168671941.1096801762359870.24353027667069.825500488
2359732.27288818666882.4680786132359652.80249023666742.235900879
2359616.73291016666649.0092773442355675.27852149662643.861583019
#Sta/Elev= 30
       0    73.7  323.18   70.95  685.61   57.31  935.46   59.16 1362.06   58.43
  1615.9   57.93 2187.0557.49306 3428.0655.74556 3524.43   55.12 4018.01   54.39
 4612.66   55.99 5266.07    56.6 5716.17   55.855857.203 46.62065885.408 36.1498
 5958.27 46.40475972.373 52.5334 6181.91   46.38 6425.44    54.1 8019.61   47.65
 9204.17   50.73 9274.84   57.1410840.64   54.8211048.46    65.211128.07   84.11
11195.36   91.5611436.72   98.9911493.46   92.8711543.27   86.7311658.85   99.25
#Mann= 16 ,-1 , 0
       0     .04       0  323.18     .09       0  935.46     .04       0
 1362.06     .05       0  1615.9     .07       0 2187.05     .09       0
 3428.06     .08       0 3524.43     .04       0 4018.01     .08       0
 4612.66    .045       0 5266.07     .04       0 5716.17     .08       0
5857.203     .05       0 5958.27     .07       0 9204.17     .08       0
11493.46     .04       0
#XS Ineff= 2 , 0
         5066.91    60.9 9276.67           60.43
Permanent Ineff=
       F       F
Bank Sta=5857.203,5958.27
XS Rating Curve= 0 ,0
Exp/Cntr=0.3,0.1

Type RM Length L Ch R = 1 ,301181  ,2199.44,2061.3,2239.29
XS GIS Cut Line= 4
2364677.34368896672223.9935302732362195.39050293667706.838500977
2359994.72528076664910.5045166022357678.23547363662130.716918945
#Sta/Elev= 30
       0   86.34 1380.76    61.3 1961.86   60.15 2530.32   59.98 2749.8157.93038
 3117.28   56.18 3381.16   55.95 3641.35   59.33 4066.7759.21389  5286.6   50.94
 5615.54    56.5  7636.8   58.26 7804.29   53.25 8557.72   54.98 9062.06   51.59
 9163.53   46.01 9694.64   50.18 9728.38   35.72    9754   40.05 9767.39   51.01
10181.24   51.1310252.32   74.2810509.72   82.8210901.84   84.9611014.52   77.84
11181.76   87.9111969.71   88.1412103.25   74.29 12182.2    85.412331.01   88.04
#Mann= 18 ,-1 , 0
       0     .09       0 1961.86     .04       0 2530.32     .09       0
 2749.81    .045       0 3117.28     .09       0 3381.16     .07       0
 3641.35     .05       0 4066.77    .045       0 5615.54     .04       0
 7804.29    .045       0 8557.72     .09       0 9062.06     .08       0
 9694.64     .05       0 9767.39     .08       010509.72     .04       0
10901.84     .08       011181.76     .04       011969.71     .08       0
#XS Ineff= 2 , 0
         8417.72    60.5
Permanent Ineff=
       F       F
Bank Sta=9694.64,9767.39
XS Rating Curve= 0 ,0
Exp/Cntr=0.3,0.1

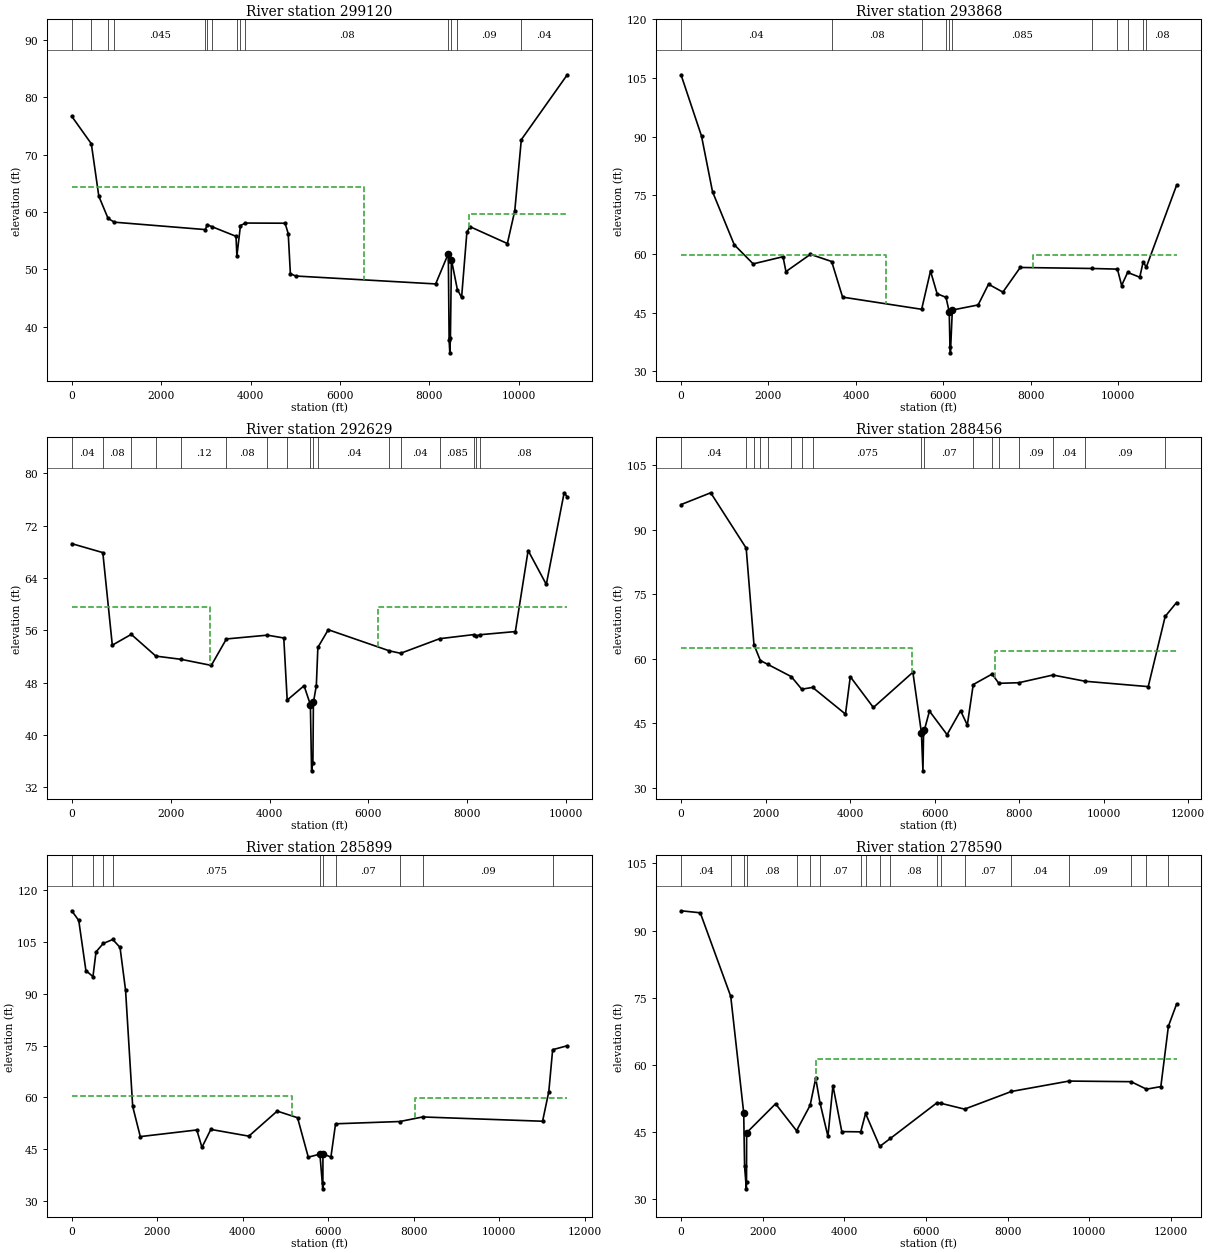
Type RM Length L Ch R = 1 ,299120  ,2897.42,5251.82,3195.94
XS GIS Cut Line= 4
2365883.78009033670953.6514892582362036.61328125 665666.26348877
2361010.70227051663042.2985229492359494.20216324662206.279328661
#Sta/Elev= 30
       0   76.66  437.87   71.88  605.52   62.74   812.4   58.87  953.54   58.21
 2988.42   56.92 3032.87   57.77 3139.56   57.42 3675.27   55.75 3695.24   52.32
 3775.26   57.62 3886.39   58.06 4773.42   58.03 4844.11   56.22 4892.21   49.26
 5006.95   48.83 8143.32   47.45 8426.26   52.72 8444.52   37.67    8460   35.44
 8473.42   38.01 8496.27   51.68 8628.5246.47527 8723.66    45.1 8841.72   56.43
 8910.39   57.43 9747.81   54.49 9913.68   60.1910059.94   72.5911087.96    83.9
#Mann= 14 ,-1 , 0
       0    .045       0  437.87     .07       0   812.4     .09       0
  953.54    .045       0 2988.42     .04       0 3032.87    .032       0
 3139.56    .045       0 3695.24     .05       0 3775.26    .032       0
 3886.39     .08       0 8426.26     .05       0 8496.27     .08       0
 8628.52     .09       010059.94     .04       0
#XS Ineff= 2 , 0
          6542.5   64.31 8896.93            59.7
Permanent Ineff=
       F       F
Bank Sta=8426.26,8496.27
XS Rating Curve= 0 ,0
Exp/Cntr=0.3,0.1

Type RM Length L Ch R = 1 ,293868  ,780.58,1239.01,1002.46
XS GIS Cut Line= 5
2367539.86328125 670155.699096682366298.88647461667888.848327637
2364429.14849854665026.3289184572363601.83068848663934.269470215
2360640.03308105661303.399108887
#Sta/Elev= 30
       0   105.8  468.36   90.14  720.49   75.91  1217.7   62.35 1650.52   57.47
 2332.99    59.3 2399.96    55.5 2960.07   59.91 3445.82   58.07 3695.91   48.97
 5504.25   45.86  5706.9   55.64 5857.85   49.84 6060.79   48.92 6135.61   45.21
 6152.09   36.12 6163.38   34.73 6205.88   45.67 6796.29   46.97 7033.96   52.27
 7362.72   50.25 7760.06   56.55 9398.94   56.29 9982.69   56.1310078.95   51.94
10216.19   55.2810494.04   54.0610569.84   57.9110644.65   56.6711334.94   77.52
#Mann= 11 ,-1 , 0
       0     .04       0 3445.82     .08       0 5504.25    .075       0
 6060.79     .08       0 6135.61     .05       0 6205.88    .085       0
 9398.94     .09       0 9982.69    .032       010216.19     .09       0
10569.84    .035       010644.65     .08       0
#XS Ineff= 2 , 0
       0    4700    59.8    8050       0    59.8
Permanent Ineff=
       F       F
Bank Sta=6135.61,6205.88
XS Rating Curve= 0 ,0
Exp/Cntr=0.3,0.1

Type RM Length L Ch R = 1 ,292629  ,3051.82,4172.92,2996.84
BEGIN DESCRIPTION:
Surveyed Section
END DESCRIPTION:
XS GIS Cut Line= 6
2367732.36352539667955.7993164062367195.93371582667557.899108887
2365068.49908447664658.6058959962364803.27709961664218.636901855
    2364896.3125664080.2258911132361116.71850586 660692.78692627
#Sta/Elev= 30
       0   69.24  628.36   67.87   820.1   53.73  1203.6   55.38 1700.67   52.06
 2208.77   51.57 2822.61   50.64 3127.75   54.68 3954.54   55.26 4288.32   54.83
 4357.41   45.34 4698.64   47.53 4826.42 44.64374850.471 34.5326 4877.53 35.7887
4887.552  44.9884946.679  47.556 4977.75   53.38 5187.92   56.09 6424.87   52.86
 6652.37   52.49 7441.07   54.72 8126.5555.34108 8180.67   55.12 8249.81   55.32
 8971.84   55.81 9230.22   68.19 9598.04   63.01 9958.66   77.0110021.64   76.39
#Mann= 17 ,-1 , 0
       0     .04       0  628.36     .08       0  1203.6     .12       0
 1700.67     .08       0 2208.77     .12       0 3127.75     .08       0
 3954.54    .075       0 4357.41     .08       0 4826.42     .05       0
4887.552     .07       0 4977.75     .04       0 6424.87    .085       0
 6652.37     .04       0 7441.07    .085       0 8126.55     .09       0
 8180.67    .035       0 8249.81     .08       0
#XS Ineff= 2 , 0
       0    2800    59.5    6200       0    59.5
Permanent Ineff=
       F       F
Bank Sta=4826.42,4887.552
XS Rating Curve= 0 ,0
Exp/Cntr=0.3,0.1

Type RM Length L Ch R = 1 ,288456  ,1754.92,2557.48,1875.9
XS GIS Cut Line= 5
2370967.13751221666112.0726928712367771.51208496663272.415283203
2366414.71112061662147.2631225592365074.45629883660773.915710449
2361698.99987793659102.733886719
#Sta/Elev= 30
       0   95.88  702.07   98.63 1541.59   85.74 1725.64   63.25 1876.87   59.56
  2057.4   58.65 2608.39   55.82 2855.75   52.89 3113.65   53.31 3890.61   47.09
  4004.4    55.8 4550.89   48.63 5485.29   56.83 5686.87    42.8 5723.39   33.88
 5738.77   42.91 5758.38   43.42 5877.31   47.79 6293.98   42.31 6613.64   47.89
  6773.2   44.54 6913.11   53.97 7359.76   56.42 7518.02   54.26  7992.8    54.4
 8799.3556.19275 9561.35   54.7411053.38   53.4911454.63   69.8411722.96   73.06
#Mann= 17 ,-1 , 0
       0     .04       0 1541.59    .075       0 1725.64     .04       0
 1876.87    .075       0  2057.4     .04       0 2608.39      .1       0
 2855.75     .04       0 3113.65    .075       0 5686.87     .05       0
 5758.38     .07       0 6913.11     .04       0 7359.76     .07       0
 7518.02     .04       0  7992.8     .09       0 8799.35     .04       0
 9561.35     .09       011454.63     .04       0
#XS Ineff= 2 , 0
          5457.5   62.37 7421.34           61.84
Permanent Ineff=
       F       F
Bank Sta=5686.87,5758.38
XS Rating Curve= 0 ,0
Exp/Cntr=0.3,0.1

Type RM Length L Ch R = 1 ,285899  ,5336.59,7309.33,5799.92
XS GIS Cut Line= 6
2371628.99169922664391.2517089842370249.69769287663128.151123047
2367354.08551025  660728.92968752366609.49969482660199.446289063
2364210.27807617659769.2410888672361761.41748047 658859.19152832
#Sta/Elev= 30
       0  114.06  163.84  111.25  331.09   96.72  496.24   94.99  567.87  102.15
   737.4  104.59  960.01  105.74 1129.66  103.44 1258.98   91.05 1425.86   57.36
 1603.51   48.62 2926.03   50.54    3046   45.51 3254.13    50.7 4143.46   48.75
 4806.99   56.01 5283.05   54.09 5534.35   42.66 5806.44   43.54 5873.27   33.48
 5876.23   35.18 5877.16   43.61 6063.88    42.7 6172.82   52.33 7677.76   52.99
 8209.94   54.3111016.42   53.0711162.24   61.6511252.29    73.8 11593.9   74.95
#Mann= 10 ,-1 , 0
       0     .04       0  496.24    .075       0   737.4     .04       0
  960.01    .075       0 5806.44     .05       0 5877.16     .08       0
 6172.82     .07       0 7677.76     .04       0 8209.94     .09       0
11252.29     .04       0
#XS Ineff= 2 ,-1
       0 5142.86  60.468    8036 11593.9    59.8
Permanent Ineff=
       F       F
Bank Sta=5806.44,5877.16
XS Rating Curve= 0 ,0
Exp/Cntr=0.3,0.1

Type RM Length L Ch R = 1 ,278590  ,1582.91,1602.07,1453.16
XS GIS Cut Line= 6
2373107.13269043662163.0092773442371229.70050049661419.223510742
2369707.43572998 659648.763488772368967.83587646659215.977294922
2364098.22131348659317.8364868162362129.20507813658738.714111328
#Sta/Elev= 30
       0   94.44  471.13   93.99 1217.38   75.33 1535.38    49.3 1556.68   37.37
 1600.16   32.34 1604.12   33.88 1606.99   44.87 2315.75   51.33 2829.23   45.32
 3161.7950.97753 3299.04   57.03 3403.3351.57467 3598.38   44.07 3720.88    55.4
 3938.15   45.12 4402.23   45.07 4519.97   49.17 4868.31   41.81 5128.05    43.6
 6272.61   51.58 6362.42   51.45 6945.02   50.14 8094.43   54.09 9503.58   56.41
 11024.4   56.2711400.66    54.611753.01   55.1711938.34   68.66 12137.4   73.57
#Mann= 19 ,-1 , 0
       0     .04       0 1217.38      .1       0 1535.38     .05       0
 1606.99     .08       0 2829.23    .032       0 3161.79     .07       0
 3403.33     .07       0 4402.23     .07       0 4519.97     .08       0
 4868.31     .07       0 5128.05     .08       0 6272.61     .04       0
 6362.42     .08       0 6945.02     .07       0 8094.43     .04       0
 9503.58     .09       0 11024.4     .04       011400.66     .09       0
11938.34     .04       0
#XS Ineff= 2 , 0
       0                 3316.46       0   61.37
Permanent Ineff=
       F       F
Bank Sta=1535.38,1606.99
XS Rating Curve= 0 ,0
Exp/Cntr=0.3,0.1

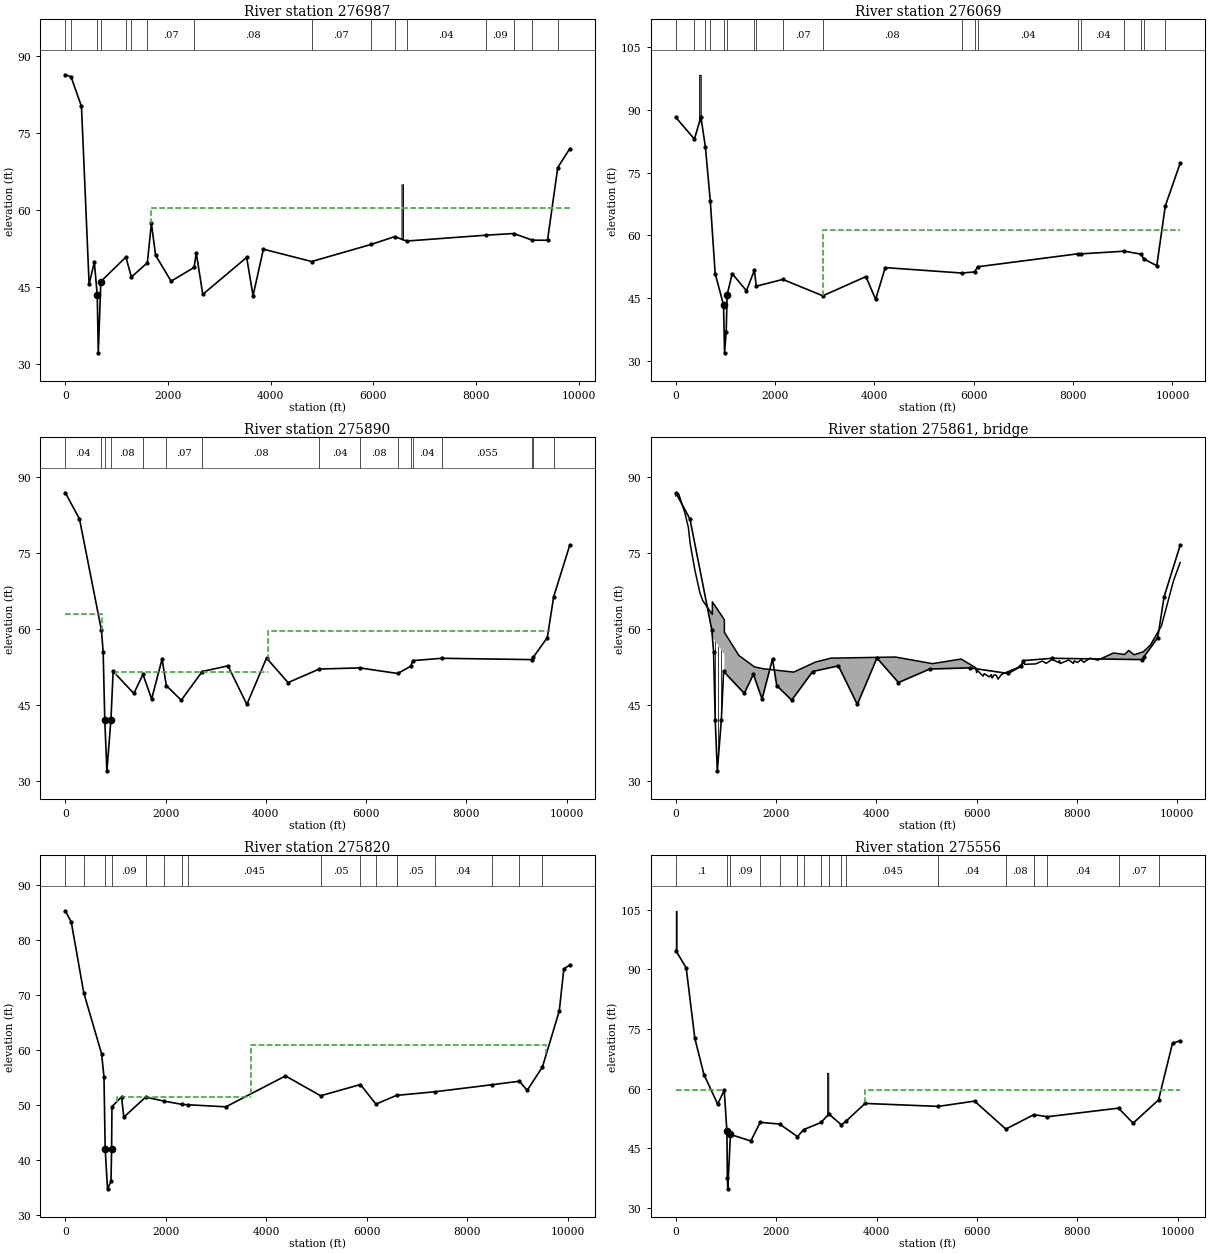
Type RM Length L Ch R = 1 ,276987  ,923.51,918.08,809.98
XS GIS Cut Line= 6
2371689.50408936660459.0864868162370982.72912598   660132.203125
 2369894.0993042659439.6072998052369023.67987061659160.133300781
 2363750.7479248658837.9921264652362228.48327637 658523.61151123
#Sta/Elev= 30
       0   86.41  111.01   86.03  314.45   80.22  463.25   45.53   565.1   49.79
  621.86   43.32  642.01   32.09  691.61   46.02 1178.88    50.8 1286.95   46.89
 1597.39   49.69 1676.41    57.4 1758.08   51.13 2059.76   46.09 2508.07   48.77
 2550.43   51.59 2677.39   43.51  3531.7   50.73 3656.18   43.24 3856.83   52.34
 4798.05   49.93 5952.37   53.26 6415.08   54.79 6647.91   53.93 8186.35   55.07
  8730.6    55.4 9098.02   54.09  9390.9   54.09 9590.21   68.29 9824.02   71.97
#Mann= 16 ,-1 , 0
       0     .04       0  111.01      .1       0  621.86     .05       0
  691.61     .08       0 1178.88     .07       0 1286.95    .032       0
 1597.39     .07       0 2508.07     .08       0 4798.05     .07       0
 5952.37     .04       0 6415.08    .055       0 6647.91     .04       0
 8186.35     .09       0  8730.6     .04       0 9098.02     .09       0
 9590.21     .04       0
#XS Ineff= 2 , 0
                         1675.56           60.36
Permanent Ineff=
       F       F
#Block Obstruct= 1 ,-1
 6546.78 6576.62  65.012
Bank Sta=621.86,691.61
XS Rating Curve= 0 ,0
Exp/Cntr=0.3,0.1

Type RM Length L Ch R = 1 ,276069  ,179.26,179.81,155.71
XS GIS Cut Line= 6
2372341.48950195659455.8950805662371858.52648926659436.262512207
2371159.60467529659287.0545043952367643.27789307658995.182495117
2364379.50952148658672.5286865232362259.25321327658312.952952597
#Sta/Elev= 30
       0   88.27  375.87   83.04  506.48   88.35  597.32   81.12  695.86   68.14
  793.55   50.91  962.02   43.37  982.47   31.94 1015.77   37.01 1034.14    45.8
 1136.54   50.87 1423.37   46.78 1582.71   51.66 1621.31   47.88 2155.65   49.49
 2961.23   45.58  3829.1   50.17 4024.41   44.72 4217.62   52.32 5760.93   51.02
 6015.91   51.29 6078.89   52.52 8101.47   55.63 8168.51   55.61 9033.01   56.25
 9367.23   55.54 9422.08   54.42 9685.67   52.77 9856.87   67.0810156.74    77.3
#Mann= 19 ,-1 , 0
       0     .04       0  375.87     .05       0  597.32     .04       0
  695.86      .1       0  962.02     .05       0 1034.14     .08       0
 1582.71     .07       0 1621.31    .032       0 2155.65     .07       0
 2961.23     .08       0 5760.93     .07       0 6015.91     .08       0
 6078.89     .04       0 8101.47    .055       0 8168.51     .04       0
 9033.01    .055       0 9367.23     .04       0 9422.08     .09       0
 9856.87     .04       0
#XS Ineff= 2 , 0
                         2962.03           61.37
Permanent Ineff=
       F       F
#Block Obstruct= 1 ,-1
  470.87  503.02  98.429
Bank Sta=962.02,1034.14
XS Rating Curve= 0 ,0
Exp/Cntr=0.5,0.3

Type RM Length L Ch R = 1 ,275890  ,77.81,69.35,109.41
BEGIN DESCRIPTION:
Surveyed Section
END DESCRIPTION:
XS GIS Cut Line= 6
 2372238.4888916659234.5435180662370673.37030029659096.982299805
2368852.39868164658651.2792968752367960.99267578658811.549072266
2364204.40148926658396.5432739262362317.40112305658120.289123535
#Sta/Elev= 30
       0   86.97  282.49   81.79 719.398 59.7983 754.613 55.4877  786.81 42.0254
 829.068 31.9156 909.561 42.0491 953.831 51.6056 1366.99   47.24 1548.47   51.02
 1721.11   46.13  1930.4   54.07 2014.31    48.8 2312.01    45.9 2730.69   51.58
 3244.53    52.7 3620.95   45.06 4013.02   54.25 4442.33   49.39 5064.96   52.07
 5869.89    52.3 6630.54   51.19 6889.12   52.62 6931.37   53.74 7505.89    54.2
 9298.85   53.94 9334.06   54.41 9614.02    58.3 9740.55   66.3910061.51   76.59
#Mann= 16 ,-1 , 0
       0     .04       0 719.398      .1       0  786.81     .05       0
 909.561     .08       0 1548.47    .032       0 2014.31     .07       0
 2730.69     .08       0 5064.96     .04       0 5869.89     .08       0
 6630.54    .045       0 6889.12    .035       0 6931.37     .04       0
 7505.89    .055       0 9298.85     .04       0 9334.06     .09       0
 9740.55     .04       0
#XS Ineff= 3 ,-1
       0  725.26   62.88 1019.87 4047.02   51.46 4047.02 9667.27    59.7
Permanent Ineff=
       F       F       F
Bank Sta=786.81,909.561
XS Rating Curve= 0 ,0
Exp/Cntr=0.5,0.3

Type RM Length L Ch R = 3 ,275861  ,,,
BEGIN DESCRIPTION:
SPEIGHTS CHURCH RD
END DESCRIPTION:
Bridge Culvert--1,0,-1,-1, 0
Deck Dist Width WeirC Skew NumUp NumDn MinLoCord MaxHiCord MaxSubmerge Is_Ogee
10.5,30,2.6,0, 60, 60, , , 0.98, 0, 1,1,,
       0   57.87  181.17   252.3  286.84  378.99 481.915 539.262 729.413 729.413
 969.867 969.8671258.614 1569.44 1745.84 2351.74 2780.39 3092.03 4382.39 5118.99
 5691.53 5983.21 6000.74 6020.64 6130.41 6152.31 6256.54 6293.65 6310.02 6348.06
 6395.05 6427.57  6499.1 6821.31 6941.34 6955.85 7177.38 7312.96 7388.46 7509.25
 7637.56 7653.88 7669.11 7840.48 7931.69 7947.82 8013.85 8084.26 8138.61  8263.4
 8417.97 8730.78 8951.23 9034.57 9140.89 9323.13 9465.53 9687.85 9925.9910060.87
   86.36   86.76   83.04   80.07   76.97   71.79  67.146  65.617  62.882  65.382
  61.842  59.342  54.762    52.5   52.13   51.46   53.43   54.23   54.45   53.14
   54.05   52.34   51.36   51.75   50.67   51.15    50.5   50.96    50.3   50.91
   50.81   50.07   51.02   52.35   53.38      53   53.09   53.65    53.2   53.98
   53.36   53.73   53.17   53.87   53.18    53.7   53.37   53.93    53.4   54.24
   53.83   55.25   54.95   55.76    54.9   55.47    56.8   60.62   69.49   73.16
                                                                          58.482
  54.942
                                                                                
                                                                                
                                                                                
                                                                                
       0   57.87  181.17   252.3  286.84  378.99 481.915 539.262 729.413 729.413
 969.867 969.8671258.614 1569.44 1745.84 2351.74 2780.39 3092.03 4382.39 5118.99
 5691.53 5983.21 6000.74 6020.64 6130.41 6152.31 6256.54 6293.65 6310.02 6348.06
 6395.05 6427.57  6499.1 6821.31 6941.34 6955.85 7177.38 7312.96 7388.46 7509.25
 7637.56 7653.88 7669.11 7840.48 7931.69 7947.82 8013.85 8084.26 8138.61  8263.4
 8417.97 8730.78 8951.23 9034.57 9140.89 9323.13 9465.53 9687.85 9925.9910060.87
   86.36   86.76   83.04   80.07   76.97   71.79  67.146  65.617  62.882  65.382
  61.842  59.342  54.762    52.5   52.13   51.46   53.43   54.23   54.45   53.14
   54.05   52.34   51.36   51.75   50.67   51.15    50.5   50.96    50.3   50.91
   50.81   50.07   51.02   52.35   53.38      53   53.09   53.65    53.2   53.98
   53.36   53.73   53.17   53.87   53.18    53.7   53.37   53.93    53.4   54.24
   53.83   55.25   54.95   55.76    54.9   55.47    56.8   60.62   69.49   73.16
                                                                          58.482
  54.942
                                                                                
                                                                                
                                                                                
                                                                                
Pier Skew, UpSta & Num, DnSta & Num=  ,789.778, 4 ,789.778, 4 , 3 , 3 , 0 ,,
     1.5     1.5       2       2
      30 55.5533 55.5533 57.5533
     1.5     1.5       2       2
      30 55.5533 55.5533 57.5533
Pier Skew, UpSta & Num, DnSta & Num=  ,850.143, 4 ,850.143, 4 , 3 , 3 , 0 ,,
     1.5     1.5       2       2
      30  54.691  54.691  56.691
     1.5     1.5       2       2
      30  54.691  54.691  56.691
Pier Skew, UpSta & Num, DnSta & Num=  ,910.508, 4 ,910.508, 4 , 3 , 3 , 0 ,,
     1.5     1.5       2       2
      30   53.78   53.78   55.78
     1.5     1.5       2       2
      30   53.78   53.78   55.78
Abutment Skew #Up #Dn= , 3 , 3
 729.413 762.963 790.663
  58.482 56.1186 42.1596
 729.413 769.973 795.573
  58.482  56.128 42.2645
Abutment Skew #Up #Dn= , 3 , 3
 916.617 932.117 969.867
 42.0877 48.9137  54.942
 928.717 950.867 969.867
 42.1501 50.0946 53.7133
BR Coef=-1 , 1 , 0 ,1.25, 0 ,,,0.8,0,2,0,
WSPro=,,,, 1 ,,,, 0 ,,,, 0 ,,,,-1 ,-1 ,-1 , 0 , 0 , 0 , 0 , 0
BC Design=,, 0 ,, 0 ,,,,,,
BC Use User HTab Curves=0
BC User HTab FreeFlow(D)= 0

Type RM Length L Ch R = 1 ,275820  ,331.8,264.19,138.86
BEGIN DESCRIPTION:
Surveyed Section
END DESCRIPTION:
XS GIS Cut Line= 6
 2372245.1149292659148.4052734382370851.67449951659015.325317383
 2368814.5690918  658564.05468752368135.71148682658713.851928711
2367746.77069092658718.1448974612362337.27929688658034.150878906
#Sta/Elev= 30
       0    85.4  118.66   83.32  366.48    70.5 721.913 59.3832 769.104 55.1504
 793.201  42.068 839.387  34.832 908.667 36.1668 920.715 42.0946 927.744  49.768
 1117.94   51.57 1163.74   47.87 1598.45   51.52 1969.95   50.77 2325.38   50.19
 2439.85   50.12 3194.15   49.75  4380.3   55.37  5078.5   51.76  5871.7    53.8
 6179.94   50.24  6590.6   51.83 7348.66   52.48 8484.2453.76069 9034.46    54.4
 9188.69   52.74 9492.31   56.99 9827.79   67.19 9918.73   74.8510036.36   75.53
#Mann= 16 ,-1 , 0
       0     .04       0  366.48      .1       0 793.201     .05       0
 920.715     .09       0 1598.45    .045       0 1969.95     .09       0
 2325.38    .075       0 2439.85    .045       0  5078.5     .05       0
  5871.7     .04       0 6179.94     .08       0  6590.6     .05       0
 7348.66     .04       0 8484.24    .055       0 9034.46     .07       0
 9492.31     .04       0
#XS Ineff= 3 ,-1
 3688.97 9569.62    60.9       0  722.49   58.43 1019.87 3688.97   51.46
Permanent Ineff=
       F       F       F
Bank Sta=793.201,920.715
XS Rating Curve= 0 ,0
Exp/Cntr=0.5,0.3

Type RM Length L Ch R = 1 ,275556  ,1304.35,1313.92,1164.16
XS GIS Cut Line= 6
2372310.61047363658593.1254882812371898.32507324658632.390686035
2371203.32971191658871.9088745122370826.38311768658875.835510254
2368799.85852051658474.8934936522362378.49732124657820.526101164
#Sta/Elev= 30
       0   94.76  207.85   90.39  380.19   72.63  562.04   63.51  835.15   56.08
  966.11   59.54 1019.19   49.21 1028.13   37.55 1036.36   34.74 1089.82   48.43
 1496.15   46.79 1682.16   51.49 2070.66   51.05 2424.86   47.89 2547.97   49.65
  2895.1   51.46  3050.5   53.58 3300.75   50.85 3387.53   51.72 3772.55   56.25
 5229.13    55.5 5953.55   56.83 6576.28   49.79 7134.3153.41792 7405.75 52.8996
 8821.51   55.06 9112.03   51.27  9618.7   57.14 9897.23   71.39 10050.5   72.04
#Mann= 17 ,-1 , 0
       0      .1       0 1019.19     .05       0 1089.82     .09       0
 1682.16    .045       0 2070.66     .09       0 2424.86    .075       0
 2547.97    .045       0  2895.1     .05       0  3050.5    .045       0
 3300.75    .075       0 3387.53    .045       0 5229.13     .04       0
 6576.28     .08       0 7134.31     .05       0 7405.75     .04       0
 8821.51     .07       0  9618.7     .04       0
#XS Ineff= 2 , 0
       0  949.79    59.7 3775.77       0    59.7
Permanent Ineff=
       F       F
#Block Obstruct= 2 ,-1
       0   18.02 104.763 3016.25 3038.88  63.964
Bank Sta=1019.19,1089.82
XS Rating Curve= 0 ,0
Exp/Cntr=0.3,0.1

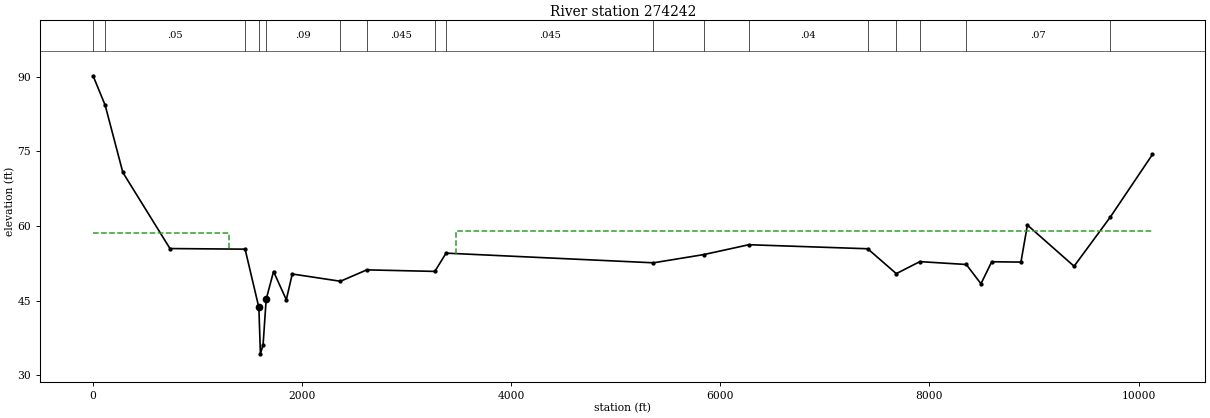
Type RM Length L Ch R = 1 ,274242  ,1158.29,1138.5,1103.9
XS GIS Cut Line= 6
2372267.06390381657751.2476806642371780.17449951657562.774475098
2371320.77069092657558.8479003912369763.78131104657899.825683594
2368944.73669434657875.0061035162362243.46289063657204.878723145
#Sta/Elev= 30
       0   90.17  115.52   84.26  284.75   70.75  735.54   55.46 1454.14   55.34
 1585.87   43.62 1600.72   34.31 1626.23   36.13 1655.79   45.26 1726.26   50.85
 1848.34   45.18 1905.39   50.35 2366.14   48.89 2618.46   51.18 3269.02   50.87
 3376.44   54.54 5360.5552.59762 5841.88   54.25 6272.55   56.23 7409.51   55.42
 7683.11   50.42 7908.0752.83341 8352.93   52.26 8493.04   48.38 8595.86   52.81
 8875.42   52.74 8937.21   60.18 9383.85   51.91 9731.07   61.8110133.36   74.36
#Mann= 17 ,-1 , 0
       0    .055       0  115.52     .05       0 1454.14      .1       0
 1585.87     .05       0 1655.79     .09       0 2366.14    .075       0
 2618.46    .045       0 3269.02    .075       0 3376.44    .045       0
 5360.55     .04       0 5841.88     .04       0 6272.55     .04       0
 7409.51     .08       0 7683.11     .07       0 7908.07     .04       0
 8352.93     .07       0 9731.07     .04       0
#XS Ineff= 2 , 0
         1301.99   58.56 3471.97           59.03
Permanent Ineff=
       F       F
Bank Sta=1585.87,1655.79
XS Rating Curve= 0 ,0
Exp/Cntr=0.3,0.1