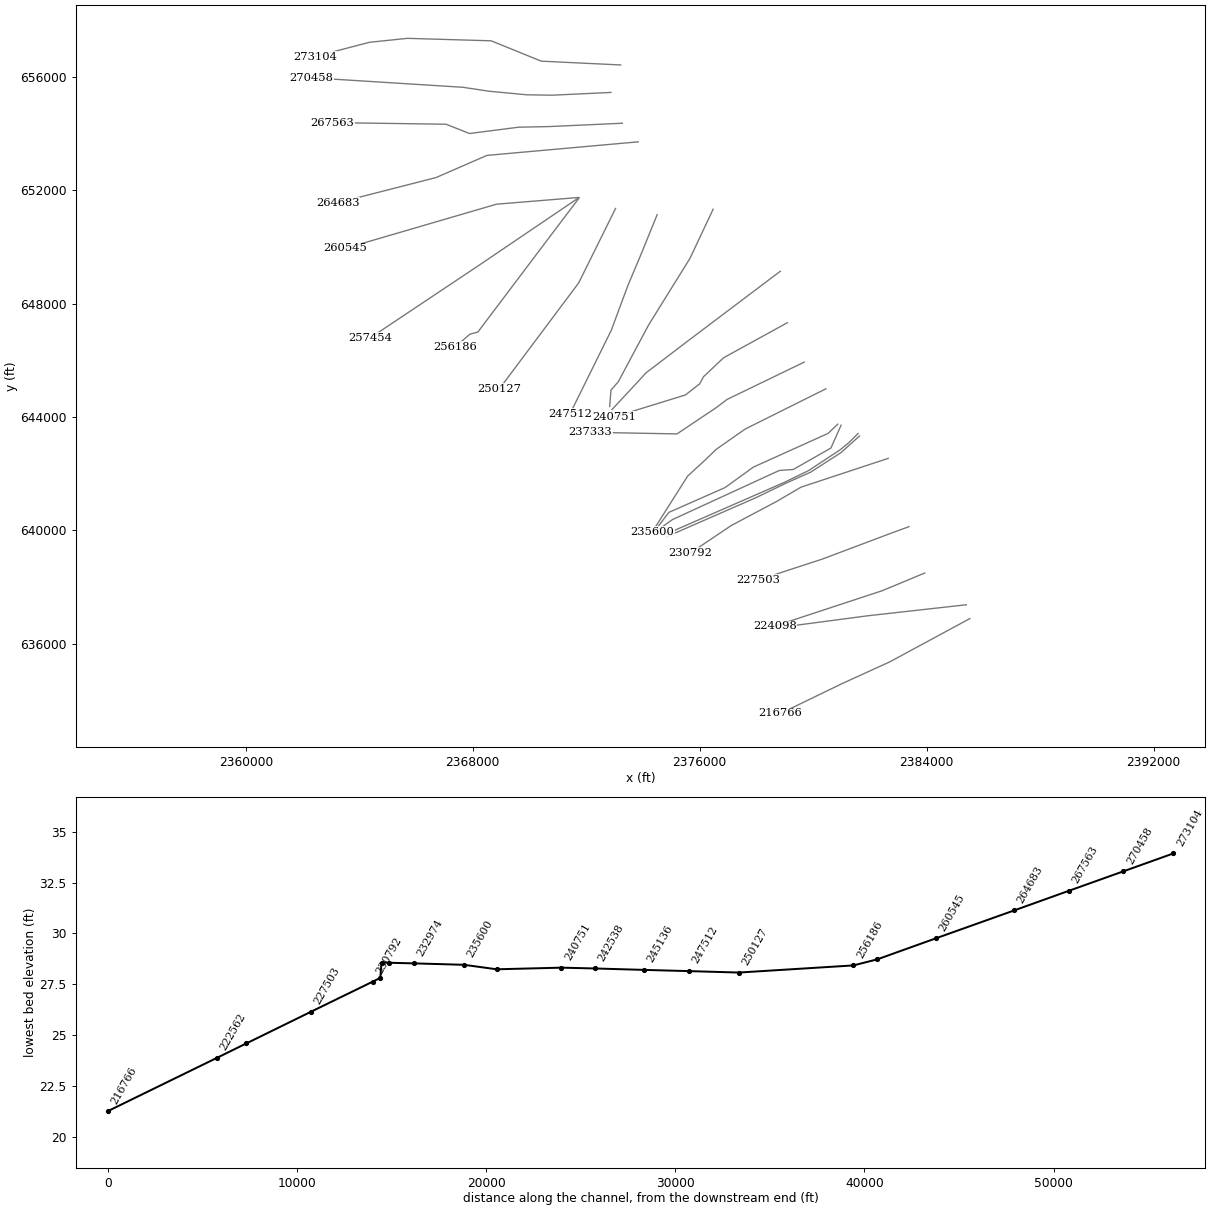
HEC-RAS study DTL_ContentneaCrk.prj: DTL_Contentnea_Crk

--- DTL_ContentneaCrk.g01 (geometry) --- (continued)

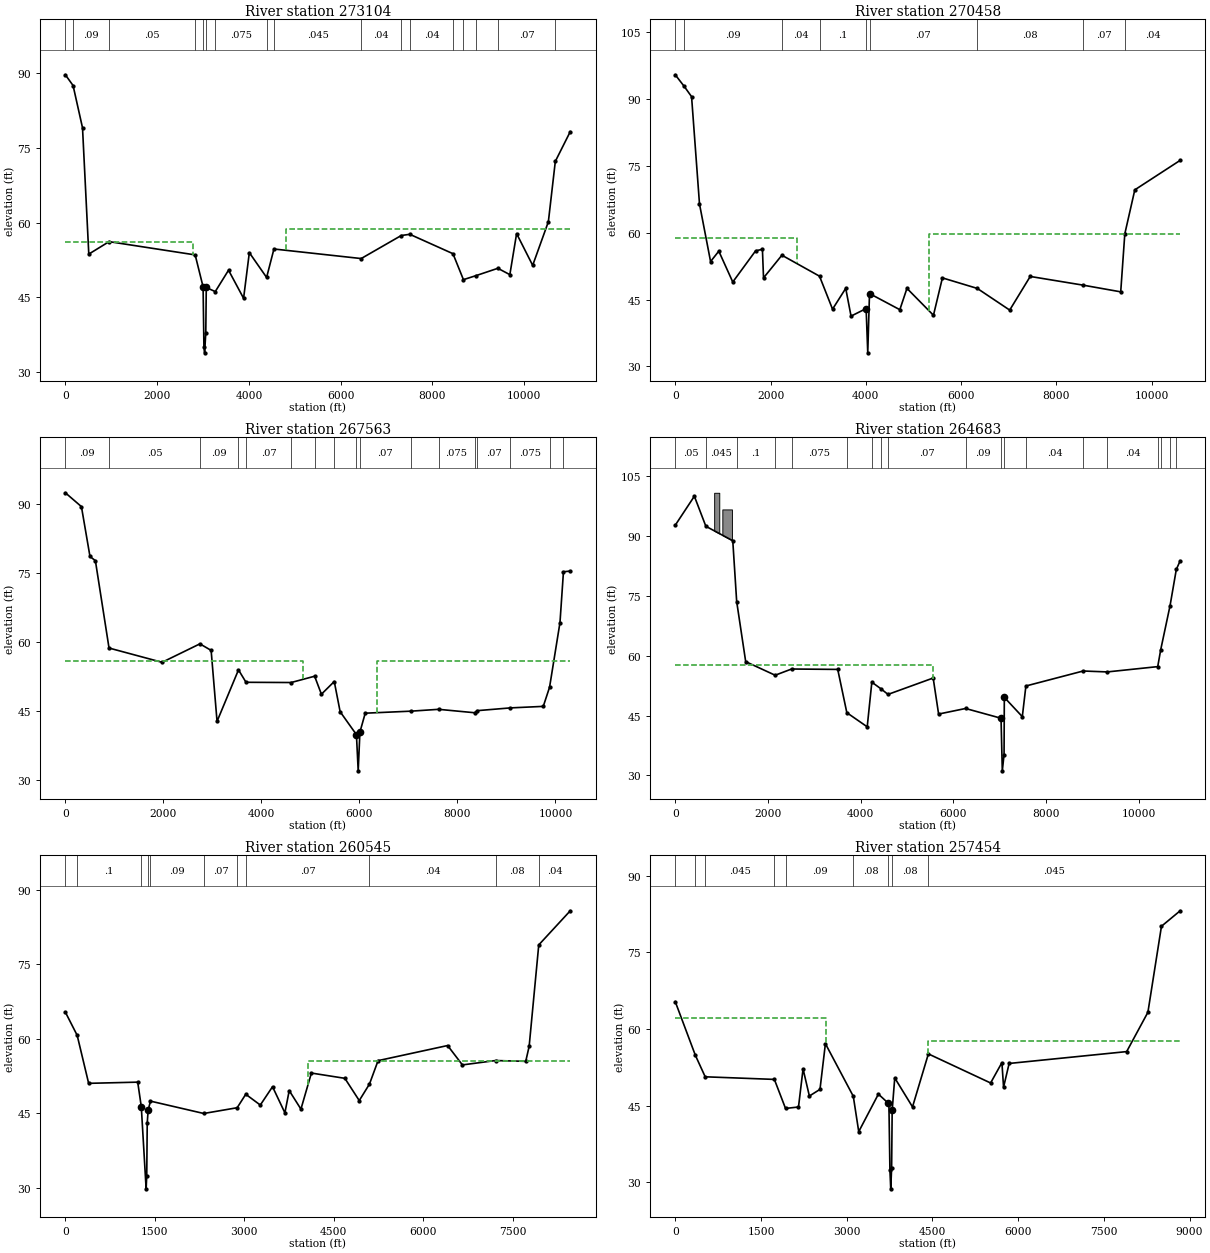
Type RM Length L Ch R = 1 ,273104  ,1545.49,2645.76,2500.27
XS GIS Cut Line= 6
2373217.13208008656425.994689941 2370417.5178833656559.496520996
2368650.58050537657278.0510864262365700.44927979657365.307312012
2364360.19451904657225.6975097662362433.57830811656723.101928711
#Sta/Elev= 30
       0   89.55  168.34    87.4  374.12   78.94  510.82   53.68  952.8156.17226
 2828.74   53.52 3001.48   47.13 3019.55   35.11    3035   33.93 3060.07   37.98
 3070.79      47 3266.64   46.18 3555.96   50.46 3883.83   44.84 4009.11   53.97
 4385.59   49.01 4545.12    54.7 6446.35   52.79 7319.95    57.4 7505.89   57.64
  8446.6   53.76 8674.35   48.57 8950.52   49.38 9424.72   50.84 9685.88   49.57
 9833.12   57.7810183.54   51.4310525.18   60.1510676.81   72.2311002.48   78.18
#Mann= 17 ,-1 , 0
       0     .04       0  168.34     .09       0  952.81     .05       0
 2828.74      .1       0 3001.48     .05       0 3070.79     .09       0
 3266.64    .075       0 4385.59     .07       0 4545.12    .045       0
 6446.35     .04       0 7319.95     .08       0 7505.89     .04       0
  8446.6     .08       0 8674.35     .07       0 8950.52     .04       0
 9424.72     .07       010676.81     .04       0
#XS Ineff= 2 , 0
         2777.58   56.09 4806.51            58.7
Permanent Ineff=
       F       F
Bank Sta=3001.48,3070.79
XS Rating Curve= 0 ,0
Exp/Cntr=0.3,0.1

Type RM Length L Ch R = 1 ,270458  ,2305.97,2894.47,2818.14
XS GIS Cut Line= 6
2372875.44873047655456.4439086912370795.26171875655358.717102051
2369908.73907471655372.6781005862368582.44512939655498.326904297
2367654.03948975655637.9368896482362307.75708008655974.034484863
#Sta/Elev= 30
       0   95.37  188.63   92.76   342.4   90.47  508.68   66.41  741.25   53.51
  913.99   55.84  1207.1   48.92 1686.03   55.91 1829.31   56.26 1852.59   49.85
 2238.09   54.93 3027.57   50.23 3300.94   42.84 3577.63    47.5 3689.25   41.28
 4005.67   42.97    4040   33.05 4076.67   46.34 4713.13   42.72 4862.51    47.5
 5418.77   41.47 5606.69   49.85 6338.08   47.49 7018.84   42.63 7449.84   50.17
 8559.21   48.22 9348.81   46.72 9434.53   59.71 9644.46   69.58 10596.5   76.19
#Mann= 9 ,-1 , 0
       0     .04       0  188.63     .09       0 2238.09     .04       0
 3027.57      .1       0 4005.67     .05       0 4076.67     .07       0
 6338.08     .08       0 8559.21     .07       0 9434.53     .04       0
#XS Ineff= 2 , 0
         2549.73    58.8 5332.14           59.75
Permanent Ineff=
       F       F
Bank Sta=4005.67,4076.67
XS Rating Curve= 0 ,0
Exp/Cntr=0.3,0.1

Type RM Length L Ch R = 1 ,267563  ,1311.08,2880.14,2630.93
XS GIS Cut Line= 6
2373273.85388184654369.5552978522370670.12988281654250.886901855
 2369623.0559082  654229.94531252367884.91290283654006.569519043
2367061.21472168654334.6527099612363052.60168457654391.013671875
#Sta/Elev= 30
       0   92.48  328.17   89.47  502.45   78.65  612.93   77.73   891.1   58.76
 1973.66   55.66 2745.43   59.67  2974.4   58.25 3095.09   42.83 3532.48   54.02
 3685.98   51.32 4606.96   51.27 5085.99   52.64  5224.4   48.73 5486.73   51.49
 5606.48   44.93 5938.98   39.95    5975   32.09 6010.06 40.5024 6118.26   44.61
 7050.54   45.05 7615.08   45.45 8348.57   44.71 8403.17   45.16 9078.96   45.76
 9751.08   46.09 9879.41   50.2510091.95    64.310162.71   75.3210301.79   75.48
#Mann= 17 ,-1 , 0
       0     .09       0   891.1     .05       0 2745.43     .09       0
 3532.48     .04       0 3685.98     .07       0 4606.96     .04       0
 5085.99     .07       0 5486.73      .1       0 5938.98     .05       0
 6010.06     .07       0 7050.54     .08       0 7615.08    .075       0
 8348.57     .08       0 8403.17     .07       0 9078.96    .075       0
 9879.41     .09       010162.71    .045       0
#XS Ineff= 2 , 0
         4858.17   55.88 6355.48           55.88
Permanent Ineff=
       F       F
Bank Sta=5938.98,6010.06
XS Rating Curve= 0 ,0
Exp/Cntr=0.3,0.1

Type RM Length L Ch R = 1 ,264683  ,3869.9,4138.07,4076.91
XS GIS Cut Line= 5
2373835.17230225653713.3372802732368505.74127197653234.690673828
2367884.52587891652966.1840820312366709.42749023652452.875305176
2363234.69287109 651562.47467041
#Sta/Elev= 30
       0   92.74  412.25  100.01  660.36   92.47    1241   88.84 1325.07    73.6
 1519.59   58.52 2155.42   55.11 2509.57   56.67 3505.29   56.57  3701.745.71607
 4141.36   42.17  4241.1   53.37 4448.1451.61576  4589.8    50.3 5564.32   54.41
 5681.69   45.37 6263.57   46.77 7028.54   44.32 7055.73   31.13 7093.62   35.21
 7099.37   49.56 7487.47   44.72 7564.67   52.41 8800.38   56.17 9320.17   55.94
10408.77   57.2710474.16   61.5610674.66   72.5510809.78   81.6410893.08   83.82
#Mann= 19 ,-1 , 0
       0     .05       0  660.36    .045       0 1325.07      .1       0
 2155.42     .04       0 2509.57    .075       0  3701.7    .085       0
  4241.1    .075       0 4448.14     .09       0  4589.8     .07       0
 6263.57     .09       0 7028.54     .05       0 7099.37    .075       0
 7564.67     .04       0 8800.38     .09       0 9320.17     .04       0
10408.77     .07       010474.16     .04       010674.66    .055       0
10809.78     .08       0
#XS Ineff= 2 , 0
         5569.12   57.68
Permanent Ineff=
       F       F
#Block Obstruct= 2 ,-1
  839.19  949.71 100.873 1015.87  1222.9  96.699
Bank Sta=7028.54,7099.37
XS Rating Curve= 0 ,0
Exp/Cntr=0.3,0.1

Type RM Length L Ch R = 1 ,260545  ,2856.63,3091.5,3135.78
XS GIS Cut Line= 3
2371727.91809082651749.4244995122368839.05987549651512.690124512
2363492.79351807649949.463500977
#Sta/Elev= 30
       0   65.34  198.17   60.67  390.83      51 1213.79   51.24 1273.69   46.31
  1354.9   29.76  1365.2   32.42 1373.32   42.98 1388.44   45.61 1427.82   47.42
 2321.26   44.93 2881.89   46.09 3025.85    48.8 3269.78   46.63  3474.9   50.32
 3682.31   45.06 3754.75   49.54 3951.21   45.81 4126.68   53.07 4687.97   52.01
 4929.44   47.53 5100.68   50.85  5245.3   55.57 6411.49   58.61 6659.56   54.71
 7216.99   55.59 7721.82   55.43 7779.11   58.45 7940.22   78.87 8468.66   85.74
#Mann= 11 ,-1 , 0
       0     .05       0  198.17      .1       0 1273.69     .05       0
 1388.44     .08       0 1427.82     .09       0 2321.26     .07       0
 2881.89    .085       0 3025.85     .07       0 5100.68     .04       0
 7216.99     .08       0 7940.22     .04       0
#XS Ineff= 2 , 0
                         4068.72           55.59
Permanent Ineff=
       F       F
Bank Sta=1273.69,1388.44
XS Rating Curve= 0 ,0
Exp/Cntr=0.3,0.1

Type RM Length L Ch R = 1 ,257454  ,1169.88,1267.78,1332.05
XS GIS Cut Line= 3
2371734.44067383651738.2431030272368298.92791748 649408.92767334
2364402.84307861 646805.65612793
#Sta/Elev= 30
       0   65.35  352.58   54.84     524   50.65  1734.6   50.14 1929.89   44.46
  2156.7   44.74 2236.68   52.19 2347.17   46.89 2532.94   48.19 2627.69   57.13
 3115.75   46.84 3210.98   39.92 3555.03   47.26 3725.47   45.51 3738.98   45.35
 3756.87   32.38 3771.11   28.73 3786.68   32.88 3796.16   44.06 3841.05   50.43
 4152.17   44.76 4429.73   55.13 5518.76   49.44 5716.71   53.42  5745.6   48.62
 5843.16   53.26 7899.79   55.58 8271.62   63.27 8508.77    80.1 8836.27   83.13
#Mann= 9 ,-1 , 0
       0     .05       0  352.58      .1       0     524    .045       0
  1734.6     .08       0 1929.89     .09       0 3115.75     .08       0
 3725.47     .05       0 3796.16     .08       0 4429.73    .045       0
#XS Ineff= 2 , 0
          2631.1   62.14 4430.38           57.69
Permanent Ineff=
       F       F
Bank Sta=3725.47,3796.16
XS Rating Curve= 0 ,0
Exp/Cntr=0.3,0.1

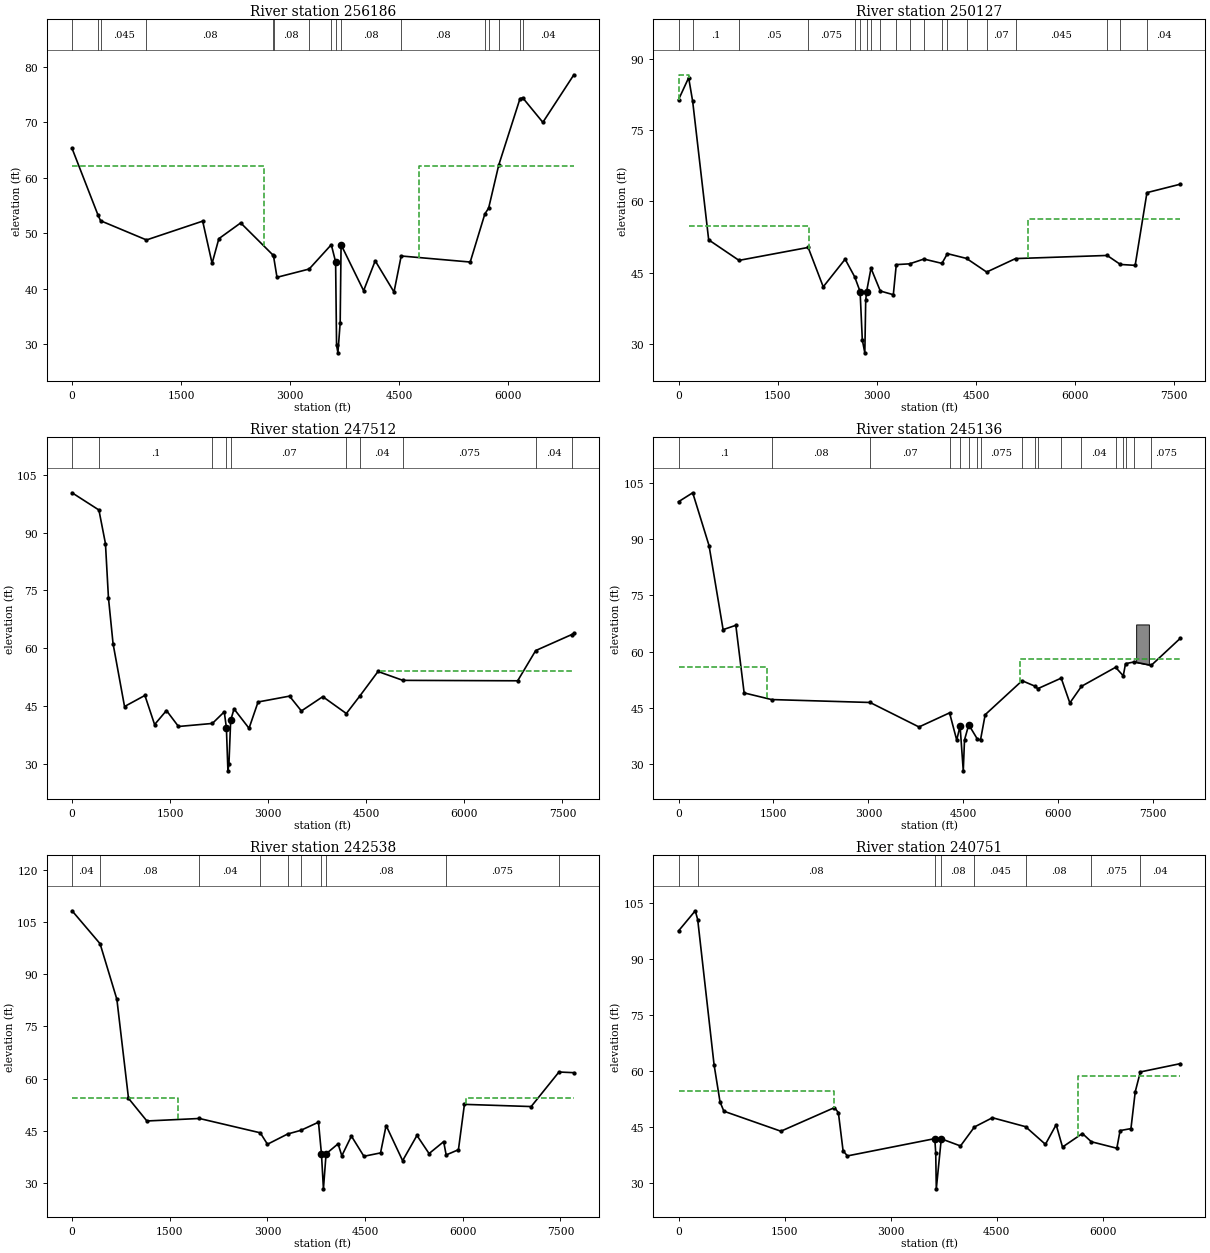
Type RM Length L Ch R = 1 ,256186  ,4331.49,6058.95,5064.86
XS GIS Cut Line= 5
2371748.41748047651728.9252929692370626.88250732650245.875488281
2368180.52008057646999.7821044922367905.54547119646927.420288086
2367374.68908691646476.132873535
#Sta/Elev= 30
       0   65.26     357   53.25  392.21   52.23 1024.0448.76971 1797.18   52.16
 1926.87   44.55 2019.89      49 2320.43   51.84 2771.04   45.97 2772.43   45.86
 2819.96   42.04 3262.69   43.53 3567.21   47.91  3626.6   44.83 3639.75   29.83
 3658.39   28.43 3689.44   33.85 3701.86   47.91 4012.05   39.63 4171.54   45.01
 4430.14   39.39  4529.1   45.88 5478.96   44.79 5680.19   53.45 5732.67   54.52
 5870.78   62.23 6164.25   74.24 6200.84   74.39 6478.53   69.96 6905.17   78.53
#Mann= 16 ,-1 , 0
       0     .05       0     357      .1       0  392.21    .045       0
 1024.04     .08       0 2771.04     .05       0 2772.43     .08       0
 3262.69     .09       0 3567.21     .08       0  3626.6     .05       0
 3701.86     .08       0  4529.1     .08       0 5680.19     .04       0
 5732.67     .08       0 5870.78     .04       0 6164.25    .075       0
 6200.84     .04       0
#XS Ineff= 2 , 0
         2646.64   62.14 4778.07           62.14
Permanent Ineff=
       F       F
Bank Sta=3626.6,3701.86
XS Rating Curve= 0 ,0
Exp/Cntr=0.3,0.1

Type RM Length L Ch R = 1 ,250127  ,2588.29,2614.69,2397.21
XS GIS Cut Line= 3
2373034.63952637651360.614318848 2371738.2244873   648738.421875
2368941.63031006644999.225524902
#Sta/Elev= 30
       0   81.48  153.13    86.1  214.16    81.1  456.19   51.91  915.1447.58092
 1961.66   50.31 2189.68      42 2521.17   47.83 2665.66   44.11 2747.68   41.01
 2781.05   30.82 2819.07   28.08 2832.59   39.15  2846.1   41.01 2912.49   45.92
 3053.74   41.12 3250.44   40.34 3295.25   46.69  3496.5   46.85 3712.94   47.86
 3986.35   46.95 4069.12      49 4358.47   47.99 4663.01   45.12  5099.7   47.96
 6486.45   48.62 6686.94   46.72  6910.3   46.53 7088.69   61.87 7593.73   63.65
#Mann= 20 ,-1 , 0
       0    .032       0  214.16      .1       0  915.14     .05       0
 1961.66    .075       0 2665.66     .08       0 2747.68     .05       0
  2846.1     .08       0 2912.49     .07       0 3053.74     .08       0
 3295.25     .08       0  3496.5     .07       0 3712.94    .075       0
 3986.35     .07       0 4069.12     .04       0 4358.47    .075       0
 4663.01     .07       0  5099.7    .045       0 6486.45     .07       0
 6686.94     .08       0 7088.69     .04       0
#XS Ineff= 3 ,-1
       0  153.29  86.726 5287.52 7593.73   56.29  153.29 1974.68   54.88
Permanent Ineff=
       F       F       F
Bank Sta=2747.68,2846.1
XS Rating Curve= 0 ,0
Exp/Cntr=0.3,0.1

Type RM Length L Ch R = 1 ,247512  ,1720.91,2376.14,1929.55
XS GIS Cut Line= 5
2374501.76428223651141.2966918952373906.09552002649676.944274902
2373471.75372314 648646.933471682372888.49468994647070.893310547
2371430.43548584644116.451293945
#Sta/Elev= 30
       0  100.31  410.55   95.84  510.47   87.13  556.38   73.05  626.71   61.18
  802.24   44.84 1113.87   47.72 1262.11   40.16 1443.52    43.8 1627.38   39.66
 2145.61   40.45 2327.57   43.46 2359.92   39.35  2383.5   28.15 2399.24   30.02
 2425.73   41.27 2476.91   44.22 2706.33   39.19  2844.5   46.02 3325.33   47.54
 3506.99   43.69 3834.21    47.4 4194.5343.02516 4405.56   47.68 4678.74   53.93
 5059.38   51.63 6814.53   51.52 7089.88   59.36 7640.0963.50806 7673.86   63.83
#Mann= 10 ,-1 , 0
       0    .045       0  410.55      .1       0 2145.61     .08       0
 2359.92     .05       0 2425.73     .07       0 4194.53    .075       0
 4405.56     .04       0 5059.38    .075       0 7089.88     .04       0
 7640.09     .05       0
#XS Ineff= 2 , 0
       0                 4717.19       0   54.01
Permanent Ineff=
       F       F
Bank Sta=2359.92,2425.73
XS Rating Curve= 0 ,0
Exp/Cntr=0.3,0.1

Type RM Length L Ch R = 1 ,245136  ,2124.11,2598.11,1668.78
XS GIS Cut Line= 6
2376475.38989258651334.4114990232375656.34527588649597.044311523
2374197.22808838647244.036071777 2373130.1942749645243.797485352
2372874.97009277 644953.234497072372827.85168457644372.108520508
#Sta/Elev= 30
       0   99.98  223.93  102.36  481.65   88.29   704.2   65.86     905   67.02
 1036.34   48.99 1469.64   47.22 3025.69   46.44  3798.4   39.91 4281.31   43.67
 4394.26   36.43 4447.61   40.15    4498   28.21 4517.58   36.45 4584.49    40.5
 4718.87   36.73 4770.39   36.45 4843.98   43.18 5427.53   52.24  5625.7   50.82
 5674.85   50.12 6045.04   52.93 6181.66   46.31 6365.28   50.75 6904.31   55.82
 7025.59   53.55 7061.26   56.79  7198.4   57.25 7467.9156.34296 7926.88   63.56
#Mann= 18 ,-1 , 0
       0      .1       0 1469.64     .08       0 3025.69     .07       0
 4281.31     .08       0 4447.61     .05       0 4584.49    .075       0
 4718.87    .032       0 4770.39    .075       0 5427.53     .04       0
  5625.7    .075       0 5674.85     .04       0 6045.04    .075       0
 6365.28     .04       0 6904.31    .032       0 7025.59     .04       0
 7061.26    .032       0  7198.4    .045       0 7467.91    .075       0
#XS Ineff= 2 , 0
         1396.02   55.82 5388.79           57.93
Permanent Ineff=
       F       F
#Block Obstruct= 1 ,-1
 7229.12 7430.05   67.25
Bank Sta=4447.61,4584.49
XS Rating Curve= 0 ,0
Exp/Cntr=0.3,0.1

Type RM Length L Ch R = 1 ,242538  ,1713.95,1787.35,1656.61
XS GIS Cut Line= 5
2378843.20251465649146.5432739262375658.97509766646742.810119629
2374102.32507324645556.1262817382373844.04669189 645269.92590332
2372908.66070557644264.734924316
#Sta/Elev= 30
       0  108.23  429.97   98.76  688.06   82.77  866.52    54.3 1148.76   47.79
 1955.69   48.51 2889.61  44.392 3000.61    41.1 3309.56   44.04 3512.99    45.1
 3784.15   47.44 3829.69   38.31    3860   28.28 3900.59   38.35 4084.91   41.22
 4142.46   37.78 4289.47   43.45 4481.65   37.64 4736.89   38.61  4822.5   46.49
 5075.81   36.38 5296.13   43.63  5482.1   38.42 5706.47   41.85 5744.54   38.02
 5933.19   39.53 6025.08   52.57 7049.97   51.94 7476.76   61.87 7705.62   61.68
#Mann= 10 ,-1 , 0
       0     .04       0  429.97     .08       0 1955.69     .04       0
 2889.61     .08       0 3309.56     .04       0 3512.99     .08       0
 3829.69     .05       0 3900.59     .08       0 5744.54    .075       0
 7476.76     .04       0
#XS Ineff= 2 , 0
       0    1631   54.45 6055.18       0   54.45
Permanent Ineff=
       F       F
Bank Sta=3829.69,3900.59
XS Rating Curve= 0 ,0
Exp/Cntr=0.3,0.1

Type RM Length L Ch R = 1 ,240751  ,3409.8,3417.89,3294.89
XS GIS Cut Line= 6
2379093.68890381647331.0661010742376844.50128174646093.826721191
2376136.96447754 645424.882690432376001.88928223645174.028686523
2375500.18127441644781.6672973632372988.08392334644005.248718262
#Sta/Elev= 30
       0   97.57  236.62  102.97  271.01  100.58  502.41   61.64  586.47   51.67
  640.95   49.16    1447   43.79 2204.76   50.13 2260.02   48.78 2326.44   38.52
 2387.92   37.16 3622.81    41.8  3636.2      38 3644.43   28.32 3714.66   41.75
 3986.32   39.83 4183.61   44.93 4437.74   47.41 4905.83   45.01 5187.27   40.27
 5338.95   45.53 5428.78   39.54 5709.68   43.17 5836.62   40.96 6196.78   39.22
 6242.99   43.96 6396.35   44.49 6457.03   54.39 6529.04    59.7 7094.47   61.93
#Mann= 8 ,-1 , 0
       0     .04       0  271.01     .08       0 3622.81     .05       0
 3714.66     .08       0 4183.61    .045       0 4905.83     .08       0
 5836.62    .075       0 6529.04     .04       0
#XS Ineff= 2 , 0
         2198.92   54.62 5641.95           58.53
Permanent Ineff=
       F       F
Bank Sta=3622.81,3714.66
XS Rating Curve= 0 ,0
Exp/Cntr=0.3,0.1

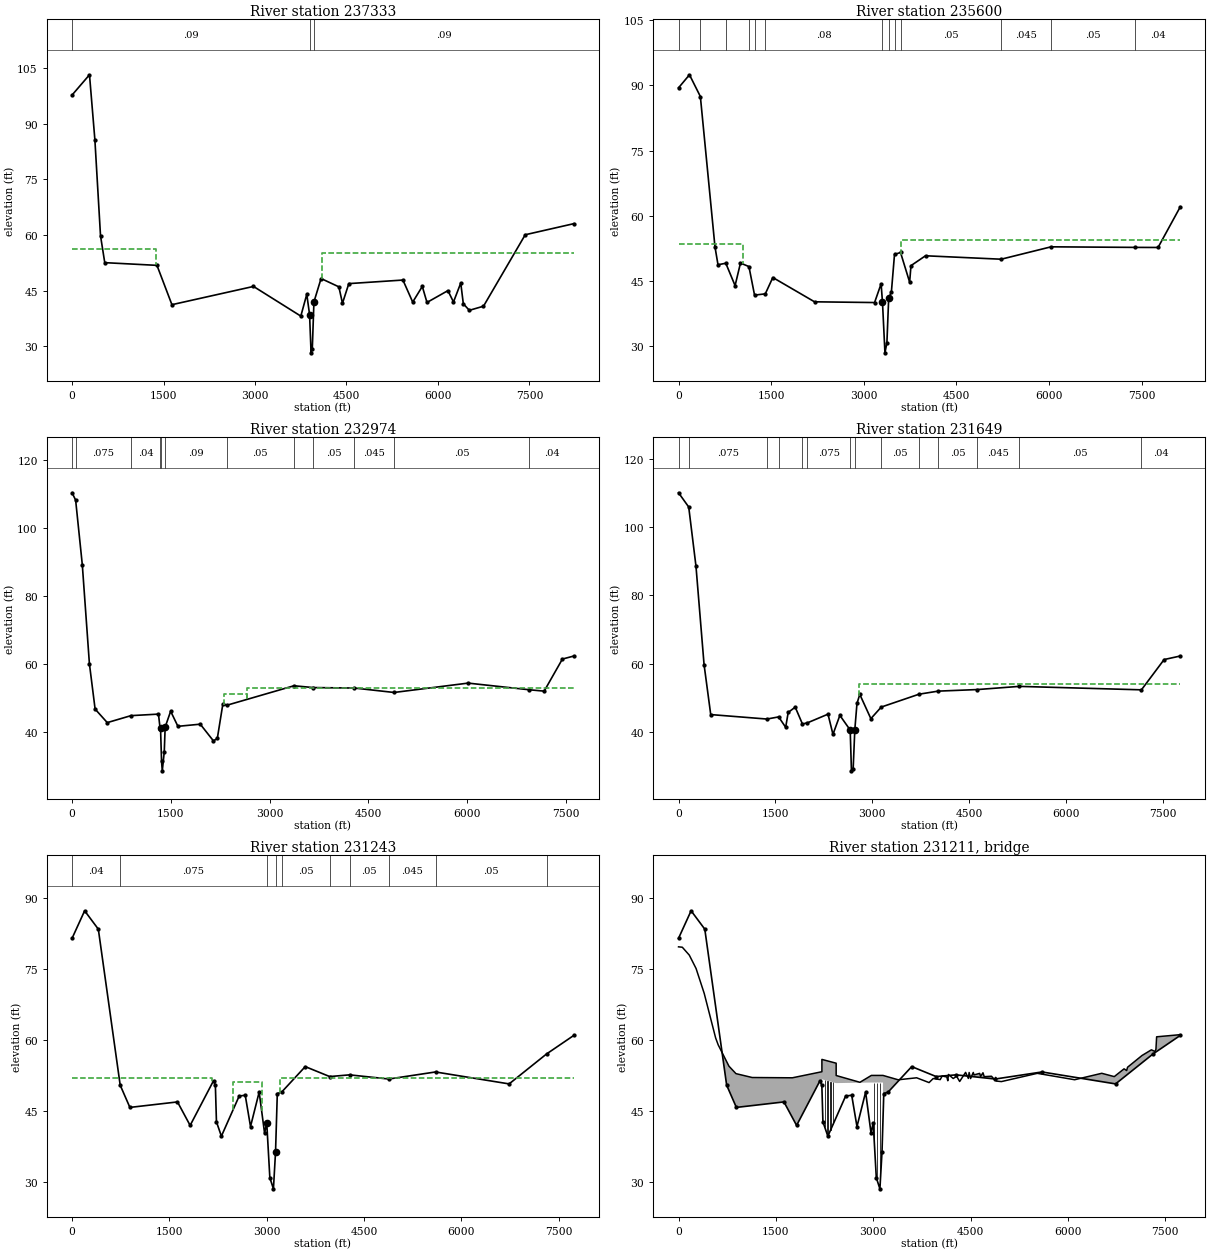
Type RM Length L Ch R = 1 ,237333  ,1535.2,1733.14,1694.78
XS GIS Cut Line= 5
2379689.35772705645941.1723022462376964.93548584644622.461486816
2376598.30267334644342.6629028322375200.83691406643406.610107422
2372142.56231689643463.596679688
#Sta/Elev= 30
       0   97.73  285.69  103.19  374.09   85.68  466.42   59.82  535.96   52.55
 1392.26   51.82 1637.49   41.22 2975.11   46.14 3751.26   38.14 3848.97   44.03
 3894.69   38.56 3919.42   28.24 3939.54   29.34 3966.28   41.96 4083.21   48.27
 4375.25   46.03 4434.12    41.6 4538.54    46.9 5425.69   47.86 5586.09   41.92
 5743.54   46.14 5820.07   41.82 6163.69   45.01 6254.91   41.94 6373.85   47.06
 6416.17   41.46 6514.68    39.7 6746.97   40.81 7431.33   60.07 8228.79   63.06
#Mann= 3 , 0 , 0
       0     .09       0 3894.69     .05       0 3966.28     .09       0
#XS Ineff= 2 , 0
         1383.36   56.12 4095.84           55.12
Permanent Ineff=
       F       F
Bank Sta=3894.69,3966.28
XS Rating Curve= 0 ,0
Exp/Cntr=0.3,0.1

Type RM Length L Ch R = 1 ,235600  ,2581.45,2626.07,2476.84
XS GIS Cut Line= 6
 2380450.4901123644998.0300903322377609.04431152643580.333679199
2376579.89971924642859.9324951172376228.27532959642516.884277344
2375576.48370361641916.5499267582374335.79290771639957.542297363
#Sta/Elev= 30
       0   89.43  177.25   92.43  353.57   87.43  590.45   52.83  639.05   48.73
  765.65   49.07  915.93   43.92 1003.31   49.12 1140.3548.30681 1231.38   41.74
 1405.32   42.03 1527.23   45.79 2202.83    40.2 3175.48   40.03 3281.22   44.34
 3303.68   40.08 3343.36   28.46 3375.09   30.77 3403.98   41.04 3447.94   42.48
 3498.26   51.09  3595.8   51.55 3743.36   44.72 3765.01   48.52 4000.52   50.79
 5226.26      50 6034.18   52.85 7389.92   52.72 7767.35    52.7 8127.94   62.07
#Mann= 13 ,-1 , 0
       0     .04       0  353.57     .08       0  765.65     .04       0
 1140.35     .08       0 1231.38    .032       0 1405.32     .08       0
 3303.68     .05       0 3403.98     .08       0 3498.26    .045       0
  3595.8     .05       0 5226.26    .045       0 6034.18     .05       0
 7389.92     .04       0
#XS Ineff= 2 , 0
         1048.82   53.44 3607.59           54.52
Permanent Ineff=
       F       F
Bank Sta=3303.68,3403.98
XS Rating Curve= 0 ,0
Exp/Cntr=0.3,0.1

Type RM Length L Ch R = 1 ,232974  ,1286.55,1324.52,777.13
XS GIS Cut Line= 6
2380869.46508789643750.2990722662380526.88848877643424.521484375
2377892.05908203642233.8695068362376897.21929932641513.468322754
2374916.11608887640638.695495605 2374392.9675293639952.599121094
#Sta/Elev= 30
       0  110.24   54.11  108.09  155.43    89.1  263.25   60.02  349.88   46.68
  534.49    42.7  894.75   44.75 1312.31    45.2 1337.15   40.96 1343.64   41.04
 1359.27   31.29 1370.14   28.53 1400.42   34.15 1413.7641.38347 1497.27   46.04
 1607.52   41.61 1947.13   42.24 2146.76   37.34 2206.04   38.05 2290.52    48.2
 2346.61   47.78 3370.16   53.53 3662.06      53 4289.2952.85733 4890.62   51.56
 6014.81   54.31 6946.09   52.35 7170.08   51.95  7447.3   61.38 7621.34   62.27
#Mann= 12 ,-1 , 0
       0     .04       0   54.11    .075       0  894.75     .04       0
 1337.15     .05       0 1343.64     .05       0 1413.76     .09       0
 2346.61     .05       0 3370.16    .045       0 3662.06     .05       0
 4289.29    .045       0 4890.62     .05       0 6946.09     .04       0
#XS Ineff= 2 ,-1
 2314.65 2664.45      51 2664.45 7621.34      53
Permanent Ineff=
       F       F
Bank Sta=1343.64,1413.76
XS Rating Curve= 0 ,0
Exp/Cntr=0.3,0.1

Type RM Length L Ch R = 1 ,231649  ,331.46,406.02,447.48
XS GIS Cut Line= 6
2380987.26092529643714.9605102542380626.96368408642907.941894531
2379300.33209229642150.5559082032378808.27227783642116.787109375
2375041.53167725640383.5003051762374456.39569092639967.190490723
#Sta/Elev= 30
       0  110.01  157.82  105.84  269.99   88.54  395.49   59.69  498.78   45.04
 1369.84   43.73 1550.98   44.36 1659.93   41.31 1699.08   45.67 1807.96   47.22
 1919.49   42.29 1998.01   42.63  2315.7   45.16 2392.53   39.24 2499.52   44.81
 2659.61    40.5  2678.9   28.56 2705.11      29 2731.13   40.62 2764.58    48.3
 2808.21   50.95 2979.74   43.85 3140.84   47.24 3726.25   51.01 4022.45   51.91
 4629.6352.36798 5278.01    53.3 7171.84   52.29 7523.16   61.16 7774.36    62.2
#Mann= 14 ,-1 , 0
       0     .04       0  157.82    .075       0 1369.84    .032       0
 1550.98    .075       0 1919.49    .032       0 1998.01    .075       0
 2659.61     .05       0 2731.13     .09       0 3140.84     .05       0
 3726.25    .045       0 4022.45     .05       0 4629.63    .045       0
 5278.01     .05       0 7171.84     .04       0
#XS Ineff= 2 , 0
                         2799.28           54.11
Permanent Ineff=
       F       F
Bank Sta=2659.61,2731.13
XS Rating Curve= 0 ,0
Exp/Cntr=0.5,0.3

Type RM Length L Ch R = 1 ,231243  ,96.56,62.42,66.51
BEGIN DESCRIPTION:
Surveyed Section
END DESCRIPTION:
XS GIS Cut Line= 6
2381584.30627441 643420.831909182381256.04571533643094.140075684
2380962.98071289642852.972106934 2379847.9307251642116.486083984
2378992.62890625641699.3016967772374782.68231201639857.597290039
#Sta/Elev= 30
       0   81.43  193.72   87.24   404.7   83.36  741.62   50.44  891.19   45.75
 1624.61   46.91  1819.6   41.952179.677   51.37 2208.56   50.38 2225.16   42.71
 2301.28   39.68 2575.67   48.16 2668.88   48.31    2750   41.712883.308   48.98
2966.812   40.323000.067   42.523047.995   30.913103.291   28.573135.691   36.34
3162.976   48.683229.044   48.97 3593.55   54.36 3970.23   52.26 4276.47   52.62
 4880.43   51.74 5601.17   53.23 6735.59   50.71 7312.53   57.03 7733.22   60.95
#Mann= 10 ,-1 , 0
       0     .04       0  741.62    .075       03000.067     .05       0
3135.691     .09       03229.044     .05       0 3970.23    .045       0
 4276.47     .05       0 4880.43    .045       0 5601.17     .05       0
 7312.53     .04       0
#XS Ineff= 3 ,-1
       0 2159.25   51.97 2479.37 2921.72   51.05 3201.23 7733.22   51.94
Permanent Ineff=
       F       F       F
Bank Sta=3000.067,3135.691
XS Rating Curve= 0 ,0
Exp/Cntr=0.5,0.3

Type RM Length L Ch R = 3 ,231211  ,,,
BEGIN DESCRIPTION:
SHEPPARD FERRY (SR. 1222)
END DESCRIPTION:
Bridge Culvert--1,0,-1,-1, 0
Deck Dist Width WeirC Skew NumUp NumDn MinLoCord MaxHiCord MaxSubmerge Is_Ogee
18,25,2.6,0, 60, 60, , , 0.98, 0, 1,1,,
       0   57.99  165.62  270.29  395.71  572.16  611.55  777.18  884.67 1134.99
 1754.212209.2542209.2542429.3712429.3712795.3452971.7172971.7173151.2313151.231
 3384.75 3669.28 3861.06 3924.42 4032.77 4063.14 4134.82 4149.59  4159.8 4233.24
 4285.68 4332.56 4423.88  4466.2 4478.62 4500.56 4542.22 4553.75 4640.68 4655.63
 4691.78 4710.94 4822.61 4876.51 4887.75 4898.76  4975.7 5528.83 6104.44 6522.22
 6715.11 6866.08 6905.92 6920.13 7143.21 7286.97 7343.02 7357.25 7367.97 7707.46
   79.63   79.55   77.89   75.06   69.81   60.39   58.94   54.45   52.88   52.06
      52   53.28   55.88   55.08   52.48   51.05    52.5    52.5    52.5    52.5
   51.58      52   50.99   51.84   51.62   52.38   52.17   51.38    52.7   51.85
   52.33   51.22   53.15   51.87   53.12   51.84   53.13   52.61   52.93    52.3
   53.06   52.24   52.33   51.52   52.09   51.31    51.2   52.94   51.59   52.95
   52.25   53.89   53.53   54.23   56.71    57.9   57.56   58.01   60.65   61.07
                                                                                
                   51.68   50.88                              51      51
                                                                                
                                                                                
                                                                                
                                                                                
       0   57.99  165.62  270.29  395.71  572.16  611.55  777.18  884.67 1134.99
 1754.212209.2542209.2542429.3712429.3712795.3452971.7172971.7173151.2313151.231
 3384.75 3669.28 3861.06 3924.42 4032.77 4063.14 4134.82 4149.59  4159.8 4233.24
 4285.68 4332.56 4423.88  4466.2 4478.62 4500.56 4542.22 4553.75 4640.68 4655.63
 4691.78 4710.94 4822.61 4876.51 4887.75 4898.76  4975.7 5528.83 6104.44 6522.22
 6715.11 6866.08 6905.92 6920.13 7143.21 7286.97 7343.02 7357.25 7367.97 7707.46
   79.63   79.55   77.89   75.06   69.81   60.39   58.94   54.45   52.88   52.06
      52   53.28   55.88   55.08   52.48   51.05    52.5    52.5    52.5    52.5
   51.58      52   50.99   51.84   51.62   52.38   52.17   51.38    52.7   51.85
   52.33   51.22   53.15   51.87   53.12   51.84   53.13   52.61   52.93    52.3
   53.06   52.24   52.33   51.52   52.09   51.31    51.2   52.94   51.59   52.95
   52.25   53.89   53.53   54.23   56.71    57.9   57.56   58.01   60.65   61.07
                                                                                
                   51.68   50.88                              51      51
                                                                                
                                                                                
                                                                                
                                                                                
Pier Skew, UpSta & Num, DnSta & Num=  ,2253.126, 4 ,2253.126, 4 , 3 , 3 , 0 ,,
       1       1       3       3
      25   48.43   48.43   51.43
       1       1       3       3
      25   48.43   48.43   51.43
Pier Skew, UpSta & Num, DnSta & Num=  ,2297.158, 4 ,2297.158, 4 , 3 , 3 , 0 ,,
       1       1       3       3
      25   48.35   48.35   51.35
       1       1       3       3
      25   48.35   48.35   51.35
Pier Skew, UpSta & Num, DnSta & Num=  ,2341.321, 4 ,2341.321, 4 , 3 , 3 , 0 ,,
       1       1       3       3
      25   48.18   48.18   51.18
       1       1       3       3
      25   48.18   48.18   51.18
Pier Skew, UpSta & Num, DnSta & Num=  ,2385.555, 4 ,2385.555, 4 , 3 , 3 , 0 ,,
       1       1       3       3
      25   48.06   48.06   51.06
       1       1       3       3
      25   48.06   48.06   51.06
Pier Skew, UpSta & Num, DnSta & Num=  ,3016.371, 4 ,3016.371, 4 , 3 , 3 , 0 ,,
       1       1     1.5     1.5
      25   49.98   49.98   50.98
       1       1     1.5     1.5
      25   49.98   49.98   50.98
Pier Skew, UpSta & Num, DnSta & Num=  ,3061.382, 4 ,3061.382, 4 , 3 , 3 , 0 ,,
       1       1     1.5     1.5
      25   49.99   49.99   50.99
       1       1     1.5     1.5
      25   49.99   49.99   50.99
Pier Skew, UpSta & Num, DnSta & Num=  ,3106.382, 4 ,3106.382, 4 , 3 , 3 , 0 ,,
       1       1     1.5     1.5
      25   49.94   49.94   50.94
       1       1     1.5     1.5
      25   49.94   49.94   50.94
Abutment Skew #Up #Dn= , 2 , 2
 2209.252225.937
 50.8217 42.8613
 2209.252233.954
 51.2266 43.0387
Abutment Skew #Up #Dn= , 3 , 2
2402.1332413.811 2429.37
  42.808   45.75    49.9
2403.363 2429.37
  43.769   50.88
BR Coef=-1 , 1 , 0 ,1.25, 0 ,,,0.8,0,2,0,
WSPro=,,,, 1 ,,,, 0 ,,,, 0 ,,,,-1 ,-1 ,-1 , 0 , 0 , 0 , 0 , 0
BC Design=,, 0 ,, 0 ,,,,,,
BC Use User HTab Curves=0
BC User HTab FreeFlow(D)= 0

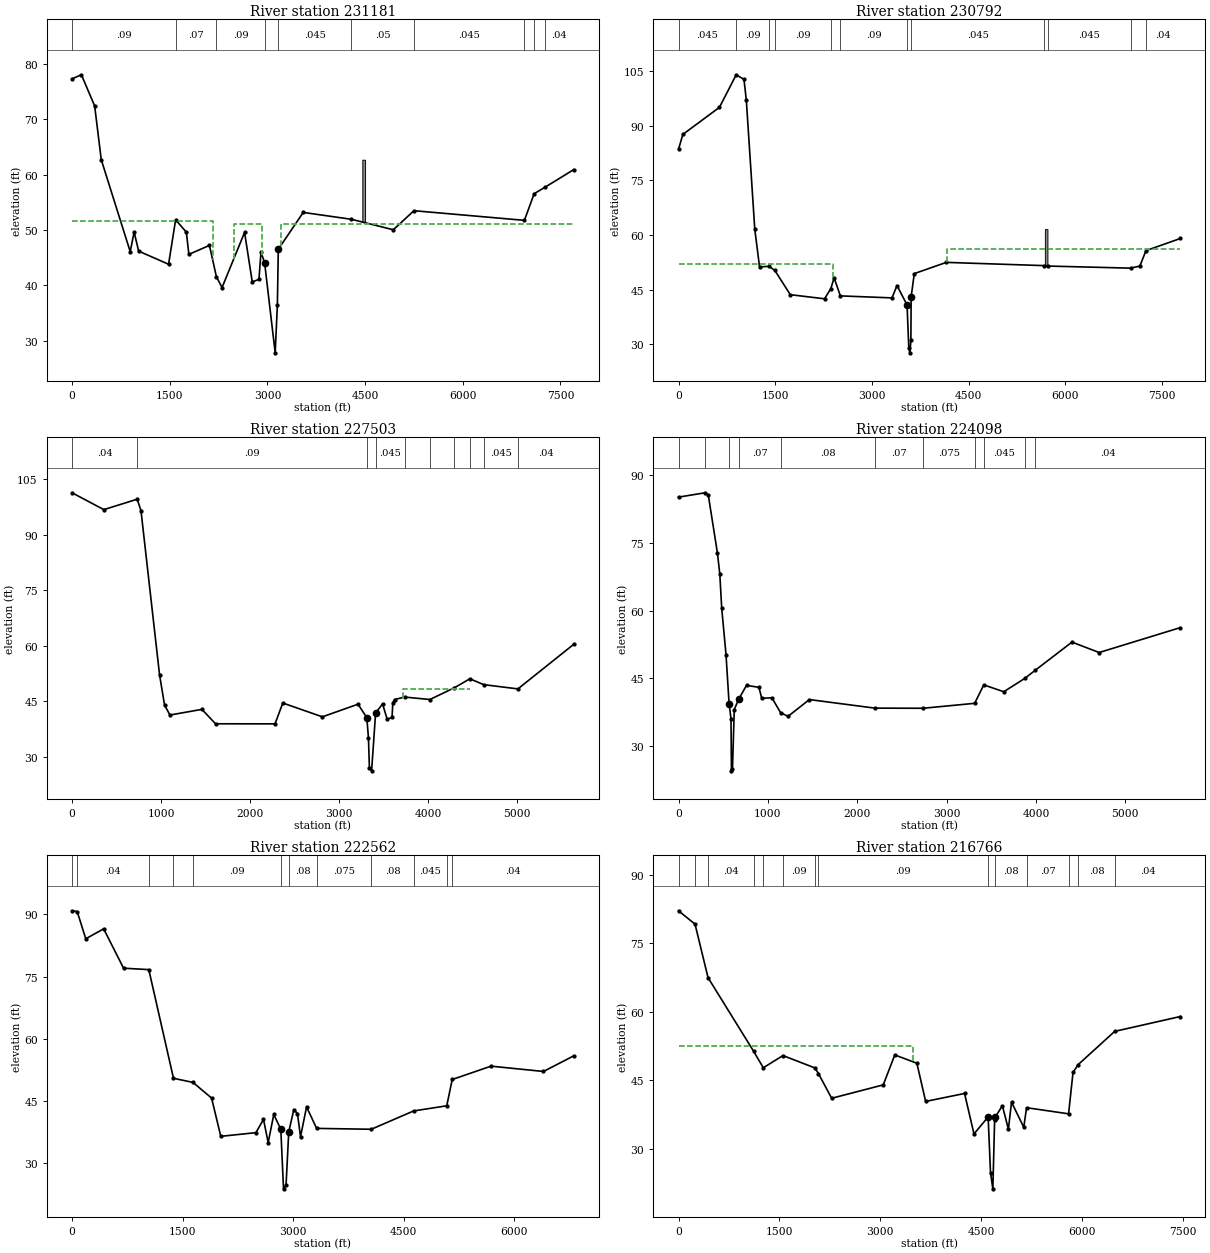
Type RM Length L Ch R = 1 ,231181  ,346.46,388.22,403
BEGIN DESCRIPTION:
Surveyed Section
END DESCRIPTION:
XS GIS Cut Line= 6
2381635.35430908643333.2468872072380985.07330322642748.232910156
2379914.22290039642056.7691040042379014.96447754641655.018493652
2377983.86932373641155.7216796882374851.42590332639785.235473633
#Sta/Elev= 30
       0   77.27  143.09      78  346.63   72.39  448.16   62.68  892.64   46.09
  953.25   49.62 1021.93   46.18 1481.92   43.81 1590.46   51.83 1754.77    49.6
 1793.68   45.59 2109.52   47.212216.221   41.572303.087    39.6 2648.96   49.55
 2766.91   40.63  2869.7   41.07 2901.21   46.05 2957.56      443119.109   27.82
  3152.7   36.423166.959   46.51 3550.04   53.16 4290.53   51.92 4933.18   50.03
 5249.89   53.47 6945.92 51.7288 7096.18   56.54 7256.46   57.66  7705.7    60.9
#Mann= 10 ,-1 , 0
       0     .09       0 1590.46     .07       02216.221     .09       0
 2957.56     .05       03166.959    .045       0 4290.53     .05       0
 5249.89    .045       0 6945.92      .1       0 7096.18    .055       0
 7256.46     .04       0
#XS Ineff= 3 ,-1
       0 2159.25   51.68 2479.37 2921.72      51 3201.23  7705.7      51
Permanent Ineff=
       F       F       F
#Block Obstruct= 1 ,-1
 4456.85 4499.69  62.677
Bank Sta=2957.56,3166.959
XS Rating Curve= 0 ,0
Exp/Cntr=0.5,0.3

Type RM Length L Ch R = 1 ,230792  ,2888.23,3289.64,2826.59
XS GIS Cut Line= 5
2382647.20050049642543.8734741212379572.62652588641527.143127441
2378740.73468018641038.2994995122377111.25592041640172.102905273
2375670.45349121639202.991699219
#Sta/Elev= 30
       0   83.58   67.43   87.63   634.8   95.06   894.5     104 1015.08  102.74
 1051.56   97.08 1182.74   61.62 1256.85   51.23 1402.08    51.4 1493.94   50.28
 1734.01   43.61 2265.34   42.48 2363.53    45.3  2413.5   48.25 2510.67   43.28
 3312.04   42.73 3389.32   46.12  3545.3   40.79 3572.83   28.91 3589.91   27.64
 3604.79   31.15 3608.85   43.02  3657.4    49.4 4154.67   52.48 5672.94   51.59
 5732.11   51.47 7012.74    50.9 7157.28   51.47 7251.74   55.71 7785.02   59.04
#Mann= 12 ,-1 , 0
       0    .045       0   894.5     .09       0 1402.08     .04       0
 1493.94     .09       0 2363.53     .07       0 2510.67     .09       0
  3545.3     .05       0 3608.85    .045       0 5672.94     .05       0
 5732.11    .045       0 7012.74      .1       0 7251.74     .04       0
#XS Ineff= 2 , 0
         2401.45   52.11 4166.37           56.12
Permanent Ineff=
       F       F
#Block Obstruct= 1 ,-1
 5683.41 5723.28  61.619
Bank Sta=3545.3,3608.85
XS Rating Curve= 0 ,0
Exp/Cntr=0.3,0.1

Type RM Length L Ch R = 1 ,227503  ,2833.61,3404.81,3350.76
XS GIS Cut Line= 4
2383378.31750488640133.5098876952382728.66992188639895.520324707
2380323.04449463638988.5864868162378063.21447754638251.033081055
#Sta/Elev= 30
       0  101.38  357.19   96.82  732.06   99.64   774.5   96.56  983.24   52.11
 1039.61   43.95 1099.85   41.25 1459.28   42.78 1612.69   38.88 2281.39   38.86
 2368.22    44.5 2813.47   40.76 3213.78   44.18 3312.76   40.54 3331.45      35
 3341.65      27 3366.68   26.15 3411.59   41.79 3489.74   44.25 3542.07    40.1
 3596.44    40.6 3605.01   44.61 3624.45   45.44 3737.58   46.11 4021.83   45.45
 4293.11   48.58 4471.33   51.05 4626.43   49.47 5011.07   48.32 5639.92   60.41
#Mann= 10 ,-1 , 0
       0     .04       0  732.06     .09       0 3312.76     .05       0
 3411.59    .045       0 3737.58     .08       0 4021.83    .045       0
 4293.11     .08       0 4471.33     .09       0 4626.43    .045       0
 5011.07     .04       0
#XS Ineff= 2 ,-1
 3716.09 4471.33   48.25 4471.33 5639.92      51
Permanent Ineff=
       F       F
Bank Sta=3312.76,3411.59
XS Rating Curve= 0 ,0
Exp/Cntr=0.3,0.1

Type RM Length L Ch R = 1 ,224098  ,1422.42,1536.32,1603.81
XS GIS Cut Line= 3
2383935.77069092638498.3134765632382433.02911377637872.488891602
2378644.49072266636624.651123047
#Sta/Elev= 30
       0   85.05  297.1286.00995  333.15    85.5  435.52   72.68  461.83   68.07
  483.37   60.47  531.61   50.24  565.98   39.43   587.2   36.12  592.33    24.6
  603.78      25  623.87   38.13  674.55   40.47  760.99   43.48  899.67   43.04
  931.28   40.62 1045.18   40.74 1142.98   37.42 1225.99   36.64 1464.62   40.34
 2197.77   38.45 2736.97   38.42 3314.35   39.51 3416.58   43.58 3640.23   42.07
 3874.33      45 3993.96   46.83 4403.63   53.03 4708.08   50.73  5616.6   56.23
#Mann= 11 ,-1 , 0
       0     .04       0  297.12     .09       0  565.98     .05       0
  674.55     .07       0 1142.98     .08       0 2197.77     .07       0
 2736.97    .075       0 3314.35     .09       0 3416.58    .045       0
 3874.33     .09       0 3993.96     .04       0
Bank Sta=565.98,674.55
XS Rating Curve= 0 ,0
Exp/Cntr=0.3,0.1

Type RM Length L Ch R = 1 ,222562  ,3496.03,5795.28,4019.83
XS GIS Cut Line= 3
2385402.60308838637377.7672729492381926.38153076636988.979309082
2378644.55389404636554.451477051
#Sta/Elev= 30
       0   90.83   69.45   90.65  185.96   84.09  428.56   86.48  698.76   77.01
    1041   76.67 1375.97   50.51 1640.1349.51842  1892.8   45.76 2017.77   36.54
 2494.24   37.42 2597.18   40.62 2660.95   35.03 2736.73    41.8 2832.23   38.24
 2869.04    23.9 2903.48   24.82 2939.85   37.63 3008.57   42.94 3058.12   42.03
 3099.72   36.44 3181.66   43.62  3318.438.44841 4059.15   38.24 4634.45   42.65
  5083.8   43.89 5158.01   50.22 5684.53   53.43 6396.36   52.15 6808.36   55.93
#Mann= 12 ,-1 , 0
       0     .09       0   69.45     .04       0    1041     .09       0
 1375.97     .04       0 1640.13     .09       0 2832.23     .05       0
 2939.85     .08       0  3318.4    .075       0 4059.15     .08       0
 4634.45    .045       0  5083.8     .09       0 5158.01     .04       0
Bank Sta=2832.23,2939.85
XS Rating Curve= 0 ,0
Exp/Cntr=0.3,0.1

Type RM Length L Ch R = 1 ,216766  ,3587.27,3814.23,3112.96
XS GIS Cut Line= 4
2385525.22729492636889.7987060552382703.65588379635363.234313965
2381031.29608154634599.9520874022378852.94012451633545.078918457
#Sta/Elev= 30
       0   82.09  245.65   79.16  439.04   67.46 1117.77   51.35 1261.13   47.75
 1553.82   50.42  2028.7   47.72 2082.46   46.47 2278.67   41.08 3046.18   44.01
 3218.04   50.56 3546.65   48.74    3677   40.39  4256.1   42.13 4396.21   33.28
 4606.95      37 4642.14   24.79 4677.14   21.27  4703.3   36.27  4715.5   37.01
  4818.7   39.47 4908.22   34.32 4954.99   40.23 5136.85   34.74  5178.9   39.02
 5803.87   37.68 5870.15   46.75 5947.97   48.46 6490.06   55.71  7466.7   58.96
#Mann= 14 ,-1 , 0
       0     .04       0  245.65     .09       0  439.04     .04       0
 1117.77     .09       0 1261.13    .032       0 1553.82     .09       0
  2028.7     .04       0 2082.46     .09       0 4606.95     .05       0
  4715.5     .08       0  5178.9     .07       0 5803.87     .09       0
 5947.97     .08       0 6490.06     .04       0
#XS Ineff= 2 , 0
         3493.67   52.54
Permanent Ineff=
       F       F
Bank Sta=4606.95,4715.5
XS Rating Curve= 0 ,0
Exp/Cntr=0.3,0.1