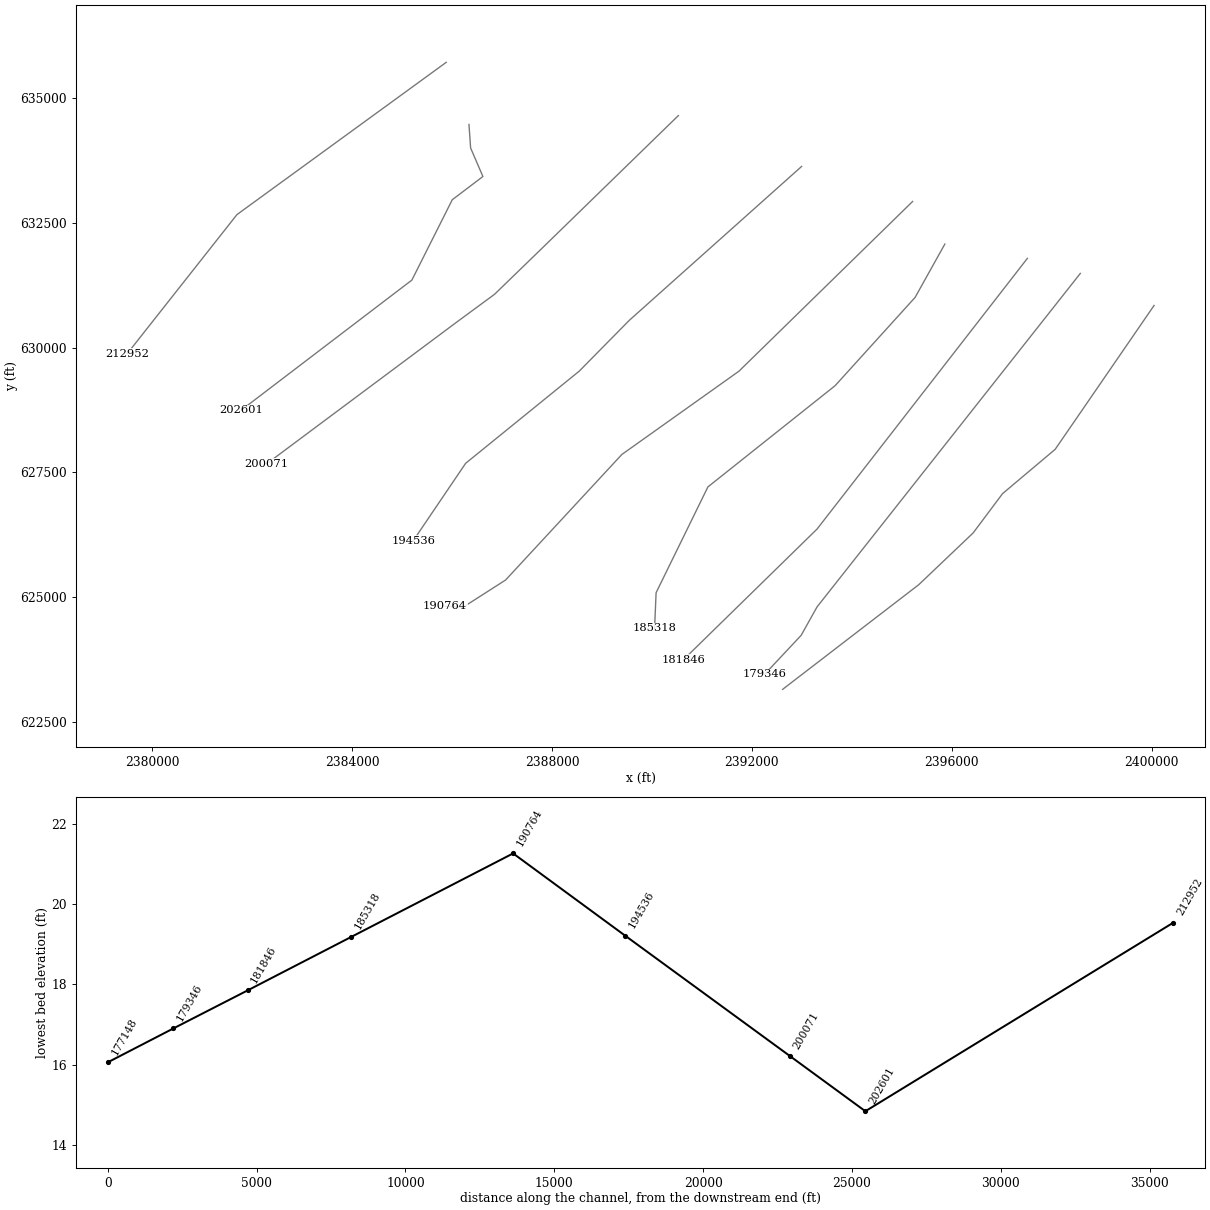
HEC-RAS study DTL_ContentneaCrk.prj: DTL_Contentnea_Crk

--- DTL_ContentneaCrk.g01 (geometry) --- (continued)

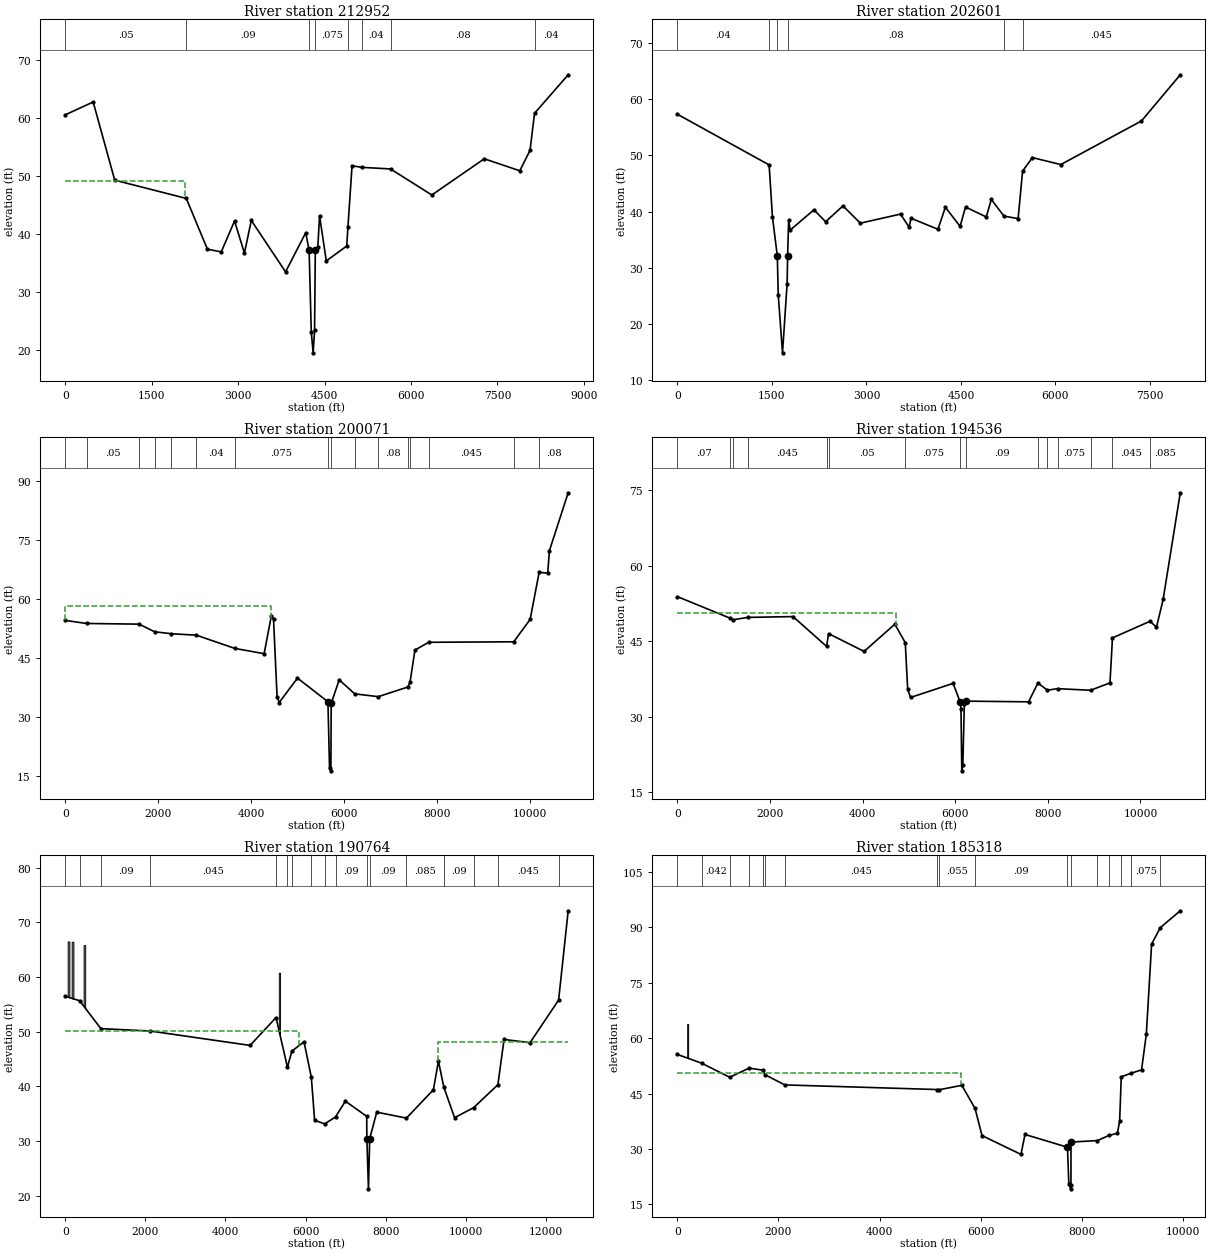
Type RM Length L Ch R = 1 ,212952  ,10208.16,10351.48,8140.62
XS GIS Cut Line= 3
2385882.87072754635712.0776977542381695.14172363632662.760498047
2379499.63330078629877.717285156
#Sta/Elev= 30
       0   60.56  484.53   62.77  858.52    49.3 2100.51   46.15 2466.33   37.41
 2706.61   36.93 2937.57   42.26 3109.21   36.72 3228.09   42.36 3822.52    33.5
 4172.88   40.24 4231.56    37.2 4269.01   23.14 4301.37   19.54 4326.14   23.39
 4339.19   37.24 4382.83    37.8 4412.51   43.17 4529.51   35.38 4884.15   37.95
 4905.26   41.26 4976.33   51.78  5143.5   51.51  5644.4   51.23 6360.69   46.74
 7270.42   52.98 7887.42   50.92 8064.98   54.44 8142.85   60.82 8726.66   67.46
#Mann= 8 ,-1 , 0
       0     .05       0 2100.51     .09       0 4231.56     .05       0
 4339.19    .075       0 4905.26     .08       0  5143.5     .04       0
  5644.4     .08       0 8142.85     .04       0
#XS Ineff= 2 , 0
         2070.52   49.13
Permanent Ineff=
       F       F
Bank Sta=4231.56,4339.19
XS Rating Curve= 0 ,0
Exp/Cntr=0.3,0.1

Type RM Length L Ch R = 1 ,202601  ,2464.96,2529.96,2293.83
BEGIN DESCRIPTION:
Surveyed Section
END DESCRIPTION:
XS GIS Cut Line= 6
2386338.54388428634467.4456787112386371.10668945633997.094482422
2386617.13671875633425.4368896482386003.81469727632959.529296875
2385196.19152832631351.4237060552381780.40332031628745.372680664
#Sta/Elev= 30
       0   57.34 1456.52 48.30591509.194 39.04631586.609 32.07541600.975  25.183
1668.813 14.83691742.237  27.1851750.218  32.169 1766.18 38.40821791.719 36.7093
 2167.76   40.31 2353.22   38.18 2628.18   41.01 2904.29   37.93 3541.45   39.55
 3678.65    37.2 3707.71   38.81 4135.54   36.84 4253.12   40.76 4487.54   37.37
 4573.05   40.81 4902.45   39.04 4982.69   42.16 5182.82   39.18 5407.75   38.75
 5478.92   47.21 5635.03   49.61 6085.13   48.37 7365.52   56.14 7980.94   64.36
#Mann= 6 ,-1 , 0
       0     .04       0 1456.52     .09       01586.609     .05       0
1750.218     .08       0 5182.82    .075       0 5478.92    .045       0
Bank Sta=1586.609,1750.218
XS Rating Curve= 0 ,0
Exp/Cntr=0.3,0.1

Type RM Length L Ch R = 1 ,200071  ,4463.45,5534.88,2756.87
XS GIS Cut Line= 5
2390529.09912109634646.0590820312387708.17492676631898.596496582
2386850.55432129631066.7045288092386070.11968994630492.098876953
 2382289.1663208627671.028320313
#Sta/Elev= 30
       0   54.56  459.81   53.78 1588.25   53.61 1921.48   51.67 2278.52   51.17
 2822.72   50.79 3646.0647.42742 4278.55   46.08 4432.34   55.68 4480.52   54.82
  4556.8   35.13 4602.64   33.63 4995.85   39.85 5650.85   33.82 5685.42   16.97
 5714.51   16.21 5721.17   33.43 5893.98   39.41 6226.43   35.84 6732.77   35.12
 7370.01   37.58 7416.54   38.76 7522.99      47 7816.85   48.98 9647.45   49.11
10000.89   54.81 10194.9   66.8210379.41   66.6210415.17   72.3410819.16    87.1
#Mann= 16 ,-1 , 0
       0      .1       0  459.81     .05       0 1588.25    .055       0
 1921.48    .045       0 2278.52     .05       0 2822.72     .04       0
 3646.06    .075       0 5650.85     .05       0 5721.17     .08       0
 6226.43    .032       0 6732.77     .08       0 7370.01     .09       0
 7416.54    .075       0 7816.85    .045       0 9647.45    .075       0
 10194.9     .08       0
#XS Ineff= 2 , 0
         4415.91   58.16
Permanent Ineff=
       F       F
Bank Sta=5650.85,5721.17
XS Rating Curve= 0 ,0
Exp/Cntr=0.3,0.1

Type RM Length L Ch R = 1 ,194536  ,2628.72,3771.82,2085.35
XS GIS Cut Line= 5
2392995.40307617633627.1071166992389549.67468262630547.296691895
2388543.39990234 629525.775329592386271.65869141627680.938476563
2385219.64428711626125.786682129
#Sta/Elev= 30
       0   53.83 1142.41   49.53 1193.45   49.22 1524.67    49.7 2498.45   49.86
    3222   43.94 3266.52   46.47 4032.21   42.94 4696.81   48.35  4921.5   44.67
 4973.98   35.38 5035.49   33.79 5954.99   36.59 6106.53   32.88 6124.54   31.56
  6142.1   19.21 6164.08   20.28 6196.95   32.45 6234.45   33.06  7584.3   32.92
 7785.13   36.65 7990.38   35.24 8211.91   35.54  8923.2 35.2205 9341.56   36.69
 9395.59   45.6310207.88   48.9310345.48   47.7510489.26   53.2610859.44   74.46
#Mann= 15 ,-1 , 0
       0     .07       0 1142.41    .045       0 1193.45     .07       0
 1524.67    .045       0    3222     .05       0 3266.52     .05       0
  4921.5    .075       0 6106.53     .05       0 6234.45     .09       0
 7785.13     .07       0 7990.38     .08       0 8211.91    .075       0
  8923.2     .09       0 9395.59    .045       010207.88    .085       0
#XS Ineff= 2 , 0
         4719.71    50.5
Permanent Ineff=
       F       F
Bank Sta=6106.53,6234.45
XS Rating Curve= 0 ,0
Exp/Cntr=0.3,0.1

Type RM Length L Ch R = 1 ,190764  ,1824.14,5445.95,3330.14
BEGIN DESCRIPTION:
Surveyed Section
END DESCRIPTION:
XS GIS Cut Line= 6
2395217.11853027632925.8350830082391740.89691162629525.846496582
2389397.25067139627857.422729492 2387071.1942749625343.312927246
2386213.57391357624794.4359130862385859.09069824624817.305725098
#Sta/Elev= 30
       0   56.48   360.4   55.64  889.07   50.55 2124.72   50.11 4614.61   47.48
 5262.82   52.57 5547.88    43.5 5658.38   46.44  5961.8   48.14 6144.36   41.65
 6226.22    33.8 6477.13   33.13 6749.62   34.42 6994.31   37.297526.929 34.5122
7530.696 30.4116 7570.88 21.26427601.018 30.4116 7777.47   35.28 8518.97   34.19
  9192.3   39.38 9317.27   44.63 9453.24   39.84 9720.63   34.27 10197.9   36.11
10801.91   40.2910956.55   48.5711605.49   47.9812318.85   55.7812557.44   72.09
#Mann= 17 ,-1 , 0
       0    .065       0   360.4    .065       0  889.07     .09       0
 2124.72    .045       0 5262.82    .055       0 5547.88    .045       0
 5658.38    .055       0 6144.36    .075       0 6477.13    .032       0
 6749.62     .09       07530.696     .05       07601.018     .09       0
 8518.97    .085       0 9453.24     .09       0 10197.9     .07       0
10801.91    .045       012318.85    .065       0
#XS Ineff= 2 , 0
         5835.44    50.1 9316.46           48.09
Permanent Ineff=
       F       F
#Block Obstruct= 4 ,-1
   60.83  103.12  66.479  160.32  203.87  66.428  457.82  498.18  65.812
 5332.17 5363.52  60.758
Bank Sta=7530.696,7601.018
XS Rating Curve= 0 ,0
Exp/Cntr=0.3,0.1

Type RM Length L Ch R = 1 ,185318  ,2368.11,3471.88,2113.12
XS GIS Cut Line= 6
 2395861.7612915632071.9553222662395267.14428711631004.694274902
2393666.25292969629236.0902709962391120.07287598627208.294311523
2390083.30511475625089.0189208982390052.81188965624372.429321289
#Sta/Elev= 30
       0   55.58  479.52   53.22 1035.64    49.4 1417.66   51.86 1696.21   51.32
 1734.02   50.09 2124.99   47.33 5131.42   46.08 5167.24   45.98 5627.03   47.22
  5889.5   40.94 6026.85    33.6 6797.52   28.51 6876.75   33.91 7717.03   30.45
 7744.25   20.51 7781.75   19.18 7786.38   20.19 7786.67   31.85 8310.96   32.25
 8535.79   33.64 8705.75   34.22 8749.15   37.58 8781.52   49.52 8979.49   50.51
 9182.72    51.4 9277.21    61.1 9381.49   85.46 9554.51   89.94 9948.47   94.49
#Mann= 17 ,-1 , 0
       0    .045       0  479.52    .042       0 1035.64    .065       0
 1417.66     .04       0 1696.21    .065       0 1734.02     .09       0
 2124.99    .045       0 5131.42     .04       0 5167.24    .055       0
  5889.5     .09       0 7717.03     .05       0 7786.67     .09       0
 8310.96    .075       0 8535.79     .09       0 8781.52    .032       0
 8979.49    .075       0 9554.51    .045       0
#XS Ineff= 2 , 0
         5614.83    50.5
Permanent Ineff=
       F       F
#Block Obstruct= 1 ,-1
   194.1  214.32  63.831
Bank Sta=7717.03,7786.67
XS Rating Curve= 0 ,0
Exp/Cntr=0.3,0.1

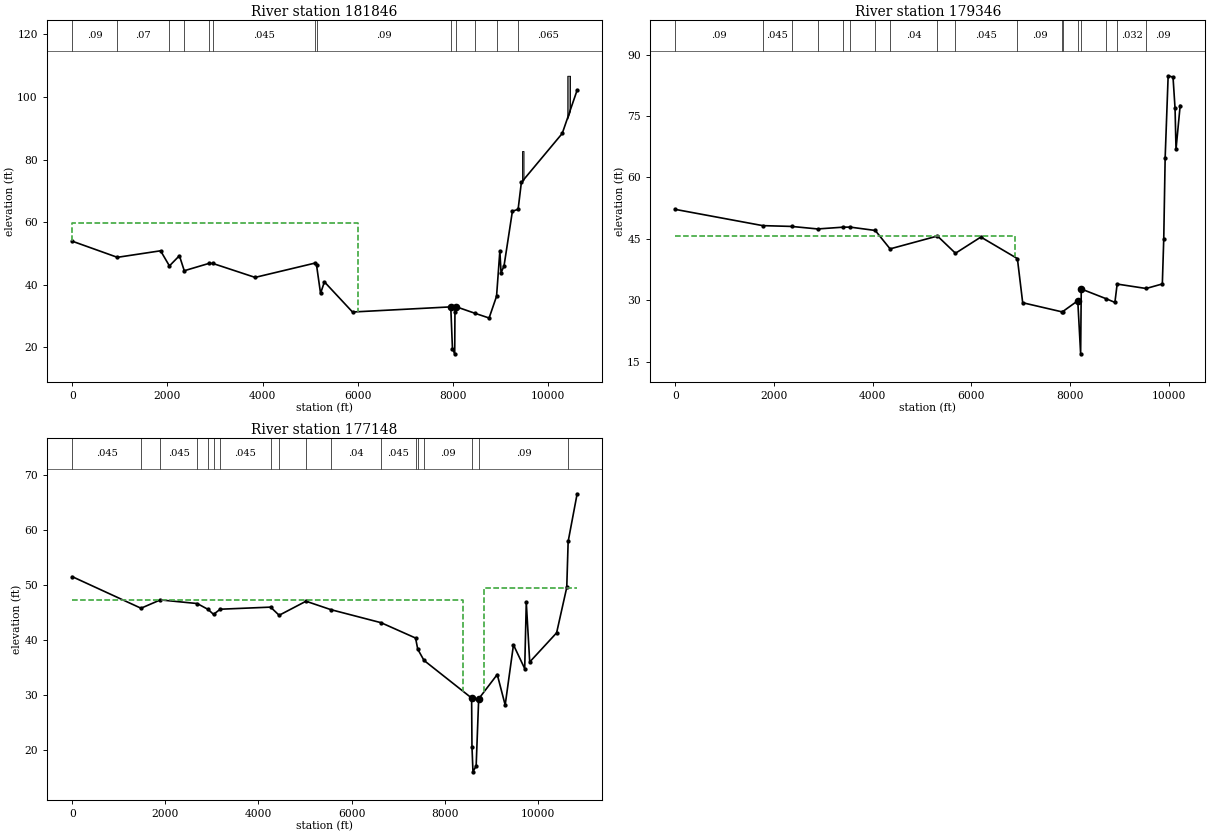
Type RM Length L Ch R = 1 ,181846  ,1042.03,2499.8,1274.25
XS GIS Cut Line= 3
 2397513.3059082631785.2064819342393305.24829102626365.045288086
2390629.47247314623746.444091797
#Sta/Elev= 30
       0   53.88  948.16   48.72 1855.99   50.81 2041.62   45.97 2251.29   49.24
 2353.43   44.43 2873.12   46.78 2955.8446.74591 3841.06    42.3 5095.04   46.86
  5131.1   46.31 5216.19   37.19  5297.2   40.87 5887.22   31.23 7951.19   32.87
 7986.81   19.47 8033.88   17.85 8039.22   31.29 8055.43   32.96 8461.33   30.81
 8756.54   29.31 8913.14   36.27 8982.62   50.75 9007.56    43.8 9069.59   45.92
  9245.9   63.46 9366.01   64.08 9434.14   72.6710292.57   88.3410605.83  102.18
#Mann= 13 ,-1 , 0
       0     .09       0  948.16     .07       0 2041.62     .09       0
 2353.43     .12       0 2873.12    .055       0 2955.84    .045       0
 5095.04     .04       0  5131.1     .09       0 7951.19     .05       0
 8055.43     .09       0 8461.33    .075       0 8913.14     .09       0
 9366.01    .065       0
#XS Ineff= 2 , 0
            6000    59.8
Permanent Ineff=
       F       F
#Block Obstruct= 2 ,-1
 9447.83  9479.6  82.71510398.9910456.07 106.787
Bank Sta=7951.19,8055.43
XS Rating Curve= 0 ,0
Exp/Cntr=0.3,0.1

Type RM Length L Ch R = 1 ,179346  ,1198.33,2198.27,859.74
XS GIS Cut Line= 4
2398572.88470459631484.0416870122393303.67547607624803.830871582
2392986.75128174 624236.123107912392255.06988525623454.836120605
#Sta/Elev= 30
       0    52.2 1772.65   48.23 2356.7248.03631 2884.52   47.42 3395.97   47.85
 3542.24   47.87 4051.63   47.05 4352.36   42.55 5311.82   45.69 5676.99   41.48
 6191.13   45.44 6931.04   40.18 7038.61   29.39 7827.09   27.18  7845.5   27.19
 8154.41   29.87 8212.38    16.9 8224.99   32.75 8722.11    30.4 8906.52   29.47
 8952.25   33.95 9539.39   32.87 9867.54   33.98  9896.2   44.99 9924.69   64.86
 9985.42   84.8510084.04   84.5210125.05   76.9110144.54    66.910228.81   77.58
#Mann= 18 ,-1 , 0
       0     .09       0 1772.65    .045       0 2356.72     .09       0
 2884.52     .09       0 3395.97    .045       0 3542.24    .065       0
 4051.63    .045       0 4352.36     .04       0 5311.82     .09       0
 5676.99    .045       0 6931.04     .09       0 7827.09    .032       0
  7845.5     .09       0 8154.41     .05       0 8224.99     .09       0
 8722.11    .075       0 8952.25    .032       0 9539.39     .09       0
#XS Ineff= 2 , 0
         6878.84   45.59
Permanent Ineff=
       F       F
Bank Sta=8154.41,8224.99
XS Rating Curve= 0 ,0
Exp/Cntr=0.5,0.3

Type RM Length L Ch R = 1 ,177148  ,157.67,165.6,179.39
BEGIN DESCRIPTION:
Surveyed Section
END DESCRIPTION:
XS GIS Cut Line= 6
2400049.27429199630842.4376831052398070.46630859627961.559509277
2397017.59747314627074.3477172852396427.48748779626285.561279297
2395340.02191162625250.0811157232392615.30010986623153.300476074
#Sta/Elev= 30
       0   51.48 1477.17   45.75 1892.56   47.26 2685.38    46.6 2918.56   45.53
 3035.69   44.63 3177.77   45.57 4261.25   45.95 4444.54   44.47 5021.52   47.02
 5560.55   45.48 6635.35   43.12 7375.03   40.34 7421.66   38.32 7556.15   36.28
 8578.89 29.45318586.482 20.65098608.173 16.0574  8676.5  17.1268730.729 29.2993
 9129.58   33.72 9299.84   28.18 9477.86    39.1 9719.26   34.79 9753.13   46.81
 9826.99   35.9910404.42   41.28 10622.6   49.5310652.57   57.8610845.63   66.52
#Mann= 18 ,-1 , 0
       0    .045       0 1477.17    .055       0 1892.56    .045       0
 2685.38    .055       0 2918.56    .045       0 3035.69     .09       0
 3177.77    .045       0 4261.25     .07       0 4444.54    .045       0
 5021.52    .045       0 5560.55     .04       0 6635.35    .045       0
 7375.03     .09       0 7421.66    .032       0 7556.15     .09       0
 8578.89     .05       08730.729     .09       010652.57    .045       0
#XS Ineff= 2 , 0
       0 8404.52   47.21 8843.96       0   49.44
Permanent Ineff=
       F       F
Bank Sta=8578.89,8730.729
XS Rating Curve= 0 ,0
Exp/Cntr=0.5,0.3