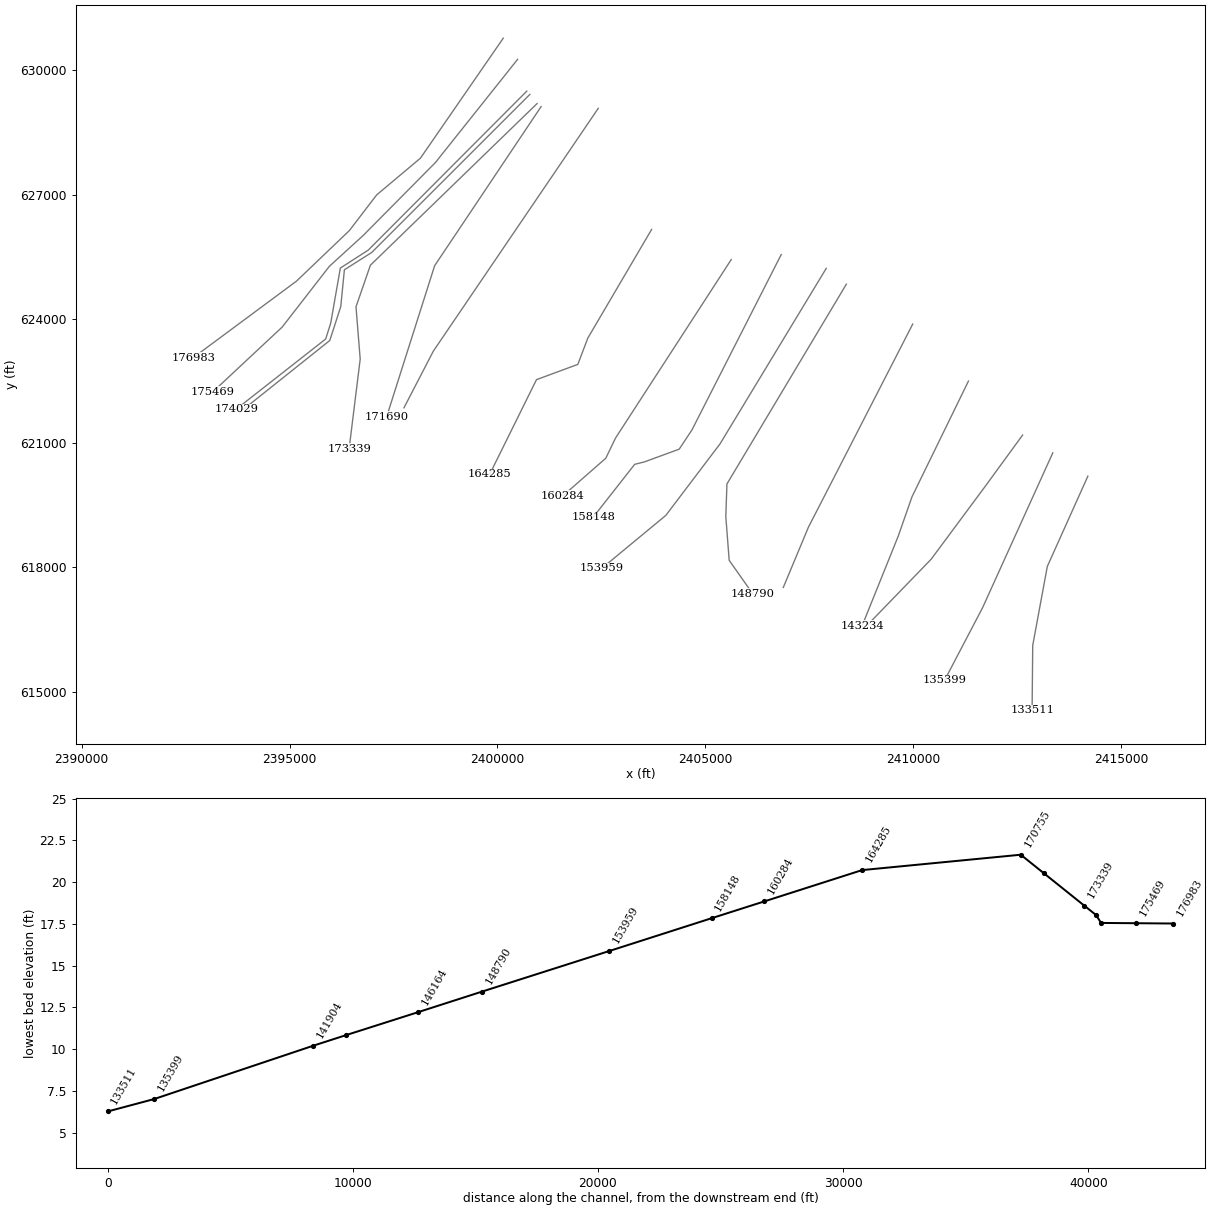
HEC-RAS study DTL_ContentneaCrk.prj: DTL_Contentnea_Crk

--- DTL_ContentneaCrk.g01 (geometry) --- (continued)

Type RM Length L Ch R = 3 ,177046  ,,,
BEGIN DESCRIPTION:
RT 258
RT 258
END DESCRIPTION:
Bridge Culvert--1,0,-1,-1, 0
Deck Dist Width WeirC Skew NumUp NumDn MinLoCord MaxHiCord MaxSubmerge Is_Ogee
77,35,2.6,0, 60, 60, , , 0.98, 0, 1,1,,
       0   87.91  157.92  246.48  263.16  353.64     675  712.48   758.1  812.42
  829.89  868.92  929.44  950.85  968.44 1043.17  1159.6 1216.56 1234.97 1258.34
  1274.6 1295.51 1874.26 2046.72 2674.33 2782.66  2873.5 2962.17 3031.27 3118.66
 3241.34  3488.9 3587.35 4065.77 4416.18 4558.69  4581.1 4762.72 4908.48 5036.48
 5098.94 5126.84 5276.79 5366.68 5568.58 6268.72 6917.118454.5218454.521 8793.96
 8793.969118.216 9733.83 9899.4810182.7210290.1910428.3910523.21 10687.9 10844.7
   51.41   50.74   49.15   50.36      50   50.61   49.83   51.06   51.58   49.94
   48.75   48.21   46.12   46.41    45.8    45.4   45.94   44.32   45.88    45.8
   44.86   46.06   45.79   46.43   46.91   46.45   46.94   46.14   46.48      46
   46.67   46.28   46.91   46.99   45.92    46.6   46.15   46.54   47.45   47.67
   47.14   47.72   48.05   47.21   46.98   49.11   50.16 51.6066  54.207  54.478
 51.8782   52.19   50.99    49.9   49.44   49.82   51.05   52.72   57.62   63.15
                                                                                
                                                                                
                                                                                
                                                                                
                                                                  47.907  48.178
                                                                                
       0   87.91  157.92  246.48  263.16  353.64     675  712.48   758.1  812.42
  829.89  868.92  929.44  950.85  968.44 1043.17  1159.6 1216.56 1234.97 1258.34
  1274.6 1295.51 1874.26 2046.72 2674.33 2782.66  2873.5 2962.17 3031.27 3118.66
 3241.34  3488.9 3587.35 4065.77 4416.18 4558.69  4581.1 4762.72 4908.48 5036.48
 5098.94 5126.84 5276.79 5366.68 5568.58 6268.72 6917.118454.5218454.521 8793.96
 8793.969118.216 9733.83 9899.4810182.7210290.1910428.3910523.21 10687.9 10844.7
   51.41   50.74   49.15   50.36      50   50.61   49.83   51.06   51.58   49.94
   48.75   48.21   46.12   46.41    45.8    45.4   45.94   44.32   45.88    45.8
   44.86   46.06   45.79   46.43   46.91   46.45   46.94   46.14   46.48      46
   46.67   46.28   46.91   46.99   45.92    46.6   46.15   46.54   47.45   47.67
   47.14   47.72   48.05   47.21   46.98   49.11   50.16 51.6066  54.207  54.478
 51.8782   52.19   50.99    49.9   49.44   49.82   51.05   52.72   57.62   63.15
                                                                                
                                                                                
                                                                                
                                                                                
                                                                  47.907  48.178
                                                                                
Pier Skew, UpSta & Num, DnSta & Num=  ,8521.758, 4 ,8521.758, 4 , 3 , 3 , 0 ,,
     1.5     1.5     2.5     2.5
      10 44.9206 44.9206 47.9206
     1.5     1.5     2.5     2.5
      10 44.9206 44.9206 47.9206
Pier Skew, UpSta & Num, DnSta & Num=  ,8590.08, 4 ,8590.08, 4 , 3 , 3 , 0 ,,
     1.5     1.5     2.5     2.5
      10  44.942  44.942  47.942
     1.5     1.5     2.5     2.5
      10  44.942  44.942  47.942
Pier Skew, UpSta & Num, DnSta & Num=  ,8657.317, 4 ,8657.317, 4 , 3 , 3 , 0 ,,
     1.5     1.5     2.5     2.5
      10 45.0139 45.0139 48.0139
     1.5     1.5     2.5     2.5
      10 45.0139 45.0139 48.0139
Pier Skew, UpSta & Num, DnSta & Num=  ,8725.638, 4 ,8725.638, 4 , 3 , 3 , 0 ,,
     1.5     1.5     2.5     2.5
      10 45.1313 45.1313 48.1313
     1.5     1.5     2.5     2.5
      10 45.1313 45.1313 48.1313
Abutment Skew #Up #Dn= , 2 , 2
8454.5218490.841
  47.907  31.004
8454.5218488.371
 46.0082 32.0935
Abutment Skew #Up #Dn= , 2 , 2
 8749.56 8793.96
 31.4869  48.178
 8762.21 8793.96
 32.1991 46.3303
BR Coef=-1 , 1 , 0 ,1.25, 0 ,,,0.8,0,2,0,
WSPro=,,,, 1 ,,,, 0 ,,,, 0 ,,,,-1 ,-1 ,-1 , 0 , 0 , 0 , 0 , 0
BC Design=,, 0 ,, 0 ,,,,,,
BC Use User HTab Curves=0
BC User HTab FreeFlow(D)= 0

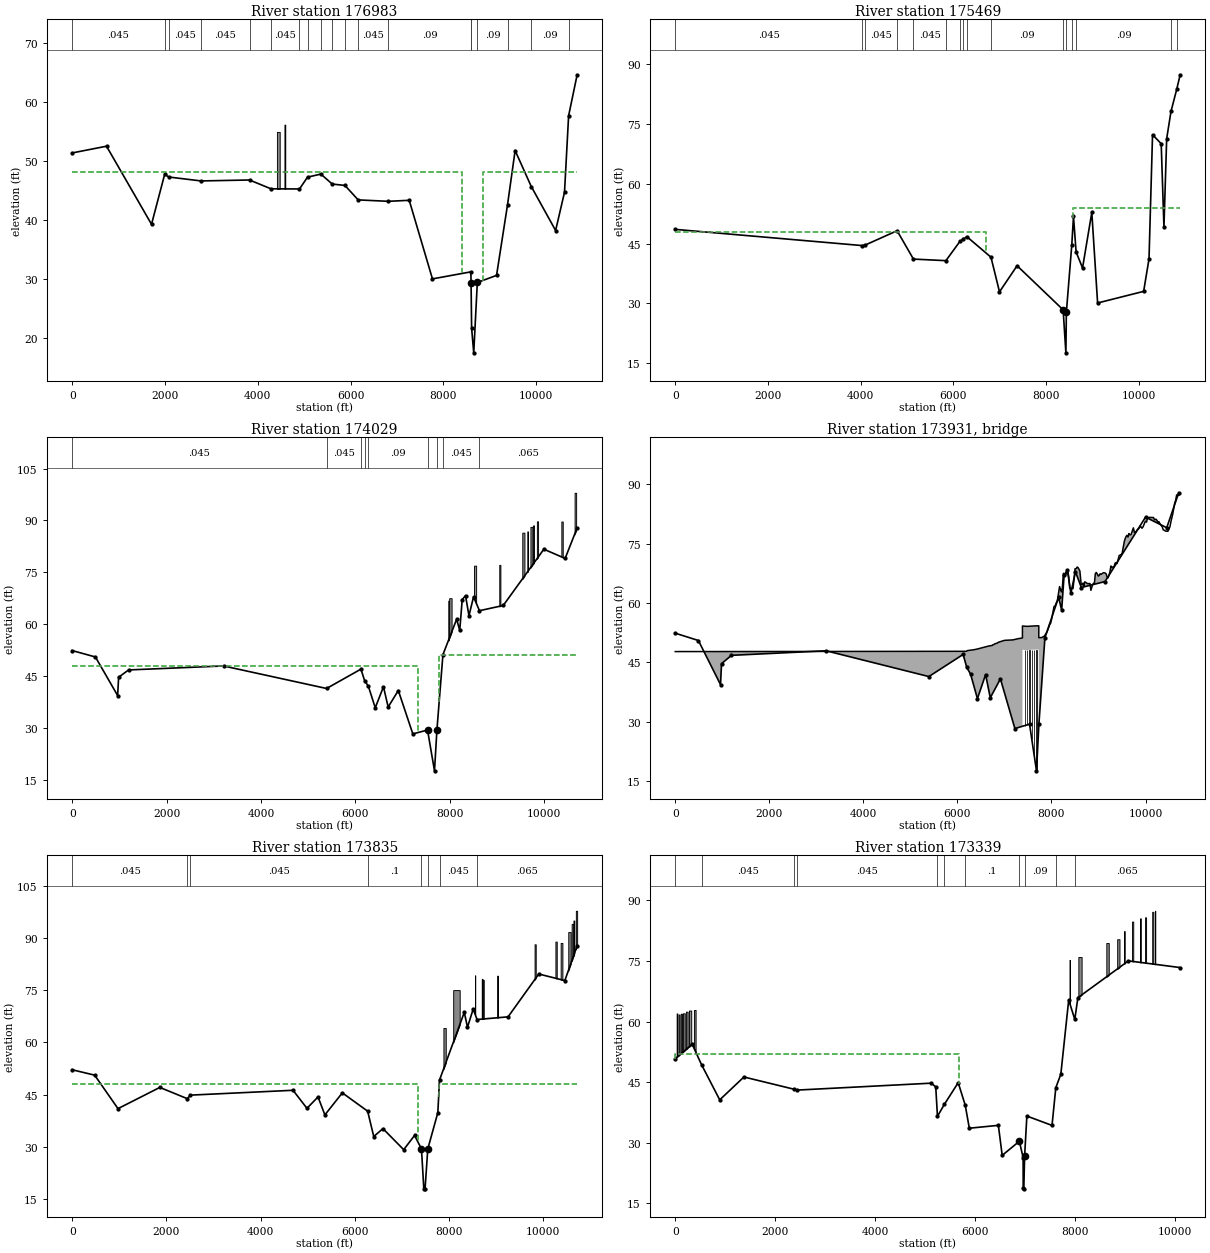
Type RM Length L Ch R = 1 ,176983  ,459.23,1513.82,832.09
BEGIN DESCRIPTION:
Surveyed Section
END DESCRIPTION:
XS GIS Cut Line= 6
2400141.90692139630775.9907226562398149.61932373627879.409912109
2397096.76208496626991.9506835942396440.27111816626131.574707031
 2395168.6494751624910.7542724612392683.02087402623061.595092773
#Sta/Elev= 30
       0   51.36     739    52.5 1709.09   39.28 1992.73   47.74 2084.15   47.28
 2777.42   46.62 3821.12   46.78 4282.58   45.29 4898.57   45.26 5071.61   47.26
 5358.93   47.78 5604.89   46.09 5878.07   45.86 6163.21   43.41 6811.85   43.17
 7263.77   43.34 7764.53   30.048592.363 31.22858596.717 29.37678608.688 21.6928
8654.398 17.5211 8731.67 29.4318 9145.94   30.63 9382.49   42.58 9546.17   51.77
 9895.09   45.6610419.04   38.2310610.83    44.710699.36   57.6610883.12   64.59
#Mann= 19 ,-1 , 0
       0    .045       0 1992.73     .05       0 2084.15    .045       0
 2777.42    .045       0 3821.12     .06       0 4282.58    .045       0
 4898.57    .055       0 5071.61     .07       0 5358.93    .045       0
 5604.89     .07       0 5878.07     .04       0 6163.21    .045       0
 6811.85     .09       08592.363    .032       08596.717     .05       0
 8731.67     .09       0 9382.49     .04       0 9895.09     .09       0
10699.36    .045       0
#XS Ineff= 2 , 0
       0 8404.52   48.18 8843.96       0   48.18
Permanent Ineff=
       F       F
#Block Obstruct= 2 ,-1
 4411.98 4472.25  54.919 4574.11 4591.95  56.147
Bank Sta=8596.717,8731.67
XS Rating Curve= 0 ,0
Exp/Cntr=0.5,0.3

Type RM Length L Ch R = 1 ,175469  ,715.81,1440.11,1060.76
XS GIS Cut Line= 6
2400486.39031982630264.3596801762398508.14569092627771.542907715
2396770.03491211626010.5620727542395958.15429688 625267.29107666
2394826.09527588623803.6188964842393156.59411621622237.032104492
#Sta/Elev= 30
       0   48.55 4035.23   44.48 4089.7244.56488 4788.23   48.21 5140.21   41.09
  5840.9   40.69 6142.75   45.51 6210.31   46.05 6293.13   46.72 6814.02   41.56
 6997.92   32.86 7377.68   39.42 8371.23   28.35  8430.8   17.54 8440.97   27.72
 8558.66   44.74 8594.63   51.79 8651.28   42.87 8790.11   38.86 8990.23   52.81
 9115.24   30.0610108.78   32.9810224.57   41.1310300.92   72.3310487.86   70.07
10546.98   49.1310605.82   71.3110698.87   78.16   10822    83.7 10897.2   87.38
#Mann= 16 ,-1 , 0
       0    .045       0 4035.23     .06       0 4089.72    .045       0
 4788.23     .07       0 5140.21    .045       0  5840.9     .07       0
 6142.75    .065       0 6210.31     .04       0 6293.13    .045       0
 6814.02     .09       0 8371.23     .05       0 8440.97     .09       0
 8558.66     .04       0 8651.28     .09       010698.87    .065       0
   10822     .09       0
#XS Ineff= 2 , 0
         6705.24   47.99 8593.13           53.88
Permanent Ineff=
       F       F
Bank Sta=8371.23,8440.97
XS Rating Curve= 0 ,0
Exp/Cntr=0.5,0.3

Type RM Length L Ch R = 1 ,174029  ,183.37,193.38,156.27
BEGIN DESCRIPTION:
Surveyed Section
END DESCRIPTION:
XS GIS Cut Line= 6
2400707.65911865629497.460693359 2396894.5480957625659.372924805
2396222.47570801625225.3883056642395990.59411621623894.092895508
2395869.07287598623511.7183227542393720.13232422 621819.86328125
#Sta/Elev= 30
       0   52.35  491.91    50.5  962.75   39.34  983.82   44.64 1195.36   46.75
 3208.14    47.9 5392.2641.38368 6121.29   46.98 6198.37   43.69 6279.73   41.99
 6424.95    35.8 6598.92   41.88 6698.42   36.02 6913.88    40.8 7221.51   28.24
7533.329 29.36187681.062  17.5567732.448 29.42157859.841 51.1733 8150.48   61.42
 8215.85    58.2 8268.76    67.1 8338.84   68.26 8411.75   62.44 8508.88   67.89
  8634.9   63.89 9138.49    65.4 9999.67   81.6810450.62   79.01 10705.3   87.84
#Mann= 9 ,-1 , 0
       0    .045       0 5392.26    .045       0 6121.29     .04       0
 6198.37    .045       0 6279.73     .09       07533.329     .05       0
7732.448     .09       07859.841    .045       0  8634.9    .065       0
#XS Ineff= 3 ,-1
                               0 7332.07   47.77 7779.91 10705.3   51.21
Permanent Ineff=
       F       F       F
#Block Obstruct= 11 ,-1
 7974.55 7985.79  66.803 7992.08 8043.46  67.503 8518.92 8563.82  76.923
  9054.1 9078.04  77.148 9542.09 9588.16  86.471 9648.24 9663.96  86.827
    9715 9756.75  88.146 9769.32    9791  88.565 9851.78 9877.03  89.732
10370.3810399.88  89.69410651.1810684.01  98.007
Bank Sta=7533.329,7732.448
XS Rating Curve= 0 ,0
Exp/Cntr=0.5,0.3

Type RM Length L Ch R = 3 ,173931  ,,,
BEGIN DESCRIPTION:
RT 258
END DESCRIPTION:
Bridge Culvert--1,0,-1,-1, 0
Deck Dist Width WeirC Skew NumUp NumDn MinLoCord MaxHiCord MaxSubmerge Is_Ogee
79.3,25,2.6,0, 155, 155, , , 0.98, 0, 1,1,,
       0 6190.38 6208.21 6348.59  6411.8 6513.35  6576.9 6601.42 6673.09  6690.4
 6710.12  6736.8  6753.8 6775.71  6803.3 6831.67 6876.26 7001.14 7180.237240.351
7298.3267358.4477382.0667382.0667432.5267481.911 7532.377581.7567632.215  7681.6
7729.9127729.912 7788.967848.0087905.983 7961.81 7980.26 8002.74 8054.38 8076.52
 8104.94 8122.06 8171.76 8209.17 8230.19 8252.92 8269.82 8293.48 8323.95 8344.63
 8367.44 8387.21 8411.35 8433.23    8457  8483.4 8500.76 8527.92 8544.29 8562.66
 8587.06  8603.2 8628.69 8632.82 8653.36 8671.96 8690.31 8707.33 8728.09 8768.89
 8800.27 8819.08 8837.64 8856.61 8874.15 8895.46 8912.45 8932.59 8952.84 8970.92
 8997.09 9013.91 9034.62 9050.95 9073.62 9099.74  9138.9 9160.43 9177.93 9194.51
 9210.97 9240.41 9264.28 9281.43 9331.98 9351.27  9371.3  9394.1 9414.63 9437.92
 9455.63 9477.88 9501.93 9529.03 9548.29  9569.6 9586.53 9602.95 9626.71 9644.94
 9666.67 9690.53 9741.04 9764.55 9783.07 9800.01 9816.58    9838 9862.47 9883.99
 9901.85 9923.86 9948.65 9975.53 9996.0510021.3810042.9710063.4410091.0710111.84
 10132.710169.5210190.8710220.7510244.4710264.72 10283.210302.2710332.4710354.62
10376.8810396.9910419.42 10453.610474.9910494.4410516.9810543.3810575.1510620.95
10638.0410661.3310696.6210714.79   10736
    47.7   47.77   47.94   48.17   48.32   48.63   48.81   48.87   49.13   49.13
   49.21   49.23   49.41   49.49   49.71   49.77   50.08   50.54  50.657  50.836
  50.983  51.087  51.165  54.165  54.109  54.076  54.117  54.176  54.179  54.214
  54.214  51.214  51.241  51.606  52.701  54.551    54.8   55.92   59.11   59.21
   60.11   60.41   64.13   62.78   63.78   67.48   67.34   66.92   67.62   68.06
   66.57   63.73   63.65   63.69    63.6   66.38   68.64   68.68   69.06   68.97
   68.44   68.09   64.98   64.78   64.56   65.02   64.25   65.33    65.2   64.85
    64.9   64.88   63.19   63.89   64.62   64.96   64.93   67.44   67.69   67.36
   66.78   66.97   67.37   67.22   67.39   67.62   67.58   67.37   66.73   66.27
   66.61   67.75   69.34   68.97   69.22   70.04   70.19   69.95   70.84   71.94
   72.09   72.19   72.54   74.34   75.54   76.36   76.79   77.09   76.66   77.53
   77.21   77.26   78.97   77.78   77.87   78.05   78.39   78.64   78.87   79.41
   79.23   78.88   79.27   80.11   80.68   80.43   81.62   81.51   81.65   81.59
   81.61   81.58   81.02   81.17   80.84   80.26   80.55   80.11   79.57   79.25
   78.45   78.38   78.18   78.11   78.12    78.6   79.19   80.75   82.28    85.3
   85.83   87.31   87.15   87.34   87.46
                                                                                
                                                                                
                          48.165  48.109  48.076  48.117  48.176  48.179  48.214
  48.214
                                                                                
                                                                                
                                                                                
                                                                                
                                                                                
                                                                                
                                                                                
                                                                                
                                                                                
                                                                                
                                                                                
                                        
       0 6190.38 6208.21 6348.59  6411.8 6513.35  6576.9 6601.42 6673.09  6690.4
 6710.12  6736.8  6753.8 6775.71  6803.3 6831.67 6876.26 7001.14 7180.237240.351
7298.3267358.4477382.0667382.0667432.5267481.911 7532.377581.7567632.215  7681.6
7729.9127729.912 7788.967848.0087905.983 7961.81 7980.26 8002.74 8054.38 8076.52
 8104.94 8122.06 8171.76 8209.17 8230.19 8252.92 8269.82 8293.48 8323.95 8344.63
 8367.44 8387.21 8411.35 8433.23    8457  8483.4 8500.76 8527.92 8544.29 8562.66
 8587.06  8603.2 8628.69 8632.82 8653.36 8671.96 8690.31 8707.33 8728.09 8768.89
 8800.27 8819.08 8837.64 8856.61 8874.15 8895.46 8912.45 8932.59 8952.84 8970.92
 8997.09 9013.91 9034.62 9050.95 9073.62 9099.74  9138.9 9160.43 9177.93 9194.51
 9210.97 9240.41 9264.28 9281.43 9331.98 9351.27  9371.3  9394.1 9414.63 9437.92
 9455.63 9477.88 9501.93 9529.03 9548.29  9569.6 9586.53 9602.95 9626.71 9644.94
 9666.67 9690.53 9741.04 9764.55 9783.07 9800.01 9816.58    9838 9862.47 9883.99
 9901.85 9923.86 9948.65 9975.53 9996.0510021.3810042.9710063.4410091.0710111.84
 10132.710169.5210190.8710220.7510244.4710264.72 10283.210302.2710332.4710354.62
10376.8810396.9910419.42 10453.610474.9910494.4410516.9810543.3810575.1510620.95
10638.0410661.3310696.6210714.79   10736
    47.7   47.77   47.94   48.17   48.32   48.63   48.81   48.87   49.13   49.13
   49.21   49.23   49.41   49.49   49.71   49.77   50.08   50.54  50.657  50.836
  50.983  51.087  51.165  54.165  54.109  54.076  54.117  54.176  54.179  54.214
  54.214  51.214  51.241  51.606  52.701  54.551    54.8   55.92   59.11   59.21
   60.11   60.41   64.13   62.78   63.78   67.48   67.34   66.92   67.62   68.06
   66.57   63.73   63.65   63.69    63.6   66.38   68.64   68.68   69.06   68.97
   68.44   68.09   64.98   64.78   64.56   65.02   64.25   65.33    65.2   64.85
    64.9   64.88   63.19   63.89   64.62   64.96   64.93   67.44   67.69   67.36
   66.78   66.97   67.37   67.22   67.39   67.62   67.58   67.37   66.73   66.27
   66.61   67.75   69.34   68.97   69.22   70.04   70.19   69.95   70.84   71.94
   72.09   72.19   72.54   74.34   75.54   76.36   76.79   77.09   76.66   77.53
   77.21   77.26   78.97   77.78   77.87   78.05   78.39   78.64   78.87   79.41
   79.23   78.88   79.27   80.11   80.68   80.43   81.62   81.51   81.65   81.59
   81.61   81.58   81.02   81.17   80.84   80.26   80.55   80.11   79.57   79.25
   78.45   78.38   78.18   78.11   78.12    78.6   79.19   80.75   82.28    85.3
   85.83   87.31   87.15   87.34   87.46
                                                                                
                                                                                
                          48.165  48.109  48.076  48.117  48.176  48.179  48.214
  48.214
                                                                                
                                                                                
                                                                                
                                                                                
                                                                                
                                                                                
                                                                                
                                                                                
                                                                                
                                                                                
                                                                                
                                        
Pier Skew, UpSta & Num, DnSta & Num=  ,7432.526, 2 ,7432.526, 2 , 0 , 0 , 0 ,,
     2.3     2.3
      15  48.109
     2.3     2.3
      15  48.109
Pier Skew, UpSta & Num, DnSta & Num=  ,7481.911, 2 ,7481.911, 2 , 0 , 0 , 0 ,,
     2.3     2.3
      15  48.076
     2.3     2.3
      15  48.076
Pier Skew, UpSta & Num, DnSta & Num=  ,7532.37, 2 ,7532.37, 2 , 0 , 0 , 0 ,,
     2.3     2.3
      15 48.1174
     2.3     2.3
      15 48.1174
Pier Skew, UpSta & Num, DnSta & Num=  ,7581.756, 2 ,7581.756, 2 , 0 , 0 , 0 ,,
     2.3     2.3
      15 48.1757
     2.3     2.3
      15 48.1757
Pier Skew, UpSta & Num, DnSta & Num=  ,7632.215, 2 ,7632.215, 2 , 0 , 0 , 0 ,,
     2.3     2.3
      15 48.1792
     2.3     2.3
      15  48.109
Pier Skew, UpSta & Num, DnSta & Num=  ,7681.6, 2 ,7681.6, 2 , 0 , 0 , 0 ,,
     2.3     2.3
      15 48.2139
     2.3     2.3
      15 48.2139
Abutment Skew #Up #Dn= , 2 , 3
7382.0667406.866
  46.214  31.627
7382.0667406.866 7414.77
  46.067  31.956   28.23
Abutment Skew #Up #Dn= , 3 , 2
 7675.567709.4427729.912
   15.08  33.733  46.264
7701.3927729.912
  35.543  48.214
BR Coef=-1 , 1 , 0 ,1.25, 0 ,,,0.8,0,2,0,
WSPro=,,,, 1 ,,,, 0 ,,,, 0 ,,,,-1 ,-1 ,-1 , 0 , 0 , 0 , 0 , 0
BC Design=,, 0 ,, 0 ,,,,,,
BC Use User HTab Curves=0
BC User HTab FreeFlow(D)= 0

Type RM Length L Ch R = 1 ,173835  ,415.12,496.63,570.09
BEGIN DESCRIPTION:
Surveyed Section
END DESCRIPTION:
XS GIS Cut Line= 6
2400782.88250732629419.3198852542396975.81231689625600.842895508
2396319.88092041 625183.970886232396232.95031738624296.882873535
2395968.71868896623476.6099243162393797.61309814621738.614074707
#Sta/Elev= 30
       0   52.16  476.19   50.62  971.96   41.02 1859.99    47.1 2442.22   43.88
 2509.76   44.89 4688.16   46.28 4984.22   41.11 5219.01   44.37 5364.73   39.22
 5734.97   45.54 6272.7940.28718 6402.22   33.02 6597.19   35.29 7038.09   29.25
7268.761 33.33367415.637 29.46637464.953 18.10437491.755 18.01817549.648 29.4587
7762.994 39.8535 7798.37   49.21 8324.54   68.63 8392.76   64.35 8513.39   69.57
    8596   66.57 9254.51   67.34 9905.89   79.6210459.77   77.7410720.88   87.75
#Mann= 8 ,-1 , 0
       0    .045       0 2442.22     .04       0 2509.76    .045       0
 6272.79      .1       07415.637     .05       07549.648     .09       0
 7798.37    .045       0    8596    .065       0
#XS Ineff= 3 ,-1
                               0 7332.07   48.21 7779.9110720.88   48.21
Permanent Ineff=
       F       F       F
#Block Obstruct= 13 ,-1
 7881.59 7931.17  64.147 8089.17 8227.37  75.008 8554.12 8556.22  79.267
 8695.88 8711.39  78.238 8716.16 8738.11  77.946 9024.26 9036.54  79.148
 9816.87 9841.67  88.14710259.2410287.88  88.91610370.8710408.13  88.539
10532.39   10584  91.65710604.6710636.42  94.00210642.2310661.26  94.959
10693.3610720.88  97.753
Bank Sta=7415.637,7549.648
XS Rating Curve= 0 ,0
Exp/Cntr=0.5,0.3

Type RM Length L Ch R = 1 ,173339  ,1595.19,1648.85,1325.31
XS GIS Cut Line= 5
2400955.22271729629197.0986938482396945.37072754625293.972473145
2396598.92767334624290.1992797852396700.23413086 623026.28112793
2396432.76367188620856.680114746
#Sta/Elev= 30
       0   50.83  339.12    54.4  527.83    49.3  890.53   40.63 1375.34   46.29
 2372.21   43.28    2444   43.05 5126.04   44.76 5216.71   43.84 5251.0136.55342
 5390.55   39.54 5666.43   44.88 5807.1539.31676 5889.04   33.61  6470.8   34.32
 6547.41   26.88 6891.12   30.38 6966.96   26.34  6968.2   18.84 6979.73    18.6
 6996.84   26.82 7041.81   36.62 7545.32    34.3 7621.19   43.64 7721.82   46.98
 7879.29   65.36 8001.39   60.55 8063.26   65.92 9075.93   75.04 10111.7   73.38
#Mann= 11 ,-1 , 0
       0    .045       0  527.83    .045       0 2372.21     .04       0
    2444    .045       0 5251.01    .032       0 5390.55    .045       0
 5807.15      .1       0 6891.12     .05       0 6996.84     .09       0
 7621.19    .045       0 8001.39    .065       0
#XS Ineff= 2 , 0
       0  5674.5      52               0
Permanent Ineff=
       F       F
#Block Obstruct= 17 ,-1
   27.52   43.05  62.016   65.44   88.23   61.76  111.35  134.39  61.963
  153.17  189.89  62.059  213.01  248.12  62.462  274.28  320.04  62.742
  373.98  407.62   62.88 7895.82 7903.81  75.277 8072.58 8137.85  75.994
 8632.74 8681.41   79.46 8850.32 8896.55  80.391 8992.75 8997.06   82.45
 9147.68 9171.64   84.77 9307.63 9323.73  85.561 9409.01 9428.91  85.818
 9551.73 9575.46  87.181 9608.77 9613.18  87.438
Bank Sta=6891.12,6996.84
XS Rating Curve= 0 ,0
Exp/Cntr=0.3,0.1

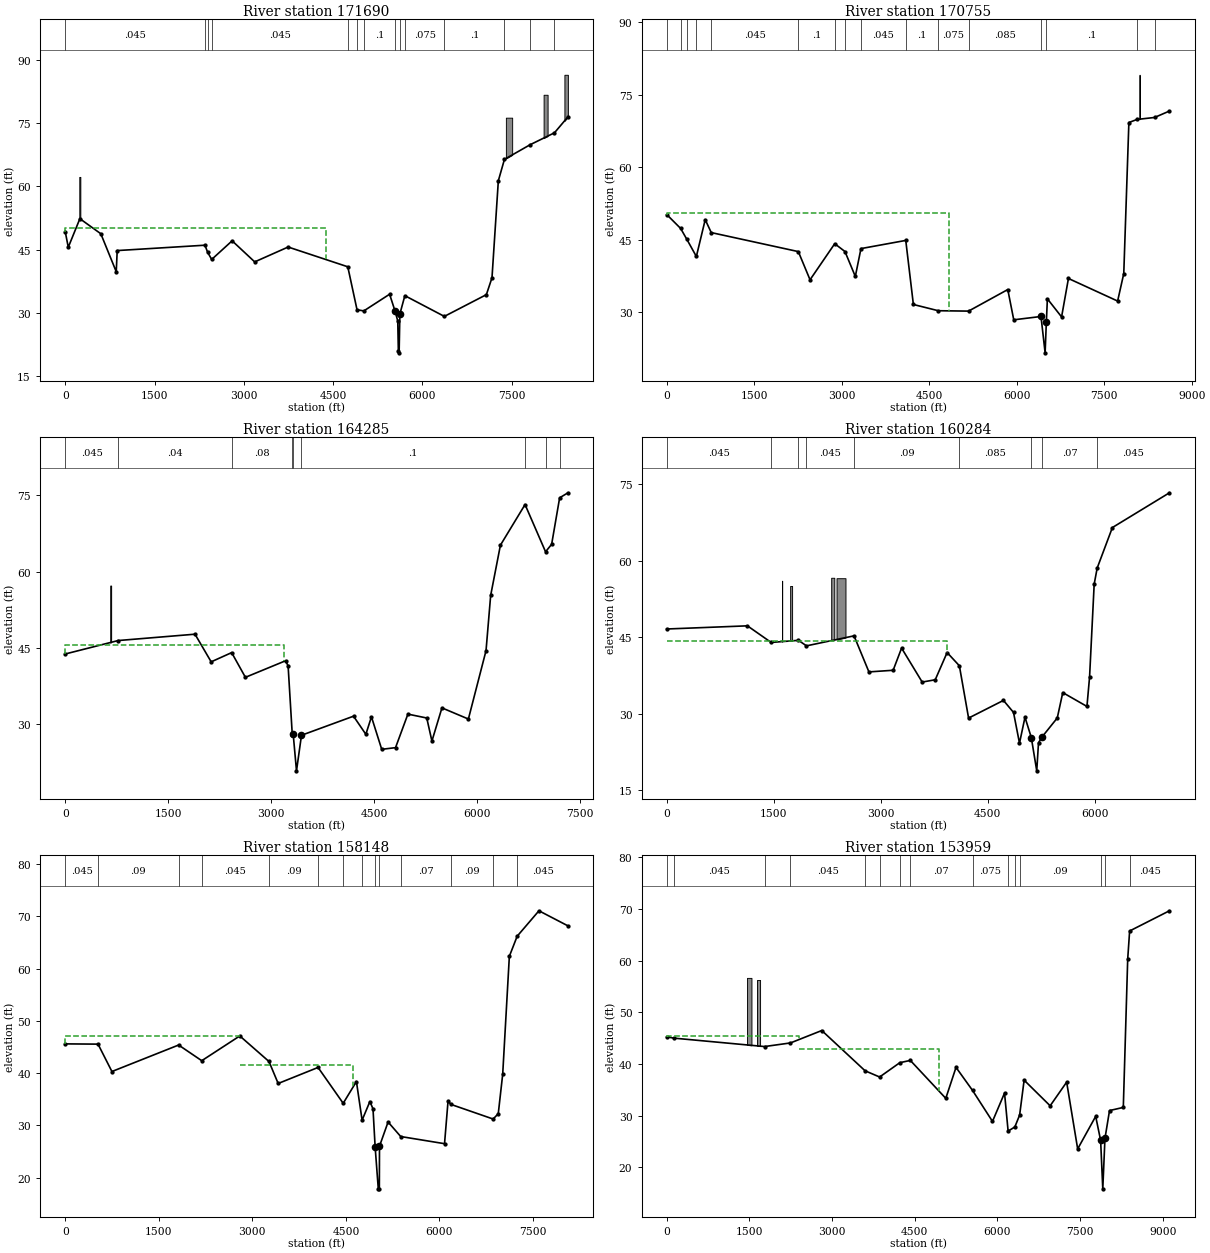
Type RM Length L Ch R = 1 ,171690  ,1031.04,934.47,615.78
XS GIS Cut Line= 3
2401052.47930908629124.1412963872398491.05291748625282.001708984
2397336.12390137 621634.25592041
#Sta/Elev= 30
       0   49.23      51   45.54   245.8   52.31  597.68   48.74  856.64   39.75
  872.79   44.76 2346.56   46.03 2392.16   44.33 2459.71   42.66  2802.9   47.07
 3182.16   42.08  3743.6    45.6 4745.47   40.92 4900.8430.73897 5014.83   30.47
 5447.95   34.42 5536.66   30.54 5584.85   28.09 5594.95   20.91 5607.59   20.54
 5620.35   29.73 5703.85   34.08 6367.54   29.17 7073.15   34.32 7167.53   38.32
 7274.05   61.29 7376.59   66.36 7807.23   69.82 8216.75   72.65  8443.9   76.44
#Mann= 14 ,-1 , 0
       0    .045       0 2346.56     .04       0 2392.16      .1       0
 2459.71    .045       0 4745.47      .1       0 4900.84    .075       0
 5014.83      .1       0 5536.66     .05       0 5620.35     .09       0
 5703.85    .075       0 6367.54      .1       0 7376.59    .065       0
 7807.23    .045       0 8216.75    .065       0
#XS Ineff= 2 , 0
       0 4375.36      50               0
Permanent Ineff=
       F       F
#Block Obstruct= 4 ,-1
  235.91  253.71  62.203 7400.75 7506.35  76.234 8034.38 8101.51  81.659
 8383.79 8442.09  86.391
Bank Sta=5536.66,5620.35
XS Rating Curve= 0 ,0
Exp/Cntr=0.3,0.1

Type RM Length L Ch R = 1 ,170755  ,3149.48,6470.02,2683.32
XS GIS Cut Line= 3
2402427.30291748629082.6519165042398458.86090088623218.176513672
2397753.35992432621851.268676758
#Sta/Elev= 30
       0   50.25  238.75   47.37  345.63   45.11  508.54   41.57   660.4   49.19
  763.66   46.51 2256.52   42.58 2457.45   36.75 2880.55   44.21 3056.38   42.59
  3233.7   37.44 3330.47    43.2 4098.45   44.89 4229.16   31.64 4656.11   30.35
 5174.99   30.27 5847.59   34.73  5949.9   28.47 6417.02   29.16  6487.7   21.64
 6508.71   27.99 6526.75   32.81 6769.96   29.07 6887.48   37.02 7730.81   32.35
 7836.12   38.04 7923.71   69.27 8062.44   69.91 8364.11   70.32 8619.24   71.65
#Mann= 16 ,-1 , 0
       0    .045       0  238.75      .1       0  345.63    .045       0
  508.54     .05       0  763.66    .045       0 2256.52      .1       0
 2880.55    .045       0 3056.38      .1       0 3330.47    .045       0
 4098.45      .1       0 4656.11    .075       0 5174.99    .085       0
 6417.02     .05       0 6508.71      .1       0 8062.44    .065       0
 8364.11    .045       0
#XS Ineff= 2 , 0
         4837.25    50.5
Permanent Ineff=
       F       F
#Block Obstruct= 1 ,-1
 8105.53 8108.96  79.149
Bank Sta=6417.02,6508.71
XS Rating Curve= 0 ,0
Exp/Cntr=0.3,0.1

Type RM Length L Ch R = 1 ,164285  ,2864.2,4000.99,2578.86
XS GIS Cut Line= 5
2403711.10272217626158.3626708982402175.96209717623534.044128418
2401935.82849121622899.404907227 2400940.9887085622530.628112793
2399817.50592041620249.357727051
#Sta/Elev= 30
       0   43.75  771.82    46.4 1889.95   47.65 2125.53    42.2 2423.85   44.02
 2624.26   39.15 3208.66   42.41 3246.13   41.42 3306.98   27.82 3320.13   27.98
 3368.38   20.72 3440.99   27.73 4199.02   31.49 4378.68   27.92  4460.1   31.37
  4609.7   24.96 4810.88   25.29 4991.14    31.9 5265.76   31.13 5340.86   26.59
 5486.85   33.13 5872.04   30.93 6129.03   44.41 6196.58   55.29 6338.53   65.19
 6697.4473.19972 6996.21   63.89 7084.76   65.37 7201.24   74.53  7322.8   75.52
#Mann= 9 ,-1 , 0
       0    .045       0  771.82     .04       0 2423.85     .08       0
 3306.98    .085       0 3320.13     .05       0 3440.99      .1       0
 6697.44    .045       0 6996.21      .1       0 7201.24    .045       0
#XS Ineff= 2 , 0
         3189.87   45.48
Permanent Ineff=
       F       F
#Block Obstruct= 1 ,-1
  654.66  668.77  57.239
Bank Sta=3320.13,3440.99
XS Rating Curve= 0 ,0
Exp/Cntr=0.3,0.1

Type RM Length L Ch R = 1 ,160284  ,1773.72,2136.45,728.24
XS GIS Cut Line= 4
2405626.23590088625430.1008911132402841.20928955621117.873291016
2402609.11572266620634.0322875982401575.70428467619725.540893555
#Sta/Elev= 30
       0   46.61 1131.11   47.23 1463.45   43.98 1846.75   44.39 1958.78   43.31
 2625.33   45.27 2833.96   38.21 3173.38   38.53 3291.77   42.87 3580.32   36.22
 3763.29   36.67 3929.68      42 4101.47   39.41 4230.57   29.17 4719.16   32.63
 4860.26   30.28 4943.98   24.26 5021.07   29.34 5109.52   25.36 5185.85   18.84
 5210.42   24.32 5256.31   25.41 5473.43   29.19 5550.43   34.16 5889.28   31.45
 5926.16   37.22 5990.75    55.4 6032.77   58.54 6245.64   66.47  7045.5   73.28
#Mann= 9 ,-1 , 0
       0    .045       0 1463.45    .055       0 1846.75     .09       0
 1958.78    .045       0 2625.33     .09       0 4101.47    .085       0
 5109.52     .05       0 5256.31     .07       0 6032.77    .045       0
#XS Ineff= 2 , 0
         3927.67   44.18
Permanent Ineff=
       F       F
#Block Obstruct= 4 ,-1
 1615.22 1618.71  56.052  1729.9 1757.31  55.037 2305.12 2348.74  56.642
 2379.95 2505.56  56.555
Bank Sta=5109.52,5256.31
XS Rating Curve= 0 ,0
Exp/Cntr=0.3,0.1

Type RM Length L Ch R = 1 ,158148  ,3132.02,4188.71,1829.03
XS GIS Cut Line= 6
2406829.02947998625551.358093262 2404683.3505249 621320.50970459
 2404374.6071167620852.5706787112403535.21112061620543.827270508
2403303.65368652620485.9379272462402303.27508545619207.011291504
#Sta/Elev= 30
       0   45.58  525.59 45.5309  748.36   40.29  1817.8   45.36 2188.62   42.36
  2798.7    47.1  3266.4   42.21 3413.79      38 4053.18   41.07 4456.24   34.21
 4668.32   38.37 4759.34   30.98 4884.28   34.55  4934.2   33.15 4968.13    25.9
 5018.95   17.84 5035.82   17.85 5038.26      26 5175.86   30.63 5378.44   27.85
 6080.94   26.48  6137.7    34.7 6180.53   34.01 6860.09    31.2  6942.4   32.22
 7013.52   39.77 7120.15   62.34 7245.42   66.18 7594.71   71.05  8060.2   68.16
#Mann= 14 ,-1 , 0
       0    .045       0  525.59     .09       0  1817.8    .065       0
 2188.62    .045       0  3266.4     .09       0 4053.18     .07       0
 4456.24     .09       0 4759.34    .085       0 4968.13     .05       0
 5038.26     .09       0 5378.44     .07       0 6180.53     .09       0
 6860.09     .07       0 7245.42    .045       0
#XS Ineff= 2 ,-1
       0  2798.7   47.11  2798.7 4620.25    41.5
Permanent Ineff=
       F       F
Bank Sta=4968.13,5038.26
XS Rating Curve= 0 ,0
Exp/Cntr=0.3,0.1

Type RM Length L Ch R = 1 ,153959  ,4097.99,5169.08,4180.57
XS GIS Cut Line= 4
2407912.32470703625218.4014892582405356.40393066620979.426879883
2404052.82092285619252.7510986332402509.10388184617972.037902832
#Sta/Elev= 30
       0   45.27  128.58   45.02 1775.51   43.39 2245.15   44.09 2812.99   46.49
 3598.45    38.7 3861.99    37.5 4228.5940.26891 4419.18   40.71 5062.35   33.37
 5247.87   39.36 5547.23   34.91 5909.28   28.91 6127.93   34.39 6192.87   27.04
 6315.07   27.84  6401.7   30.14 6483.22   36.89 6955.33   31.93 7254.74   36.51
 7454.46   23.59 7781.28   29.89 7870.72   25.26 7910.02   15.87 7949.43   25.61
 8032.25   31.01 8282.28   31.62    8362   60.29 8396.99   65.74 9119.23   69.65
#Mann= 15 ,-1 , 0
       0     .07       0  128.58    .045       0 1775.51     .09       0
 2245.15    .045       0 3598.45     .07       0 3861.99    .045       0
 4228.59     .08       0 4419.18     .07       0 5547.23    .075       0
 6192.87    .032       0 6315.07     .08       0  6401.7     .09       0
 7870.72     .05       0 7949.43     .09       0 8396.99    .045       0
#XS Ineff= 2 ,-1
       0  2404.9   45.48  2404.9 4936.71  42.906
Permanent Ineff=
       F       F
#Block Obstruct= 2 ,-1
 1456.37 1537.37  56.669 1638.23 1693.65  56.268
Bank Sta=7870.72,7949.43
XS Rating Curve= 0 ,0
Exp/Cntr=0.3,0.1

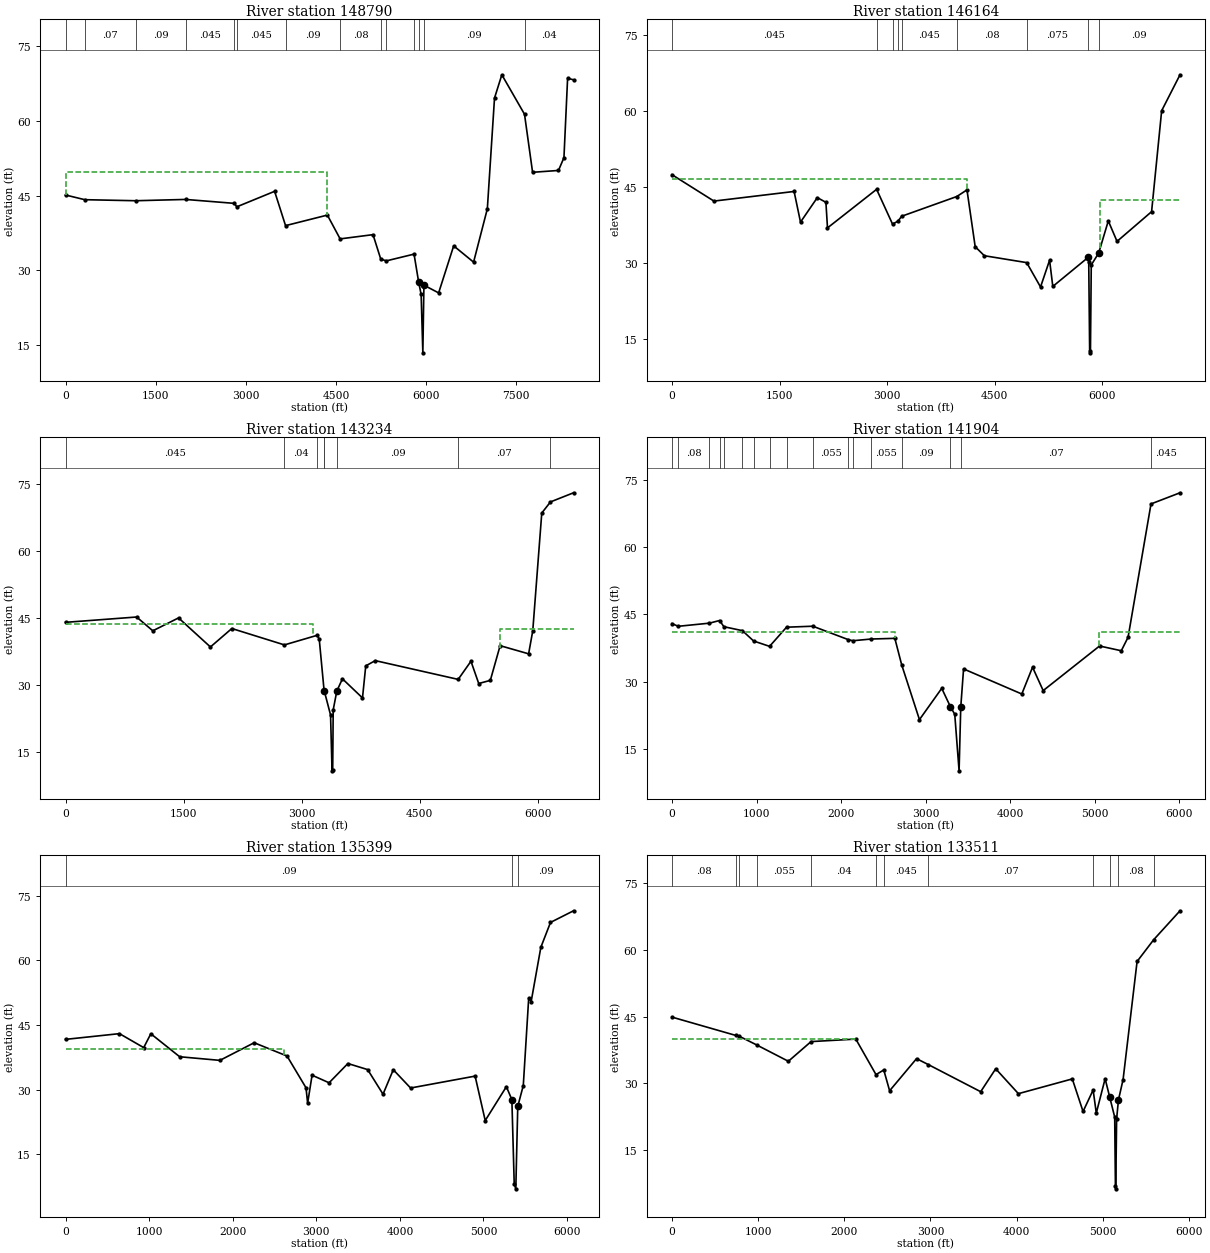
Type RM Length L Ch R = 1 ,148790  ,2758.52,2626.27,1944.23
XS GIS Cut Line= 5
2408396.10308838624836.5236816412405522.96868896620011.826293945
 2405495.8637085619225.7800903322405577.17871094 618168.68347168
2406146.38470459617355.532287598
#Sta/Elev= 30
       0   45.14  321.28    44.2 1166.75   43.99 1997.85   44.25 2812.04   43.46
 2849.24   42.76 3479.52   45.88 3661.73   38.99 4357.57   41.11 4569.77   36.33
 5117.19   37.18 5246.15   32.26 5339.99   31.92 5799.93   33.27 5876.87   27.63
  5917.9   25.17  5946.2   13.45 5964.19   27.03 6208.93   25.49  6459.4   34.93
 6790.49   31.66  7019.5   42.37 7138.82    64.6  7260.7   69.28 7637.98   61.36
  7772.4    49.7 8203.28   50.07 8294.22   52.64 8355.09   68.58    8454   68.27
#Mann= 14 ,-1 , 0
       0    .045       0  321.28     .07       0 1166.75     .09       0
 1997.85    .045       0 2812.04     .04       0 2849.24    .045       0
 3661.73     .09       0 4569.77     .08       0 5246.15     .09       0
 5339.99     .08       0 5799.93     .09       0 5876.87     .05       0
 5964.19     .09       0 7637.98     .04       0
#XS Ineff= 2 , 0
         4358.05   49.73
Permanent Ineff=
       F       F
Bank Sta=5876.87,5964.19
XS Rating Curve= 0 ,0
Exp/Cntr=0.3,0.1

Type RM Length L Ch R = 1 ,146164  ,2910.25,2930.2,2253.94
XS GIS Cut Line= 4
2409993.03027344 623873.720886232408012.25012207 620000.00012207
2407483.75012207     618969.18752406878.59088135617512.451477051
#Sta/Elev= 30
       0   47.36  585.35   42.15 1703.53   44.05 1792.93      38 2027.16   42.83
 2147.25   41.91 2169.35   36.86 2854.48   44.47 3076.29   37.62  3150.7   38.17
 3204.56   39.16 3972.75   43.05 4115.01   44.36 4229.56   33.15 4357.36   31.37
 4947.87   30.01    5141    25.2 5267.27   30.48 5312.12   25.31 5804.16   31.03
 5813.38   30.09 5826.08   12.64 5837.08   12.21 5848.65   29.55 5952.04   31.89
 6086.26   38.24 6208.25    34.2 6690.05   40.06 6830.51   59.98  7086.6   67.07
#Mann= 9 ,-1 , 0
       0    .045       0 2854.48     .07       0 3076.29    .045       0
  3150.7     .09       0 3204.56    .045       0 3972.75     .08       0
 4947.87    .075       0 5804.16     .05       0 5952.04     .09       0
#XS Ineff= 2 , 0
          4108.5   46.52 5974.68           42.31
Permanent Ineff=
       F       F
Bank Sta=5804.16,5952.04
XS Rating Curve= 0 ,0
Exp/Cntr=0.3,0.1

Type RM Length L Ch R = 1 ,143234  ,1585.28,1329.15,909.28
XS GIS Cut Line= 4
2411333.28509521622496.2366943362409976.92352295619706.351928711
2409641.49871826618745.8170776372408772.44329834616580.801879883
#Sta/Elev= 30
       0      44  903.17   45.19 1108.87   42.11 1435.66   44.99 1840.51    38.5
 2112.45   42.62 2780.37   38.96  3197.2   41.11 3222.78   40.21 3283.66   28.87
 3286.24    28.7 3366.25   23.32 3385.34   10.84 3393.45   11.03 3399.93   24.45
 3445.72   28.65 3517.15   31.39 3771.87   27.12 3813.34   34.28 3934.18   35.45
 4987.11   31.26 5149.52   35.31 5248.17   30.34 5395.44   31.04 5519.87   38.79
  5881.8   36.97 5934.41    42.1  6048.9   68.41 6159.52   70.89 6452.46   72.93
#Mann= 8 ,-1 , 0
       0    .045       0 2780.37     .04       0  3197.2     .08       0
 3283.66    .075       0 3286.24     .05       0 3445.72     .09       0
 4987.11     .07       0 6159.52    .045       0
#XS Ineff= 2 , 0
         3145.57   43.71 5512.66           42.54
Permanent Ineff=
       F       F
Bank Sta=3286.24,3445.72
XS Rating Curve= 0 ,0
Exp/Cntr=0.3,0.1

Type RM Length L Ch R = 1 ,141904  ,6005.69,6505.05,2900.89
XS GIS Cut Line= 4
2412636.31072998621193.2113037112411770.00012207 620000.00012207
 2410435.6505127618194.4210815432408845.76348877616546.120910645
#Sta/Elev= 30
       0   42.96   73.92   42.36  443.52   43.06  563.12   43.65   614.2   42.27
  832.96   41.39  965.77   39.09 1154.48    37.9 1355.21   42.16 1665.91   42.38
 2084.79    39.4 2140.08   39.15 2356.43   39.53 2636.28   39.68 2717.62   33.77
 2927.49    21.6 3191.16   28.56 3294.42   24.44 3345.04   22.79 3396.33   10.21
 3416.07   24.37 3449.39   32.88 4138.31    27.3 4265.34   33.26 4391.17   28.06
  5058.1   37.98 5315.23   36.92  5395.5   39.93 5666.62   69.58 6009.78   72.06
#Mann= 17 ,-1 , 0
       0    .045       0   73.92     .08       0  443.52     .06       0
  563.12     .04       0   614.2     .09       0  832.96    .055       0
  965.77    .045       0 1154.48    .055       0 1355.21     .09       0
 1665.91    .055       0 2084.79     .04       0 2140.08     .04       0
 2356.43    .055       0 2717.62     .09       0 3294.42     .05       0
 3416.07     .07       0 5666.62    .045       0
#XS Ineff= 2 , 0
       0 2636.28   41.14 5050.63       0   41.14
Permanent Ineff=
       F       F
Bank Sta=3294.42,3416.07
XS Rating Curve= 0 ,0
Exp/Cntr=0.3,0.1

Type RM Length L Ch R = 1 ,135399  ,1799.78,1888.31,1968.81
XS GIS Cut Line= 3
2413362.78710938620763.9796752932411672.18792725617021.867126465
2410760.40411377615274.281677246
#Sta/Elev= 30
       0   41.68  645.44   43.01   935.5   39.77 1020.63   42.98 1365.65   37.65
 1846.76   36.81 2256.83    40.9 2649.93   37.82 2877.03   30.45 2896.48   26.88
 2949.53   33.37 3153.01   31.61 3378.14   36.08  3614.3   34.67  3798.3   28.96
 3921.01   34.64 4127.94    30.4 4899.91   33.16 5020.78   22.85 5273.91   30.71
 5339.62    27.7 5367.69    8.18 5386.61    7.01 5410.12   26.13 5476.19   30.97
 5541.04   51.28 5570.27   50.44 5686.17   63.03  5801.7   68.81 6077.42   71.51
#Mann= 3 , 0 , 0
       0     .09       0 5339.62     .05       0 5410.12     .09       0
#XS Ineff= 2 , 0
       0 2617.92    39.5               0
Permanent Ineff=
       F       F
Bank Sta=5339.62,5410.12
XS Rating Curve= 0 ,0
Exp/Cntr=0.3,0.1

Type RM Length L Ch R = 1 ,133511  ,1601.81,1597.26,1329.84
XS GIS Cut Line= 4
2414206.06451416620200.1687011722413230.28289795618019.906677246
2412879.61151123616114.083496094 2412864.3649292614543.685119629
#Sta/Elev= 30
       0   44.92   738.3   40.81  782.53    40.6  984.79   38.64 1350.98   34.98
 1614.58   39.41  2133.9   39.97 2368.21   31.98 2458.44   33.02 2526.21   28.34
 2838.81   35.57 2973.83   34.25 3583.25   28.13 3757.58   33.29 4021.11   27.69
 4646.61   31.01 4771.52   23.68 4888.57   28.51 4925.12   23.32 5027.61   31.05
 5080.81   26.93 5138.84   22.41 5147.26    6.83 5150.98    6.27 5161.03   21.96
 5182.37   26.28 5236.22   30.87 5398.68   57.44 5591.49   62.34 5896.95   68.85
#Mann= 12 ,-1 , 0
       0     .08       0   738.3     .04       0  782.53     .08       0
  984.79    .055       0 1614.58     .04       0 2368.21    .032       0
 2458.44    .045       0 2973.83     .07       0 4888.57      .1       0
 5080.81     .05       0 5182.37     .08       0 5591.49    .045       0
#XS Ineff= 2 , 0
       0  2133.9   39.98               0
Permanent Ineff=
       F       F
Bank Sta=5080.81,5182.37
XS Rating Curve= 0 ,0
Exp/Cntr=0.3,0.1