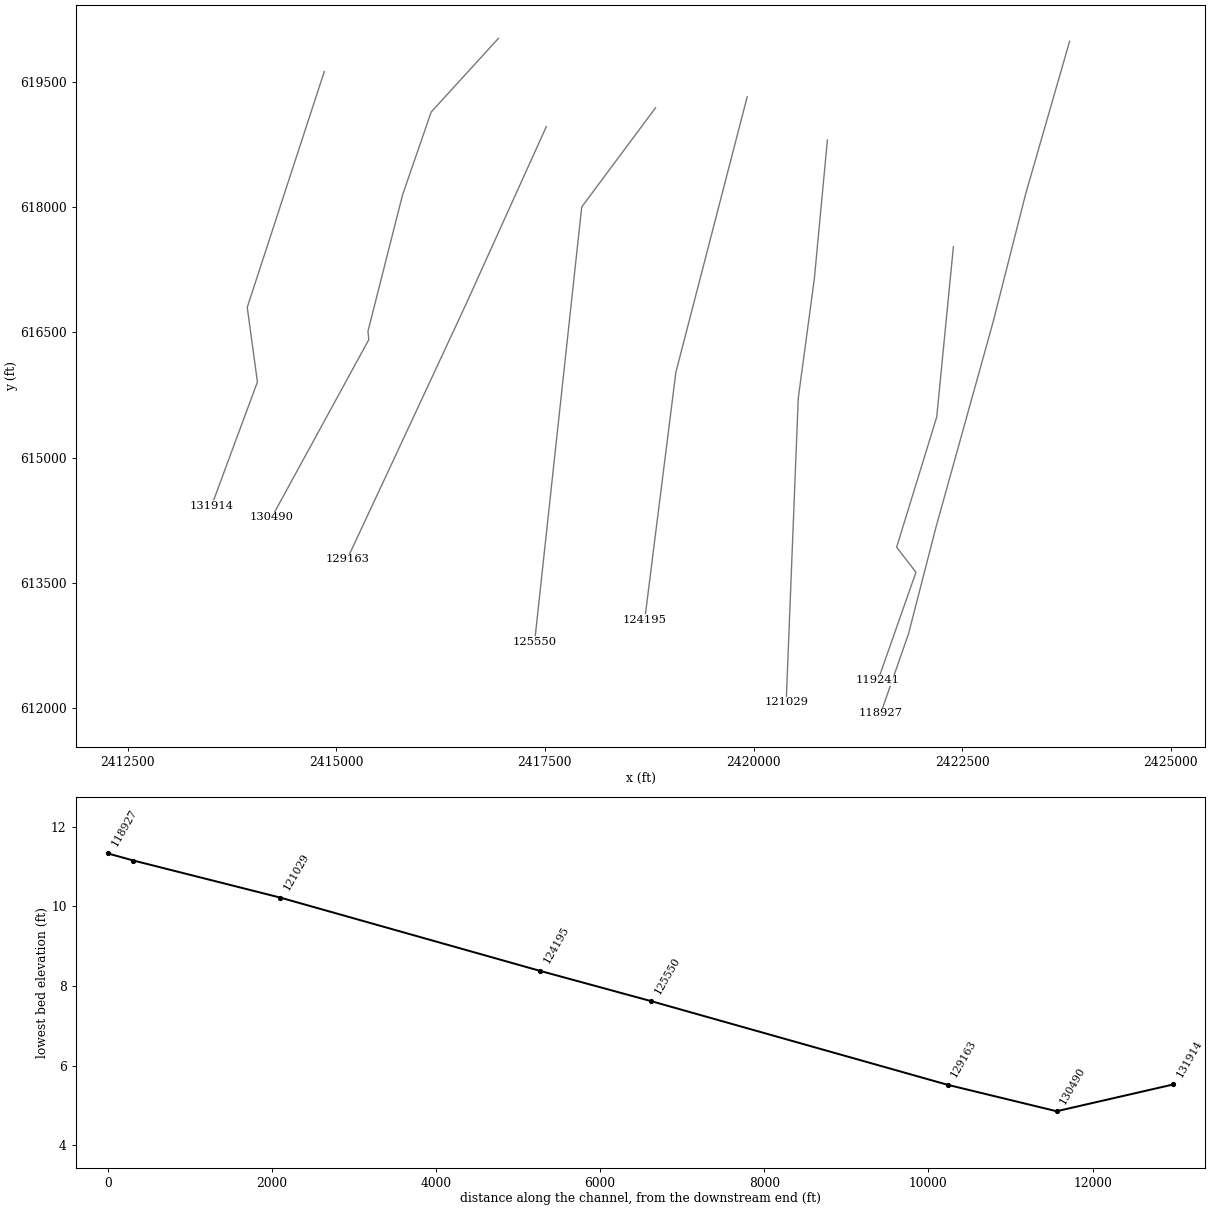
HEC-RAS study DTL_ContentneaCrk.prj: DTL_Contentnea_Crk

--- DTL_ContentneaCrk.g01 (geometry) --- (continued)

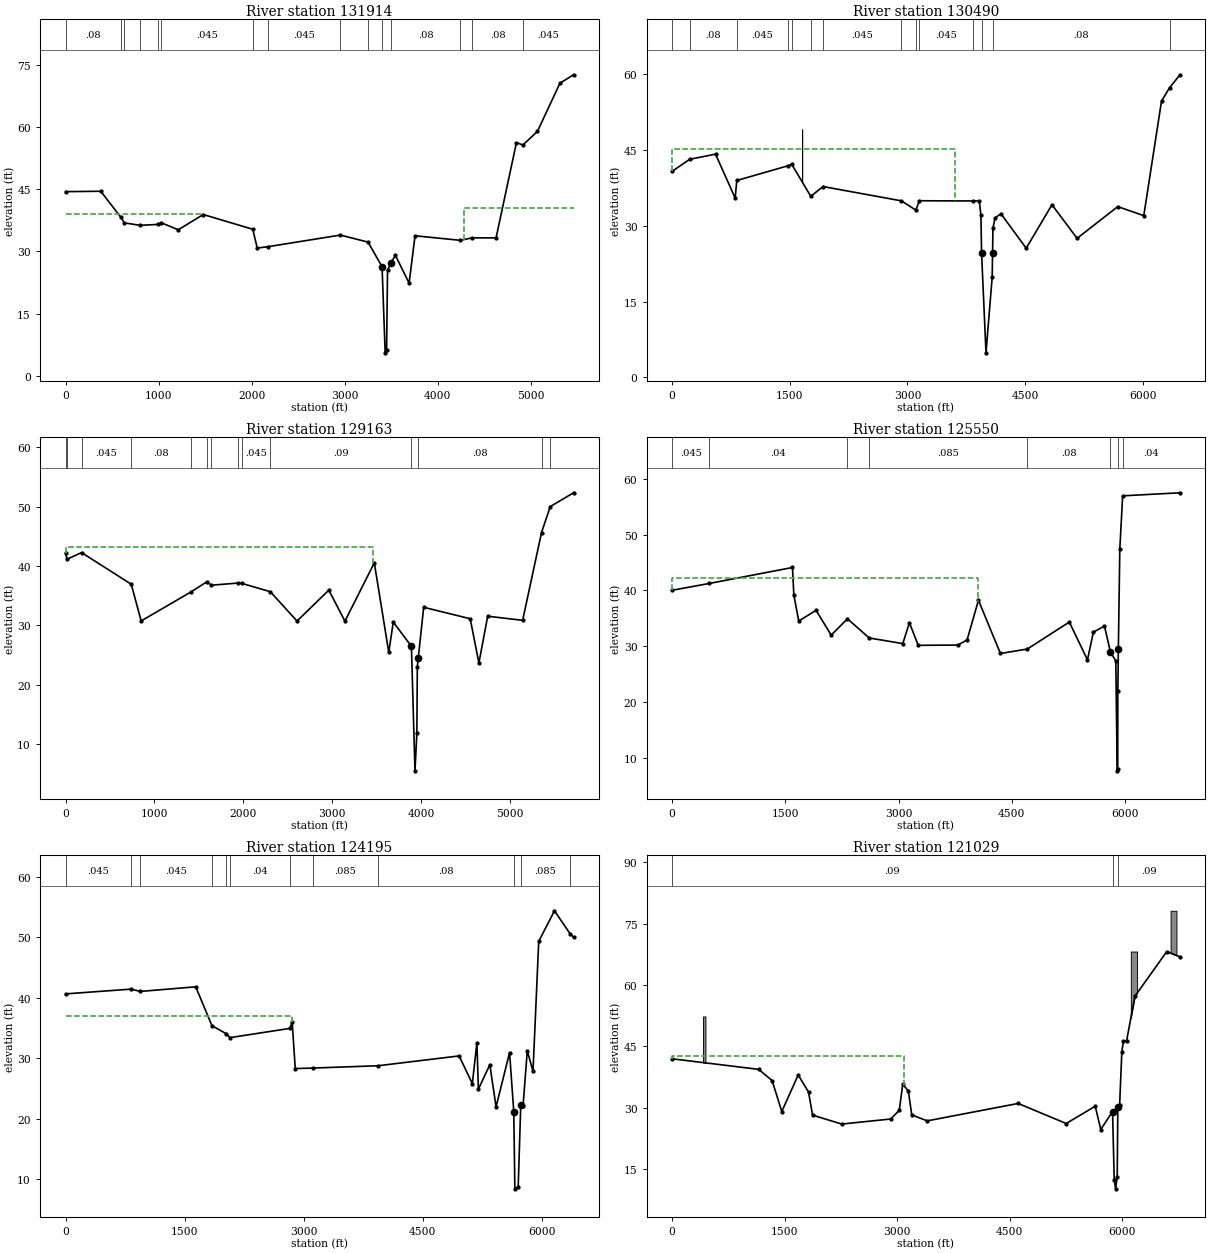
Type RM Length L Ch R = 1 ,131914  ,1451.04,1423.95,1070.28
XS GIS Cut Line= 4
2414857.65887451619629.5806884772413934.31152344616800.865905762
2414056.28430176615906.3994750982413507.40710449614422.398498535
#Sta/Elev= 30
       0   44.39  378.44   44.48  591.93    38.3  632.88   36.86  800.52   36.27
  989.46   36.48 1028.23   36.89 1211.76    35.2 1480.92   38.87 2012.78   35.32
 2060.92   30.79 2177.14   31.12 2954.73   33.92 3251.79   32.22 3402.52   26.29
 3435.81    5.53  3451.1    6.14 3461.27   25.41  3495.3    27.1 3545.55   29.04
 3693.26   22.34 3756.67   33.75 4244.52   32.65 4370.66   33.25 4627.84   33.24
 4846.63   56.19 4916.72   55.65 5072.69   58.92 5314.31   70.53  5460.6   72.56
#Mann= 15 ,-1 , 0
       0     .08       0  591.93     .04       0  632.88     .08       0
  800.52    .055       0  989.46     .04       0 1028.23    .045       0
 2012.78    .075       0 2177.14    .045       0 2954.73     .08       0
 3251.79      .1       0 3402.52     .05       0  3495.3     .08       0
 4244.52     .04       0 4370.66     .08       0 4916.72    .045       0
#XS Ineff= 2 , 0
       0 1480.92   38.88 4280.29       0    40.4
Permanent Ineff=
       F       F
Bank Sta=3402.52,3495.3
XS Rating Curve= 0 ,0
Exp/Cntr=0.3,0.1

Type RM Length L Ch R = 1 ,130490  ,1140.15,1327.06,995.57
BEGIN DESCRIPTION:
Surveyed Section
END DESCRIPTION:
XS GIS Cut Line= 6
2416944.14031982620027.0972900392416137.97711182 619143.74810791
2415794.92889404618148.9083251952415380.74890137616515.158691406
 2415390.4755249616413.6923217772414229.03210449614284.851928711
#Sta/Elev= 30
       0   40.78  225.22   43.19  555.03   44.21  805.02   35.51  825.8238.99312
 1476.25    41.9 1525.44    42.2 1768.14   35.86 1924.7637.79267 2922.7334.95943
 3106.53   33.13 3151.84 34.97913829.451 34.9399 3914.88 34.93423935.591 32.0959
3944.004 24.6369 4000.31  4.85694079.268 19.85224083.798 24.64854088.976 29.5525
4115.511 31.60664191.233 32.3832 4512.51   25.58 4840.87   34.19 5160.94   27.53
 5678.83   33.82 6010.38   32.03 6236.48   54.73 6339.92   57.39 6471.95   59.93
#Mann= 14 ,-1 , 0
       0    .045       0  225.22     .08       0  825.82    .045       0
 1476.25     .04       0 1525.44    .055       0 1768.14     .08       0
 1924.76    .045       0 2922.73     .09       0 3106.53     .04       0
 3151.84    .045       03829.451     .09       03944.004     .05       0
4083.798     .08       0 6339.92    .045       0
#XS Ineff= 2 , 0
       0 3607.59   45.15               0
Permanent Ineff=
       F       F
#Block Obstruct= 1 ,-1
 1656.04 1659.68  49.147
Bank Sta=3944.004,4083.798
XS Rating Curve= 0 ,0
Exp/Cntr=0.3,0.1

Type RM Length L Ch R = 1 ,129163  ,2648.43,3612.55,3086.86
XS GIS Cut Line= 4
 2417517.8994751618969.3096923832416549.45227051616826.434082031
2415686.25830078614969.975891113 2415130.6005249613780.219299316
#Sta/Elev= 30
       0   42.15   17.14   41.15   180.5   42.27  739.13   36.94  850.54   30.76
 1410.29   35.64 1589.08   37.35 1641.06   36.78 1939.2237.13833 1979.21    37.1
 2303.08   35.68 2602.92   30.74 2960.54   35.95  3141.6   30.72 3471.98   40.54
 3634.53   25.47 3685.19   30.57  3889.3   26.49 3929.02    5.52 3950.31   11.84
 3955.63   23.08 3966.41   24.57    4027   33.06 4550.07   31.13 4647.81   23.68
 4746.59   31.56 5139.56   30.86 5352.14   45.65 5449.81   50.01    5712   52.34
#Mann= 14 ,-1 , 0
       0     .04       0   17.14     .05       0   180.5    .045       0
  739.13     .08       0 1410.29    .045       0 1589.08     .09       0
 1641.06     .04       0 1939.22     .04       0 1979.21    .045       0
 2303.08     .09       0  3889.3     .05       0 3966.41     .08       0
 5352.14     .09       0 5449.81     .04       0
#XS Ineff= 2 , 0
         3461.54   43.14
Permanent Ineff=
       F       F
Bank Sta=3889.3,3966.41
XS Rating Curve= 0 ,0
Exp/Cntr=0.3,0.1

Type RM Length L Ch R = 1 ,125550  ,1310.66,1354.76,1326.38
XS GIS Cut Line= 3
2418825.78009033619193.8939208982417941.47808838 618004.66027832
2417377.35430908612790.327880859
#Sta/Elev= 30
       0      40  491.05   41.22 1595.58   44.09 1613.61   39.16 1678.36   34.49
 1907.73   36.41 2108.15   31.96 2323.41   34.89 2611.32   31.45 3056.03   30.44
 3144.05   34.18  3260.2   30.13 3786.26   30.18 3907.62   31.11 4058.12   38.22
 4348.57   28.67 4704.01   29.46 5260.86    34.3 5501.24   27.53 5579.75    32.5
 5726.52   33.59 5805.85    28.9 5876.48   27.35 5894.94    7.62 5901.89    7.99
 5903.32   21.85 5910.32   29.39 5929.52   47.36 5967.29   56.94 6726.74   57.49
#Mann= 8 ,-1 , 0
       0    .045       0  491.05     .04       0 2323.41     .05       0
 2611.32    .085       0 4704.01     .08       0 5805.85     .05       0
 5910.32     .09       0 5967.29     .04       0
#XS Ineff= 2 , 0
       0 4049.64   42.14               0
Permanent Ineff=
       F       F
Bank Sta=5805.85,5910.32
XS Rating Curve= 0 ,0
Exp/Cntr=0.3,0.1

Type RM Length L Ch R = 1 ,124195  ,2088.77,3166.51,2036.82
XS GIS Cut Line= 3
2419923.85968018619325.0675048832419069.72528076616022.604125977
2418696.40808105613055.049682617
#Sta/Elev= 30
       0   40.63  827.79   41.42  942.39   41.04  1640.9    41.8 1845.08   35.38
 2025.62   34.04 2071.71   33.39 2826.52   34.92 2856.45   35.94 2895.18   28.28
 3113.33   28.36 3935.99   28.74 4960.11   30.37  5126.5   25.78 5184.26   32.57
    5203   24.86 5347.06   28.92 5425.72   21.94 5595.83   30.93 5648.73   21.17
 5662.63    8.38 5704.52    8.67  5736.9   22.26 5765.53   22.07 5819.05   31.22
 5891.14   27.82 5963.39   49.33 6161.99   54.38 6357.26    50.6 6402.07      50
#Mann= 12 ,-1 , 0
       0    .045       0  827.79    .055       0  942.39    .045       0
 1845.08     .09       0 2025.62    .075       0 2071.71     .04       0
 2826.52    .032       0 3113.33    .085       0 3935.99     .08       0
 5648.73     .05       0  5736.9    .085       0 6357.26    .065       0
#XS Ineff= 2 , 0
       0  2848.1      37               0
Permanent Ineff=
       F       F
Bank Sta=5648.73,5736.9
XS Rating Curve= 0 ,0
Exp/Cntr=0.3,0.1

Type RM Length L Ch R = 1 ,121029  ,1505.39,1788.32,1554.23
XS GIS Cut Line= 4
2420885.00311279618807.4437255862420728.28387451617141.972717285
 2420535.9598999615713.2808837892420391.12030029612064.042907715
#Sta/Elev= 30
       0   41.98 1154.16    39.4 1333.74   36.66 1462.48    29.1  1681.2   38.02
 1818.65   33.86  1872.5   28.22  2260.6   26.04 2912.35   27.27 3026.78   29.38
 3073.94   35.78 3148.21   34.11 3193.84   28.27  3399.5   26.82 4611.18   31.07
 5250.75   26.17 5637.38    30.4 5710.88   24.71 5867.92   29.08 5890.32   12.38
 5908.99   10.22 5930.21    13.2  5938.3   30.21 5962.12   30.59 5991.62   43.67
 6012.78   46.29 6055.01   46.35 6165.45   57.24 6589.82   68.15 6766.52   66.88
#Mann= 3 , 0 , 0
       0     .09       0 5867.92     .05       0  5938.3     .09       0
#XS Ineff= 2 , 0
         3088.61   42.54
Permanent Ineff=
       F       F
#Block Obstruct= 3 ,-1
  413.66  445.57  52.317 6111.28 6194.51   68.17 6640.98 6719.02  78.122
Bank Sta=5867.92,5938.3
XS Rating Curve= 0 ,0
Exp/Cntr=0.3,0.1

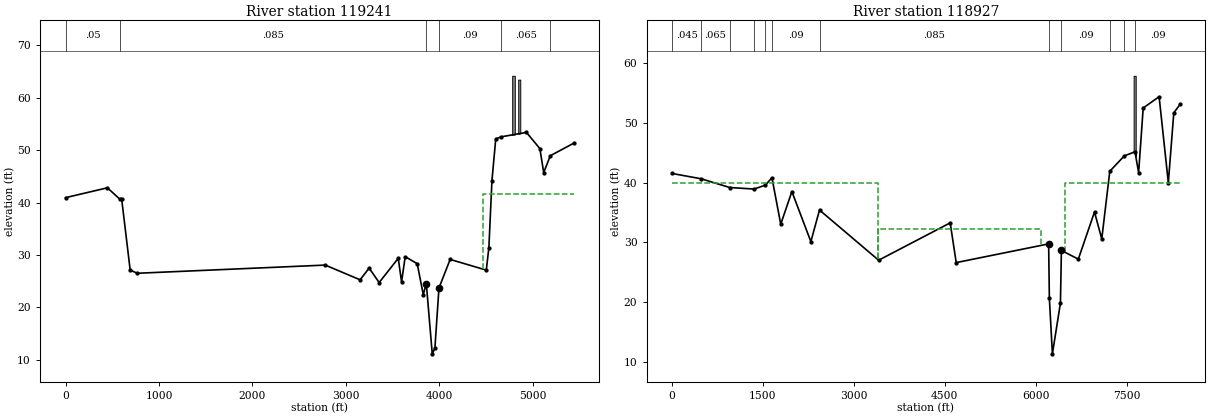
Type RM Length L Ch R = 1 ,119241  ,542.46,313.14,134.29
XS GIS Cut Line= 5
2422394.43731689617527.7197265632422194.68548584615485.569885254
2421714.41809082613924.7006835942421945.97570801613624.533508301
2421491.43670654612329.526672363
#Sta/Elev= 30
       0   40.94  448.11   42.82   577.9   40.71  600.43   40.76  692.16   27.11
  769.53   26.52 2779.58   28.08 3152.73   25.27 3248.98   27.51 3356.22   24.75
 3560.62   29.37 3596.07   24.88 3635.15   29.68 3763.46   28.35  3828.5   22.45
 3860.95   24.54 3924.64   11.15  3952.8   12.23  3996.4   23.71 4116.13   29.16
    4503   27.12 4530.38    31.4 4563.41   44.21    4604   52.15 4664.56   52.55
 4932.43   53.39 5076.25    50.3 5117.13   45.73 5188.09   48.94 5436.54   51.31
#Mann= 6 ,-1 , 0
       0     .05       0   577.9    .085       0 3860.95     .05       0
  3996.4     .09       0 4664.56    .065       0 5188.09     .09       0
#XS Ineff= 2 , 0
                         4470.16           41.71
Permanent Ineff=
       F       F
#Block Obstruct= 2 ,-1
 4779.82 4807.84   64.19 4844.36 4866.52  63.457
Bank Sta=3860.95,3996.4
XS Rating Curve= 0 ,0
Exp/Cntr=0.5,0.3

Type RM Length L Ch R = 1 ,118927  ,136.3,119.44,121.71
BEGIN DESCRIPTION:
Surveyed Section
END DESCRIPTION:
XS GIS Cut Line= 6
2423786.65447998619991.3853149412423261.57971191618165.834716797
2422866.75610352616612.9973144532422182.82470703614153.547302246
2421857.61871338612888.8189086912421524.09332275611932.156494141
#Sta/Elev= 30
       0   41.52  481.96   40.63  951.34   39.17 1354.51   38.91 1538.91   39.56
 1648.71    40.8 1793.93   33.03 1977.75   38.49 2290.82   30.11 2433.25    35.4
 3408.61      27  4588.7   33.25 4688.04    26.6 6212.63 29.73216224.364 20.6491
6274.655 11.32896407.089 19.83616423.014 28.6356 6702.13   27.18 6968.94   35.07
 7088.66   30.56 7220.97   41.89 7461.52   44.47  7636.7   45.15 7696.82   41.66
 7771.99   52.48  8034.6   54.37 8186.51   39.98 8276.77   51.67 8379.33   53.07
#Mann= 12 ,-1 , 0
       0    .045       0  481.96    .065       0  951.34    .045       0
 1354.51     .06       0 1538.91     .05       0 1648.71     .09       0
 2433.25    .085       0 6212.63     .05       06423.014     .09       0
 7220.97    .065       0 7461.52    .045       0  7636.7     .09       0
#XS Ineff= 3 ,-1
       0    3391      40    3391 6090.81   32.25 6482.74 8379.33   39.97
Permanent Ineff=
       F       F       F
#Block Obstruct= 1 ,-1
 7614.04 7648.68  57.871
Bank Sta=6212.63,6423.014
XS Rating Curve= 0 ,0
Exp/Cntr=0.5,0.3