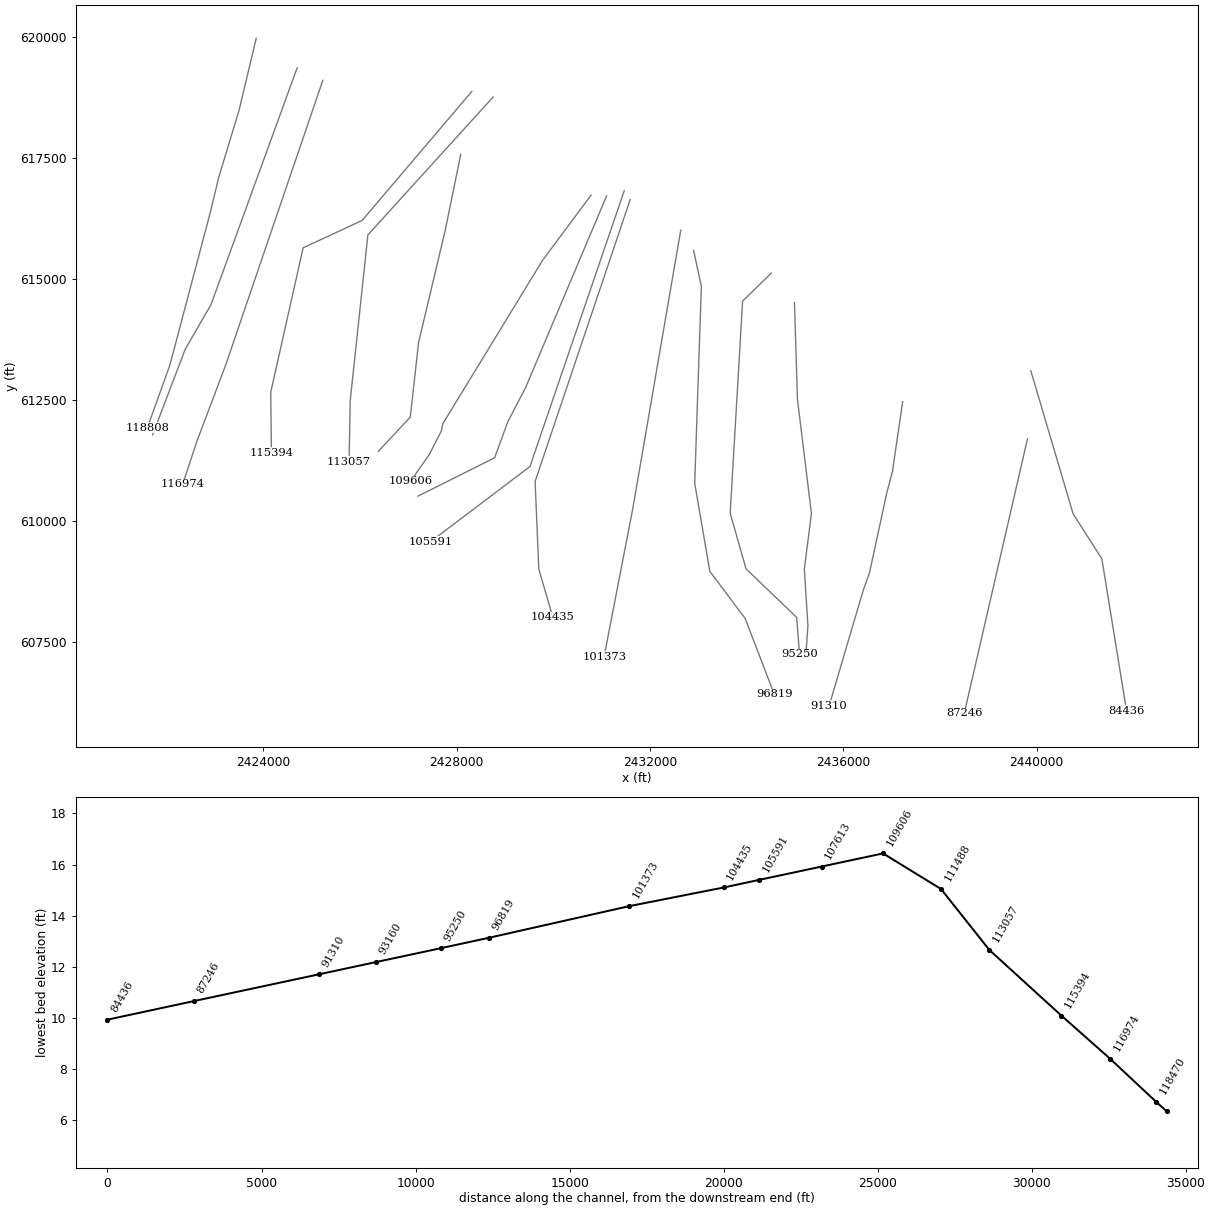
HEC-RAS study DTL_ContentneaCrk.prj: DTL_Contentnea_Crk

--- DTL_ContentneaCrk.g01 (geometry) --- (continued)

Type RM Length L Ch R = 3 ,118863  ,,,
BEGIN DESCRIPTION:
RT 123
END DESCRIPTION:
Bridge Culvert--1,0,-1,-1, 0
Deck Dist Width WeirC Skew NumUp NumDn MinLoCord MaxHiCord MaxSubmerge Is_Ogee
46.25,26.5,2.6,0, 60, 60, , , 0.98, 0, 1,1,,
       0   31.71   60.86   75.16   90.91  183.71  197.85  211.76  259.71  275.33
  307.39  344.45   418.5  471.38  490.22  573.39  604.58  790.49  826.86  849.38
 1010.96 1030.28 1402.81 1733.32  1752.6 1767.77 1785.31 2026.27  2295.6 2612.03
 3322.91 5290.37 5491.886135.8056135.8056260.4286437.7446437.744 6656.88 7092.35
 7366.16 7440.25 7494.66 7573.87  7599.5 7622.61 7653.76 7669.62 7685.28 7708.23
 7732.42  7902.6 8003.64 8061.84 8113.37 8135.78 8191.09 8214.79 8228.22 8362.68
   41.72   41.23    39.3   40.94    41.5    40.9   39.27   41.03    41.1   40.02
   41.16   39.97   40.91   39.89   40.74   40.43   39.14   39.72   38.53   39.64
   39.33   40.05   38.58    39.1   40.58    39.4   39.24   39.84    37.8    33.3
   32.14   33.39   35.28  43.467  46.167  46.704  46.062  43.362  41.224   40.02
   42.72   45.11   45.74   48.44   47.69   45.91   41.23   41.01   45.08   49.33
   52.27   54.42   54.77   50.51   39.98      39   47.46   52.18   53.09   53.57
                                                                                
                                                                                
                                                                                
                                  37.967  38.504  37.862
                                                                                
                                                                                
       0   31.71   60.86   75.16   90.91  183.71  197.85  211.76  259.71  275.33
  307.39  344.45   418.5  471.38  490.22  573.39  604.58  790.49  826.86  849.38
 1010.96 1030.28 1402.81 1733.32  1752.6 1767.77 1785.31 2026.27  2295.6 2612.03
 3322.91 5290.37 5491.886135.8056135.8056260.4286437.7446437.744 6656.88 7092.35
 7366.16 7440.25 7494.66 7573.87  7599.5 7622.61 7653.76 7669.62 7685.28 7708.23
 7732.42  7902.6 8003.64 8061.84 8113.37 8135.78 8191.09 8214.79 8228.22 8362.68
   41.72   41.23    39.3   40.94    41.5    40.9   39.27   41.03    41.1   40.02
   41.16   39.97   40.91   39.89   40.74   40.43   39.14   39.72   38.53   39.64
   39.33   40.05   38.58    39.1   40.58    39.4   39.24   39.84    37.8    33.3
   32.14   33.39   35.28  43.467  46.167  46.704  46.062  43.362  41.224   40.02
   42.72   45.11   45.74   48.44   47.69   45.91   41.23   41.01   45.08   49.33
   52.27   54.42   54.77   50.51   39.98      39   47.46   52.18   53.09   53.57
                                                                                
                                                                                
                                                                                
                                  37.967  38.504  37.862
                                                                                
                                                                                
Pier Skew, UpSta & Num, DnSta & Num=  ,6171.77, 4 ,6171.77, 4 , 3 , 3 , 0 ,,
     3.5     3.5     3.8     3.8
       4 34.2506 34.2506 38.2506
     3.5     3.5     3.8     3.8
       4 34.2506 34.2506 38.2506
Pier Skew, UpSta & Num, DnSta & Num=  ,6260.428, 4 ,6260.428, 4 , 3 , 3 , 0 ,,
     3.5     3.5     3.8     3.8
       4 34.5044 34.5044 38.5044
     3.5     3.5     3.8     3.8
       4 34.5044 34.5044 38.5044
Pier Skew, UpSta & Num, DnSta & Num=  ,6349.086, 4 ,6349.086, 4 , 3 , 3 , 0 ,,
     3.5     3.5     3.8     3.8
       4 34.3916 34.3916 38.3916
     3.5     3.5     3.8     3.8
       4 34.3916 34.3916 38.3916
BR Coef=-1 , 1 , 0 ,1.25, 0 ,,,0.8,0,2,0,
WSPro=,,,, 1 ,,,, 0 ,,,, 0 ,,,,-1 ,-1 ,-1 , 0 , 0 , 0 , 0 , 0
BC Design=,, 0 ,, 0 ,,,,,,
BC Use User HTab Curves=0
BC User HTab FreeFlow(D)= 0

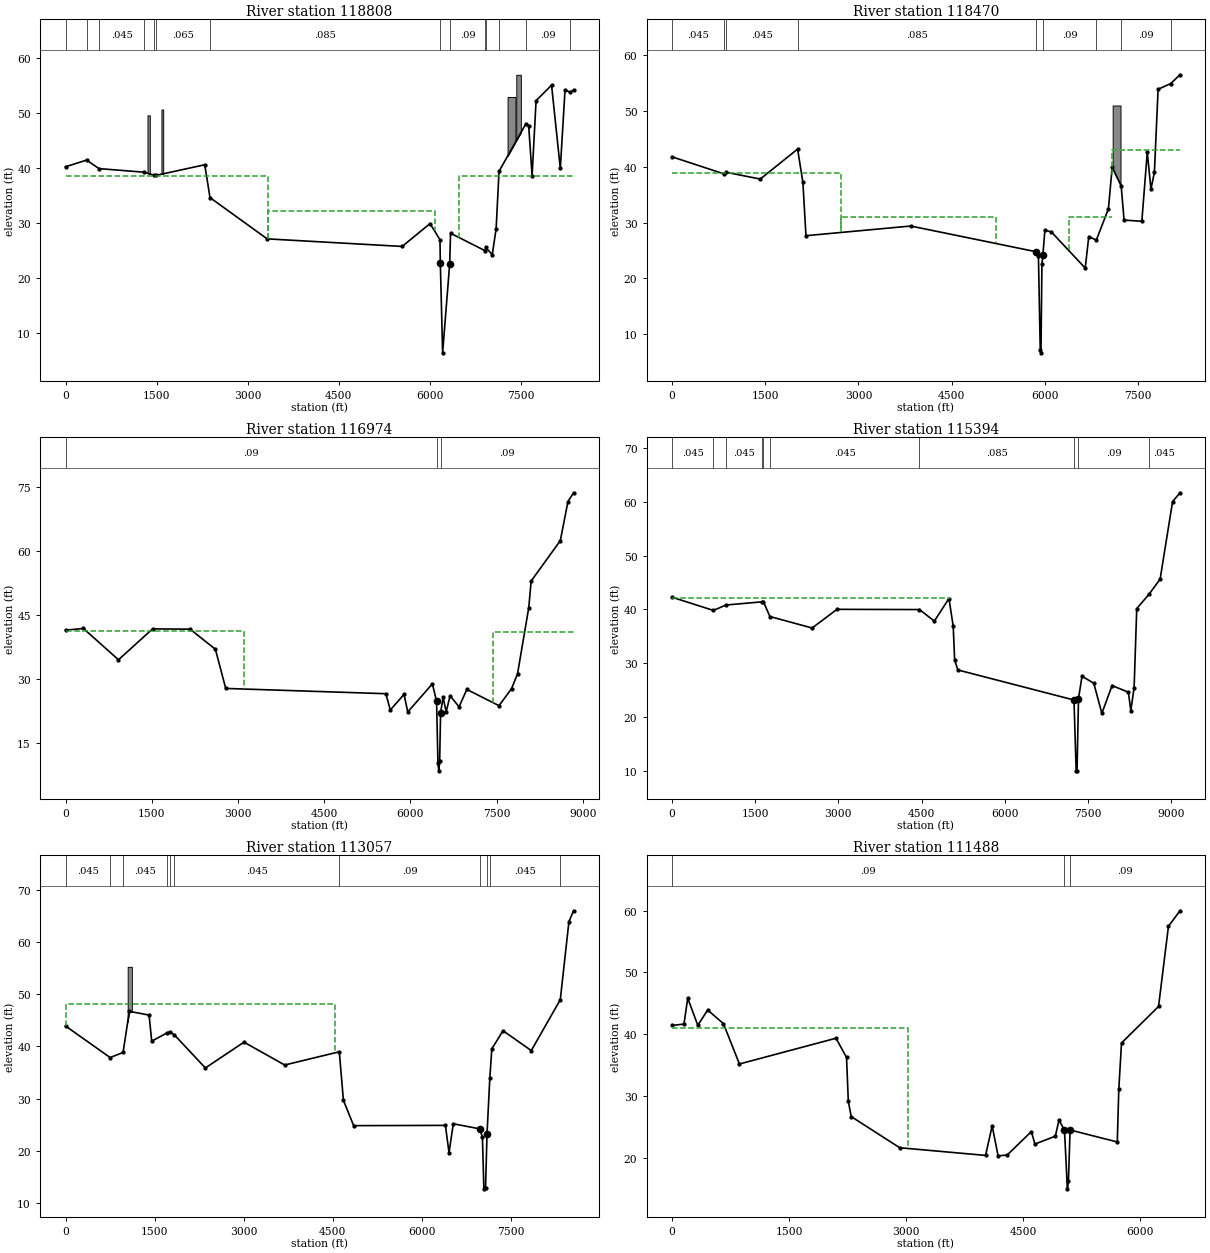
Type RM Length L Ch R = 1 ,118808  ,450.53,338.46,190.59
BEGIN DESCRIPTION:
Surveyed Section
END DESCRIPTION:
XS GIS Cut Line= 6
2423851.20367432 619970.474670412423494.03088379618476.530090332
2423073.89471436617092.4846801762422901.03210449616373.559692383
 2422065.5402832613220.3519287112421600.07312012611924.920288086
#Sta/Elev= 30
       0    40.2  348.33   41.42  550.96   39.87 1297.03   39.21 1463.6638.64751
 1497.99   38.65  2295.1   40.57 2381.37   34.59  3323.1   27.08 5548.36    25.7
 6008.33   29.866171.975 26.91316177.836 22.65046215.516  6.33256331.905 22.5571
 6346.14 28.1031 6918.88    24.9 6923.07   25.51 7033.92   24.23 7097.63   28.95
 7144.96   39.37 7587.07   48.01  7633.6   47.67  7690.2   38.61 7755.87   52.24
 8011.02   55.05 8155.17   39.89 8232.78   54.18 8322.25   53.76 8373.33    54.2
#Mann= 14 ,-1 , 0
       0    .045       0  348.33     .12       0  550.96    .045       0
 1297.03    .045       0 1463.66    .035       0 1497.99    .065       0
 2381.37    .085       06177.836     .05       06331.905     .09       0
 6918.88    .032       0 6923.07     .09       0 7144.96    .045       0
 7587.07     .09       0 8322.25    .055       0
#XS Ineff= 3 ,-1
    3330 6085.81   32.14 6487.74 8373.33    38.5       0    3330    38.5
Permanent Ineff=
       F       F       F
#Block Obstruct= 4 ,-1
 7429.48 7504.65  56.948 7285.63 7415.02  52.905 1581.11 1610.15  50.627
 1350.93 1389.26  49.569
Bank Sta=6177.836,6331.905
XS Rating Curve= 0 ,0
Exp/Cntr=0.5,0.3

Type RM Length L Ch R = 1 ,118470  ,785.08,1495.77,1016.52
XS GIS Cut Line= 4
2424698.93731689619362.0145263672422915.08673096614465.001525879
2422383.36212158613547.3477172852421705.84191895611772.073303223
#Sta/Elev= 30
       0   41.76  829.51   38.73  869.56      39 1420.25   37.78 2021.07   43.14
 2105.93   37.19 2155.35   27.65 3840.84   29.38 5862.16   24.77    5895   23.98
  5924.1    7.22 5935.71     6.7 5951.34    22.6 5965.95   24.11 5998.62   28.63
  6101.2   28.34  6647.7   21.86 6704.96    27.5  6825.7   26.85 7021.17   32.47
 7081.01   39.88 7226.16   36.54 7272.84   30.44 7558.29   30.23 7645.75   42.59
 7704.67   35.99 7760.34   38.97 7820.02   53.84 8020.53   54.84 8172.54   56.43
#Mann= 9 ,-1 , 0
       0    .045       0  829.51    .035       0  869.56    .045       0
 2021.07    .085       0 5862.16     .05       0 5965.95     .09       0
  6825.7    .045       0 7226.16     .09       0 8020.53    .055       0
#XS Ineff= 4 ,-1
       0 2721.52   38.93 2721.52    5209      31    6379 7070.52      31
 7070.52 8172.54   42.94
Permanent Ineff=
       F       F       F       F
#Block Obstruct= 1 ,-1
 7088.97 7215.51   50.94
Bank Sta=5862.16,5965.95
XS Rating Curve= 0 ,0
Exp/Cntr=0.3,0.1

Type RM Length L Ch R = 1 ,116974  ,926.38,1580.2,1330.07
XS GIS Cut Line= 5
2425229.34613037619102.4144897462424390.78387451616647.714111328
2423221.44909668613222.7681274412422632.58868408611665.137512207
2422328.66070557 610753.35369873
#Sta/Elev= 30
       0   41.45  311.26   41.86  921.45    34.5 1515.41   41.76 2167.89   41.69
 2607.94   36.97  2787.7   27.76 5573.91   26.52  5650.8   22.68  5889.9   26.36
 5954.92   22.23 6383.42   28.84 6456.27   24.73 6480.02   10.13 6495.01    8.39
 6509.78   10.76 6526.11   22.09 6570.41   25.64 6622.81   22.24 6691.52   26.04
 6847.37   23.43  6982.6   27.52 7542.36   23.71 7760.44    27.7 7864.67   31.19
 8060.32   46.76 8101.52      53 8609.04   62.49 8741.67   71.68 8839.37   73.75
#Mann= 3 , 0 , 0
       0     .09       0 6456.27     .05       0 6526.11     .09       0
#XS Ineff= 2 , 0
         3101.27    41.2 7441.23           40.94
Permanent Ineff=
       F       F
Bank Sta=6456.27,6526.11
XS Rating Curve= 0 ,0
Exp/Cntr=0.3,0.1

Type RM Length L Ch R = 1 ,115394  ,1495.62,2336.68,1850.14
XS GIS Cut Line= 5
2428313.33111572618872.2178955082426041.58972168616204.065307617
2424821.86291504615639.9417114262424151.01312256612651.610717773
2424166.25970459611401.390686035
#Sta/Elev= 30
       0   42.27  747.55   39.82     972   40.82 1630.68   41.42 1648.09   41.47
 1765.35   38.69 2526.87   36.56 2976.01   40.02  4462.4   39.98  4731.4   37.84
 4994.75   42.03 5071.35   36.89 5097.25   30.62 5155.51   28.78 7249.04   23.21
 7288.61   10.08 7304.39    10.1 7330.58   23.45 7393.73   27.62 7606.89   26.31
 7751.92   20.73 7936.17   25.89 8229.95   24.65 8274.28   21.25 8333.45   25.51
 8380.96   40.17  8601.4    42.8  8802.5   45.63 9027.09   59.99 9161.15   61.63
#Mann= 10 ,-1 , 0
       0    .045       0  747.55     .09       0     972    .045       0
 1630.68    .035       0 1648.09     .08       0 1765.35    .045       0
  4462.4    .085       0 7249.04     .05       0 7330.58     .09       0
  8601.4    .045       0
#XS Ineff= 2 , 0
       0 4994.75   42.05               0
Permanent Ineff=
       F       F
Bank Sta=7249.04,7330.58
XS Rating Curve= 0 ,0
Exp/Cntr=0.3,0.1

Type RM Length L Ch R = 1 ,113057  ,1285.19,1569.06,1319.64
XS GIS Cut Line= 4
2428753.72949219618757.1328735352426161.80987549 615906.02130127
2425795.89190674612475.5394897462425772.99627686611218.387695313
#Sta/Elev= 30
       0   43.94  752.47   37.87   969.9   38.85 1075.38   46.75 1408.46   46.03
 1452.25   41.01 1715.52   42.64 1758.32   42.84 1835.36   42.22 2356.57   35.87
 3007.43   40.83  3693.5   36.44 4613.2438.98051 4682.74   29.66 4855.17   24.79
 6401.19   24.84 6462.34   19.59 6534.16   25.15 6977.64   24.18 7025.07    22.6
 7049.55   12.65 7077.61   12.88 7102.69   23.23  7149.7   33.94 7183.54   39.55
 7371.97   43.03 7848.25   39.21 8337.04   48.99 8482.55   63.98 8560.47   66.07
#Mann= 11 ,-1 , 0
       0    .045       0  752.47     .09       0   969.9    .045       0
 1715.52    .035       0 1758.32     .08       0 1835.36    .045       0
 4613.24     .09       0 6977.64     .05       0 7102.69     .09       0
  7149.7    .045       0 8337.04     .09       0
#XS Ineff= 2 , 0
         4538.88   48.13
Permanent Ineff=
       F       F
#Block Obstruct= 1 ,-1
 1047.52 1117.94  55.304
Bank Sta=6977.64,7102.69
XS Rating Curve= 0 ,0
Exp/Cntr=0.3,0.1

Type RM Length L Ch R = 1 ,111488  ,1288.09,1881.43,817.59
XS GIS Cut Line= 5
2428084.29589844 617572.736511232427761.37249756615996.110473633
2427210.50311279613678.6600952152427039.54370117612140.024902344
2426377.01470947611431.883911133
#Sta/Elev= 30
       0   41.43  153.91   41.66  201.92   45.85     331   41.46  457.13   43.93
  659.66   41.72  864.47   35.21 2101.47   39.37 2236.66   36.27 2259.14    29.2
  2296.5   26.71 2918.06   21.68 4017.67   20.44 4102.44   25.21 4178.17   20.38
 4293.85   20.49 4604.74   24.29  4649.8   22.27 4912.41   23.55 4958.39   26.16
 5029.03   24.49 5066.25   15.04  5079.8   16.29 5100.63   24.55 5705.51   22.61
 5725.04   31.18 5759.63    38.6 6234.05    44.5 6361.17   57.46 6509.23   59.96
#Mann= 3 , 0 , 0
       0     .09       0 5029.03     .05       0 5100.63     .09       0
#XS Ineff= 2 , 0
       0 3018.99    41.1               0
Permanent Ineff=
       F       F
Bank Sta=5029.03,5100.63
XS Rating Curve= 0 ,0
Exp/Cntr=0.3,0.1

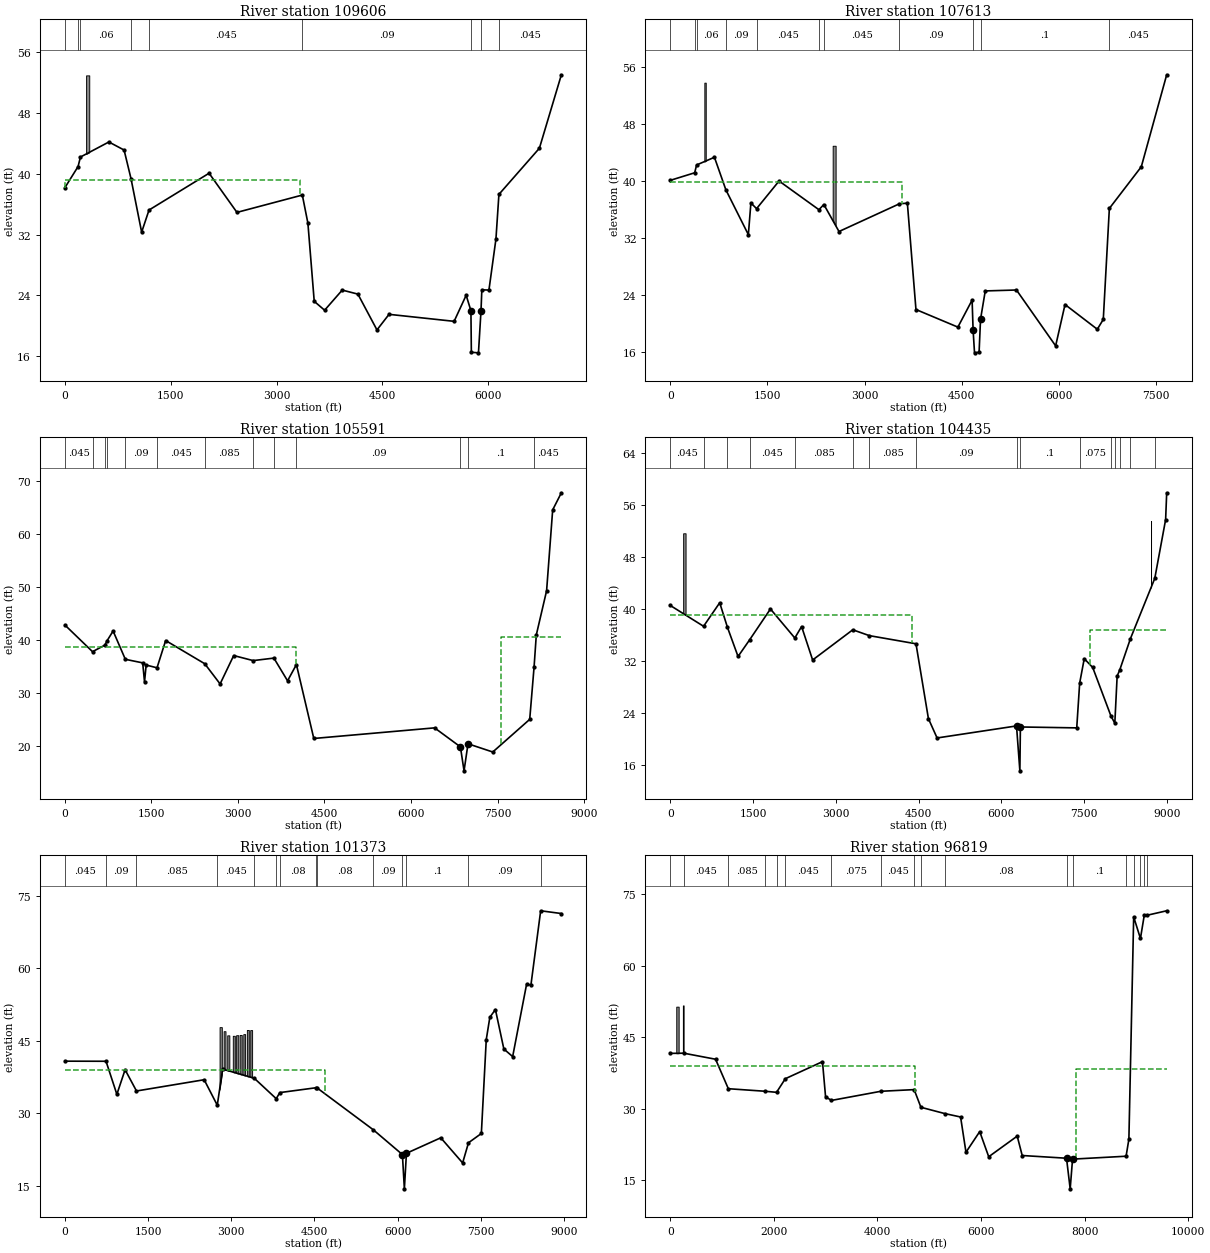
Type RM Length L Ch R = 1 ,109606  ,1094.5,1993.84,1010.51
BEGIN DESCRIPTION:
Surveyed Section
END DESCRIPTION:
XS GIS Cut Line= 6
 2430781.5255127616729.3369140632429775.14068604615378.322509766
2427712.98413086612003.2913208012427682.09667969611852.353088379
2427434.63287354611369.3129272462427046.11187744610813.661499023
#Sta/Elev= 30
       0   38.17   186.5   40.94  219.5842.18959  623.13   44.17  838.85   43.11
  936.73   39.35 1087.55   32.31 1192.21   35.22 2043.55   40.06 2438.73   34.91
 3365.48   37.19 3444.69   33.48 3534.24   23.21 3681.48   22.04 3931.39   24.69
 4153.31   24.16 4423.61   19.45 4594.72    21.5 5517.32   20.585687.958 24.0078
5755.521 21.98375761.855 16.51145862.495 16.43555898.388 21.94825910.353 24.7214
6010.993 24.69616110.226  31.3996152.453 37.2769 6726.41   43.35 7037.81   53.01
#Mann= 9 ,-1 , 0
       0    .045       0   186.5    .035       0  219.58     .06       0
  936.73     .09       0 1192.21    .045       0 3365.48     .09       0
5755.521     .05       05898.388     .09       06152.453    .045       0
#XS Ineff= 2 , 0
         3334.54   39.21
Permanent Ineff=
       F       F
#Block Obstruct= 1 ,-1
  300.02   344.8  52.932
Bank Sta=5755.521,5898.388
XS Rating Curve= 0 ,0
Exp/Cntr=0.3,0.1

Type RM Length L Ch R = 1 ,107613  ,937.47,2021.64,777.83
XS GIS Cut Line= 5
2431101.98730469616711.3848876952429424.86291504612747.272521973
2429058.94470215612045.9295043952428784.50628662611298.846923828
2427198.86132813610506.024291992
#Sta/Elev= 30
       0   40.13  377.0741.19387  406.9642.29094  682.09   43.37  859.14   38.79
 1205.84   32.51 1244.98   36.96 1332.78   36.16 1679.76   40.04 2295.38   36.01
 2371.26   36.74 2605.18   32.95 3537.73   36.84 3660.53   36.93 3793.17      22
  4440.5   19.53 4659.98   23.32  4675.6   19.07  4697.3   15.92 4767.81      16
 4790.19   20.64 4863.12   24.61 5344.75   24.74 5949.67    16.9 6094.47    22.7
 6592.73   19.23 6685.17   20.61 6778.86   36.19 7272.04   42.04 7664.06   54.95
#Mann= 11 ,-1 , 0
       0    .045       0  377.07    .035       0  406.96     .06       0
  859.14     .09       0 1332.78    .045       0 2295.38    .085       0
 2371.26    .045       0 3537.73     .09       0  4675.6     .05       0
 4790.19      .1       0 6778.86    .045       0
#XS Ineff= 2 , 0
         3573.24   39.93
Permanent Ineff=
       F       F
#Block Obstruct= 2 ,-1
  526.36  547.91  53.844 2507.41 2553.18  44.988
Bank Sta=4675.6,4790.19
XS Rating Curve= 0 ,0
Exp/Cntr=0.3,0.1

Type RM Length L Ch R = 1 ,105591  ,610.85,1156.44,1354.38
XS GIS Cut Line= 3
2431467.62188721 616820.816284182429516.05889893611118.593322754
2427457.76971436 609563.44152832
#Sta/Elev= 30
       0   42.88  478.53   37.86   693.739.09868  728.99   39.89  835.22   41.76
 1047.43   36.42  1348.2   35.75 1379.99   32.16 1408.15   35.34 1596.54   34.82
 1746.21   39.96 2423.64   35.59 2690.18   31.78 2925.94   37.13 3263.65   36.18
 3622.55   36.65 3859.67   32.37  4013.3   35.43 4314.66    21.5 6408.61    23.5
 6856.32   19.92 6919.42    15.4 6988.12    20.5 7417.28   18.95 8057.84    25.1
 8133.31   34.94 8172.01   41.01 8350.67   49.35 8456.01   64.59 8606.68   67.81
#Mann= 13 ,-1 , 0
       0    .045       0  478.53     .06       0   693.7    .035       0
  728.99     .06       0 1047.43     .09       0 1596.54    .045       0
 2423.64    .085       0 3263.65    .045       0 3622.55    .085       0
  4013.3     .09       0 6856.32     .05       0 6988.12      .1       0
 8133.31    .045       0
#XS Ineff= 2 , 0
         4014.47    38.7 7567.81            40.7
Permanent Ineff=
       F       F
Bank Sta=6856.32,6988.12
XS Rating Curve= 0 ,0
Exp/Cntr=0.3,0.1

Type RM Length L Ch R = 1 ,104435  ,2642.79,3061.77,2027.62
XS GIS Cut Line= 4
2431589.87811279616635.1519165042429623.06848145610810.956115723
2429699.30133057608996.6123046882429988.98651123608005.584289551
#Sta/Elev= 30
       0   40.51  603.62   37.31  896.06   40.92 1037.21   37.13 1228.43   32.67
 1438.42   35.23 1815.52   39.97 2257.04   35.51 2380.04   37.27 2580.07   32.13
 3307.74   36.77  3608.2   35.87  4452.9   34.62 4678.12   23.12 4835.14   20.15
 6274.55      22 6335.29    15.1 6344.71   21.84 7365.62    21.7 7418.81   28.58
 7501.65   32.33 7655.11   30.98 7987.34   23.49 8055.71   22.42 8097.96   29.66
 8142.97   30.55 8339.07   35.42 8779.87   44.67 8976.39    53.7 8995.77   57.82
#Mann= 16 ,-1 , 0
       0    .045       0  603.62     .06       0 1037.21     .09       0
 1438.42    .045       0 2257.04    .085       0 3307.74    .045       0
  3608.2    .085       0  4452.9     .09       0 6274.55     .05       0
 6344.71      .1       0 7418.81    .075       0 7987.34    .032       0
 8055.71    .075       0 8142.97      .1       0 8339.07     .05       0
 8779.87     .09       0
#XS Ineff= 2 , 0
         4376.13    39.1 7613.02           36.76
Permanent Ineff=
       F       F
#Block Obstruct= 2 ,-1
  233.75   277.7  51.597 8712.31 8712.52  53.491
Bank Sta=6274.55,6344.71
XS Rating Curve= 0 ,0
Exp/Cntr=0.3,0.1

Type RM Length L Ch R = 1 ,101373  ,2186.28,4554.16,3305.35
XS GIS Cut Line= 3
2432636.52667236616002.0535278322431645.49871826610254.090698242
2431050.88189697607189.526916504
#Sta/Elev= 30
       0   40.78  741.24   40.76  936.86   33.92 1085.27   39.01 1290.86   34.61
 2511.42   36.94 2747.85   31.67 2844.28   39.14 3413.83   37.26 3811.27   33.02
 3876.24   34.28 4534.75   35.29 4546.68   35.26 5561.64   26.59 6087.26   21.46
 6122.63   14.37 6159.79   21.72 6779.24   24.93 7173.47   19.73 7279.22    23.9
 7511.27   25.82 7599.67   45.24 7664.38   49.86 7764.85   51.46 7917.21   43.29
 8075.96   41.73 8327.92   56.74 8405.23   56.52 8581.13   71.89 8954.49   71.32
#Mann= 14 ,-1 , 0
       0    .045       0  741.24     .09       0 1290.86    .085       0
 2747.85    .045       0 3413.83    .032       0 3811.27    .075       0
 3876.24     .08       0 4534.75    .075       0 4546.68     .08       0
 5561.64     .09       0 6087.26     .05       0 6159.79      .1       0
 7279.22     .09       0 8581.13    .045       0
#XS Ineff= 2 , 0
         4683.54   39.03
Permanent Ineff=
       F       F
#Block Obstruct= 9 ,-1
 2789.46 2829.86   47.82 2862.63 2895.96  46.978  2927.6  2965.4  46.121
 3027.79 3064.25  46.027  3088.2 3126.65  46.151 3151.96    3189  46.205
 3217.89 3250.22  46.375 3281.62 3316.78  47.232 3342.47  3376.3  47.209
Bank Sta=6087.26,6159.79
XS Rating Curve= 0 ,0
Exp/Cntr=0.3,0.1

Type RM Length L Ch R = 1 ,96819   ,859.5,1568.97,1306.55
XS GIS Cut Line= 6
2432902.92407227615588.2626953132433063.43127441614843.313110352
2432926.21191406610772.4744873052433238.81567383608951.330688477
2433970.65167236607975.5490722662434571.32647705606412.823486328
#Sta/Elev= 30
       0   41.58  259.74   41.62  874.91   40.35 1121.37   34.16 1836.36   33.62
 2052.01    33.4 2221.65   36.26 2938.88   39.84  2998.5   32.46 3112.99    31.7
 4066.63   33.62 4708.78   33.97 4839.13   30.26 5295.34   28.95  5605.3   28.22
 5709.24   20.82 5974.56   25.15 6148.38   19.87 6698.42    24.2  6794.8   20.13
 7650.22   19.56 7721.14   13.13 7766.83   19.37 8800.34   19.98 8854.48   23.57
 8946.98   70.25 9077.32   65.71 9152.08   70.64 9201.92   70.58 9584.33   71.53
#Mann= 18 ,-1 , 0
       0    .065       0  259.74    .045       0 1121.37    .085       0
 1836.36    .032       0 2052.01    .085       0 2221.65    .045       0
 3112.99    .075       0 4066.63    .045       0 4708.78    .075       0
 4839.13     .07       0 5295.34     .08       0 7650.22     .05       0
 7766.83      .1       0 8800.34     .09       0 8946.98    .045       0
 9077.32     .09       0 9152.08    .035       0 9201.92    .045       0
#XS Ineff= 2 , 0
         4728.75   39.03 7839.06           38.33
Permanent Ineff=
       F       F
#Block Obstruct= 2 ,-1
     116  162.24  51.395  243.68  258.33  51.652
Bank Sta=7650.22,7766.83
XS Rating Curve= 0 ,0
Exp/Cntr=0.3,0.1

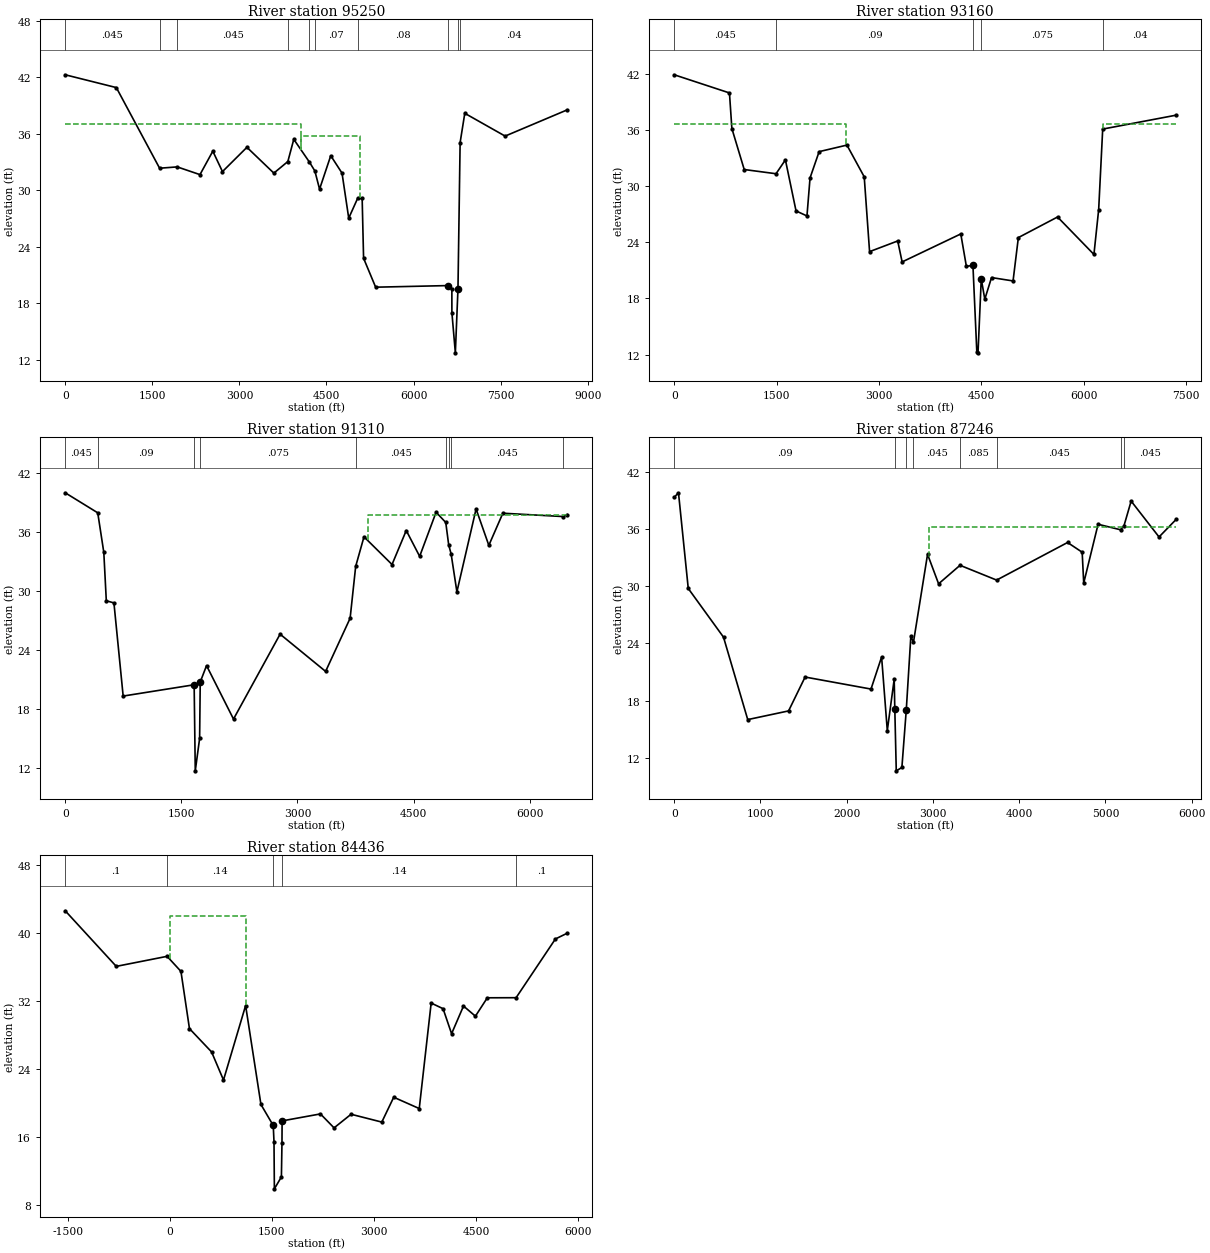
Type RM Length L Ch R = 1 ,95250   ,1810.35,2090.06,1545.01
XS GIS Cut Line= 6
2434511.85687256615117.751525879 2433917.2399292614538.381286621
2433660.08190918610154.3021240232433988.12188721609002.946716309
2435036.56268311607999.530883789 2435094.4520874607240.536682129
#Sta/Elev= 30
       0   42.24  880.46   40.88 1625.87   32.32 1929.42   32.46 2321.14   31.64
  2542.4   34.13 2708.57   31.96 3129.67   34.54 3593.57    31.8 3834.63   33.03
 3936.75   35.39 4207.37   32.96 4299.91   32.03 4380.82    30.1  4573.7   33.65
 4767.83    31.8 4883.22   27.02 5035.87   29.11 5114.58   29.11 5139.13   22.76
 5346.99   19.69 6587.37   19.86 6659.69    19.5 6660.01      17 6719.74   12.72
 6764.85   19.51 6801.84   35.04 6882.16   38.15 7576.85   35.73 8648.24   38.52
#Mann= 10 ,-1 , 0
       0    .045       0 1625.87     .09       0 1929.42    .045       0
 3834.63    .045       0 4207.37    .075       0 4299.91     .07       0
 5035.87     .08       0 6587.37     .05       0 6764.85    .075       0
 6801.84     .04       0
#XS Ineff= 2 ,-1
       0    4061      37    4061 5081.37   35.75
Permanent Ineff=
       F       F
Bank Sta=6587.37,6764.85
XS Rating Curve= 0 ,0
Exp/Cntr=0.3,0.1

Type RM Length L Ch R = 1 ,93160   ,2040.8,1850.03,1504.85
XS GIS Cut Line= 6
2434990.98187256614505.7730712892435051.96807861 612513.55267334
2435341.65612793610147.1613159182435194.26971436608996.673278809
2435269.31152344607827.6096801762435224.28649902607177.962097168
#Sta/Elev= 30
       0   41.88  809.36   39.94  844.79   36.14 1025.71   31.76 1491.91   31.31
 1629.42   32.79 1785.15   27.34 1945.32    26.8 1990.29   30.86 2123.59   33.67
 2530.87   34.37 2784.51   30.98  2862.9   22.99 3275.42   24.13  3339.9   21.89
 4199.72   24.88 4281.64   21.42 4377.84   21.52 4434.57   12.31 4452.18   12.18
 4499.84   20.07 4551.75   17.91 4650.33   20.22 4965.83   19.86 5043.51   24.49
 5617.88   26.69  6151.1   22.69 6220.72   27.49 6279.71   36.08 7358.99   37.57
#Mann= 5 ,-1 , 0
       0    .045       0 1491.91     .09       0 4377.84     .05       0
 4499.84    .075       0 6279.71     .04       0
#XS Ineff= 2 , 0
       0 2524.41   36.57 6287.46       0   36.57
Permanent Ineff=
       F       F
Bank Sta=4377.84,4499.84
XS Rating Curve= 0 ,0
Exp/Cntr=0.3,0.1

Type RM Length L Ch R = 1 ,91310   ,3021.1,4063.51,2778.38
XS GIS Cut Line= 6
2437229.68890381612459.474914551 2437018.8572998611017.957702637
2436903.07849121610580.5712890632436542.87792969608921.075683594
2436414.23468018 608560.875122072435706.69787598606168.114074707
#Sta/Elev= 30
       0      40  420.26   37.96  498.58   33.93  530.82   29.01  629.32   28.79
  748.55   19.31 1665.48   20.46 1679.92    11.7 1736.17      15 1744.02   20.74
 1825.58   22.41 2173.78   16.97 2775.57   25.61 3363.44   21.82 3680.05   27.23
 3751.88   32.51 3859.24   35.52 4221.47    32.7 4405.08   36.16 4578.24   33.53
 4790.46   38.02 4915.3836.98166    4953   34.71 4984.77   33.77 5059.26   29.92
 5307.02   38.35  5471.7   34.65 5652.88   37.92 6431.69   37.58 6485.52   37.78
#Mann= 9 ,-1 , 0
       0    .045       0  420.26     .09       0 1665.48     .05       0
 1744.02    .075       0 3751.88    .045       0 4915.38    .035       0
    4953    .055       0 4984.77    .045       0 6431.69     .08       0
#XS Ineff= 2 , 0
                         3905.06           37.74
Permanent Ineff=
       F       F
Bank Sta=1665.48,1744.02
XS Rating Curve= 0 ,0
Exp/Cntr=0.3,0.1

Type RM Length L Ch R = 1 ,87246   ,2137.67,2810.13,2358.79
XS GIS Cut Line= 4
2439812.50012207 611689.000122072439225.25012207     609141.1875
2439225.25427246609141.1740722662438504.68029785606015.125671387
#Sta/Elev= 30
       0   39.32   49.37   39.79  162.65   29.76  571.32   24.66  852.34   16.02
 1325.97   16.93 1517.52   20.48 2281.83   19.22 2404.76   22.58 2470.78   14.87
 2550.81   20.25 2557.86   17.12 2574.78   10.65 2639.95      11 2690.92   17.04
  2743.9   24.77 2773.91   24.11 2937.58   33.34 3065.64   30.25 3314.25   32.19
 3738.73   30.64 4561.34   34.58 4730.61   33.56 4748.48   30.33 4915.14   36.49
 5175.7635.91312 5215.35   36.33  5298.5   38.92 5621.87   35.16 5822.65   37.02
#Mann= 8 ,-1 , 0
       0     .09       0 2557.86     .05       0 2690.92      .1       0
 2773.91    .045       0 3314.25    .085       0 3738.73    .045       0
 5175.76    .035       0 5215.35    .045       0
#XS Ineff= 2 , 0
                         2951.18           36.19
Permanent Ineff=
       F       F
Bank Sta=2557.86,2690.92
XS Rating Curve= 0 ,0
Exp/Cntr=0.3,0.1

Type RM Length L Ch R = 1 ,84436   ,145.77,80.9,67.63
BEGIN DESCRIPTION:
Tie in section to Sta. 84436 from Lenior County Effective Model
END DESCRIPTION:
XS GIS Cut Line= 6
2439882.52547488613096.3072622242440757.75012207     610139.3125
2440777.75012207     610108.18752440847.07391357 610000.00012207
 2441352.0980835609212.1610717772441864.27960193606063.196222845
#Sta/Elev= 30
-1535.25   42.58 -785.25   36.05  -38.65   37.23  164.75   35.46  289.75   28.74
  614.75      26  789.75    22.7 1114.75   31.45 1339.75   19.83  1520.5   17.36
  1531.7   15.45  1537.1    9.92  1640.4   11.32  1648.8   15.35  1650.6    17.9
 2213.85   18.72 2413.85   17.08 2663.85   18.68 3115.15   17.76 3290.15   20.68
 3665.15   19.35 3840.15   31.74 4015.15   31.08 4140.15   28.14 4315.15   31.39
 4490.15    30.2 4665.15   32.36 5087.75   32.37 5665.15   39.27 5840.15   39.95
#Mann= 5 ,-1 , 0
-1535.25      .1       0  -38.65     .14       0  1520.5    .052       0
  1650.6     .14       0 5087.75      .1       0
#XS Ineff= 2 , 0
       0 1115.24   41.93               0
Permanent Ineff=
       F       F
Bank Sta=1520.5,1650.6
XS Rating Curve= 0 ,0
Exp/Cntr=0.3,0.1
Stream Node=Contentnea Creek,Main            , 0 , 0 ,Upstream end
Stream Node=Contentnea Creek,Main            , 0 , 1 ,Downstream end

Chan Stop Cuts=-1
Use User Specified Reach Order=0