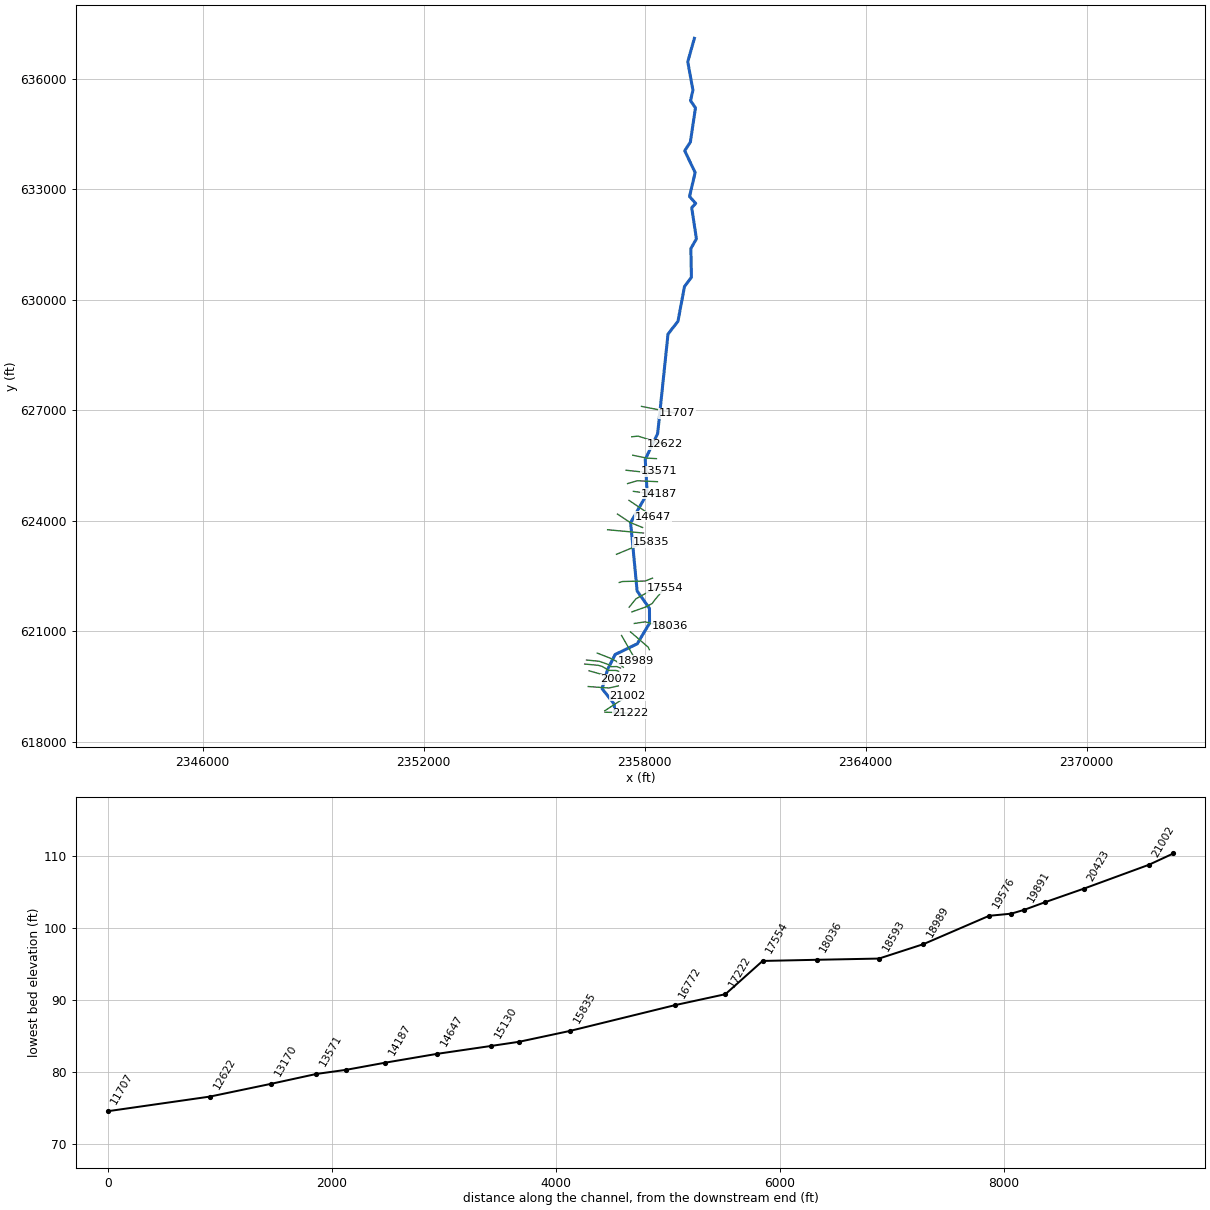
--- DTL_Cow_Branch.prj (project) ---

Proj Title=DTL_Cow_Branch
Current Plan=p01
Default Exp/Contr=0.3,0.1
English Units
Geom File=g01
Flow File=f01
Flow File=f02
Plan File=p01
Plan File=p02
Y Axis Title=Elevation
X Axis Title(PF)=Main Channel Distance
X Axis Title(XS)=Station
BEGIN DESCRIPTION:
END DESCRIPTION:
DSS Export Rating Curves= 0
DSS Export Rating Curve Sorted= 0
DSS Export Volume Flow Curves= 0
DXF OffsetX= 0
DXF OffsetY= 0
DXF ScaleX= 1
DXF ScaleY= 10

--- DTL_Cow_Branch.p01 (plan) ---

Plan Title=DTL_Cow_Branch
Program Version=4.00
Short Identifier=Multi Profile
Geom File=g01
Flow File=f01
Subcritical Flow
K Sum by GR= 0
Std Step Tol= 0.01
Critical Tol= 0.01
Num of Std Step Trials= 20
Max Error Tol= 0.3
Flow Tol Ratio= 0.001
Split Flow NTrial= 30
Split Flow Tol= 0.02
Split Flow Ratio= 0.02
Log Output Level= 0
Friction Slope Method= 1
Unsteady Friction Slope Method= 2
Unsteady Bridges Friction Slope Method= 1
Parabolic Critical Depth
Global Vel Dist= 0 , 0 , 0
Global Log Level= 0
CheckData=True
Encroach Param=-1 ,10,10, 2
Encroach River=Cow Branch
Encroach Reach=Main
Encroach Node=21222
       1     255     290
Encroach Node=21002
       1     299  349.96
Encroach Node=20423
       1     355     412
Encroach Node=20072
       1     440     515
Encroach Node=19891
       1     585     661
Encroach Node=19774
       1     595     669
Encroach Node=19576
       1     415     445
Encroach Node=18989
       1     320     375
Encroach Node=18593
       1     270     335
Encroach Node=18036
       1     395     460
Encroach Node=17554
       1     380     555
Encroach Node=17222
       1     385     530
Encroach Node=16772
       1     435     515
Encroach Node=15835
       1     385     475
Encroach Node=15381
       1     550     640
Encroach Node=15130
       1     400     480
Encroach Node=14647
       1     390     470
Encroach Node=14187
       1     340     415
Encroach Node=13839
       1     490     560
Encroach Node=13571
       1     500     575
Encroach Node=13170
       1     320     420
Encroach Node=12622
       1     600     700
Encroach Node=11707
       1     445     550
Encroach Node=11070
       1     320     420
Encroach Node=10425
       1     290     385
Encroach Node=10016
       1     495     575
Encroach Node=9822
       1  667.38  710.63
Encroach Node=9742
       1  671.57 700.805
Encroach Node=9537
       1     380     440
Encroach Node=9012
       1     590     663
Encroach Node=8630
       1     330     420
Encroach Node=8141
       1     440     530
Encroach Node=7924
       1     400     490
Encroach Node=7292
       1     500     595
Encroach Node=6747
       1     493   593.1
Encroach Node=6417
       1     605     705
Encroach Node=6032
       1     490     570
Encroach Node=5364
       1     500     580
Encroach Node=4871
       1     360     470
Encroach Node=4234
       1     545     675
Encroach Node=3479
       1  292.16     415
Encroach Node=2845
       1     360     425
Encroach Node=2690
       1  818.04  861.96
Encroach Node=2559
       1  842.76  881.96
Encroach Node=2396
       1  617.57  650.27
Encroach Node=2307
       1     580  618.53
Encroach Node=1765
       1     280     335
Encroach Node=1379
       1     490     550
Computation Interval=1HOUR
Output Interval=1HOUR
Run HTab= 0
Run UNet= 0
Run PostProcess= 0
Run WQNet= 0
UNET Theta= 1
UNET Theta Warmup= 1
UNET ZTol= 0.02
UNET ZSATol= 0.05
UNET MxIter= 20
UNET MaxInSteps= 0
UNET DtIC= 0
UNET DtMin= 0
UNET MaxCRTS= 20
UNET WFStab= 2
UNET SFStab= 1
UNET WFX= 1
UNET SFX= 1
UNET DSS MLevel= 4
UNET DZMax Abort= 100
UNET Convert EG Bridges= 0
UNET Use Existing IB Tables=-1
UNET Froude Reduction=False
UNET Froude Limit= 1
UNET Froude Power= 10
UNET Time Slicing=0,0, 5
Instantaneous Interval=1HOUR
Write IC File= 0
Echo Input=False
Echo Output=False
Write Detailed= 0
Detailed Automatic Start=False, 10
WQ ULTIMATE=-1
WQ Max Comp Step=1HOUR
WQ Output Interval=15MIN
WQ Output Selected Increments= 0
WQ Output face flow=0
WQ Output face velocity=0
WQ Output face area=0
WQ Output face dispersion=0
WQ Output cell volume=0
WQ Output cell surface area=0
WQ Output cell continuity=0
WQ Output face conc=0
WQ Output face dconc_dx=0
WQ Output face courant=0
WQ Output face peclet=0
WQ Output face adv mass=0
WQ Output face disp mass=0
WQ Output cell mass=0
WQ Output cell source sink temp=0
WQ Output cell source sink nsm=0
WQ Output MaxMinRange=-1
WQ Daily Max Min Mean=-1
WQ Daily Range=0
WQ Daily Time=0
WQ Create Restart=0
WQ Fixed Restart=0
WQ System Summary=False
Sorting and Armoring Iterations= 10
XS Update Threshold= 0.02
Hydraulics Update Threshold= 0.02
Energy Slope Method= 1
Volume Change Method= 0
XS Weighting Method= 0
Number of US Weighted Cross Sections= 1
Number of DS Weighted Cross Sections= 1
Upstream XS Weight=0.25
Main XS Weight=0.5
Downstream XS Weight=0.25
Number of DS XS's Weighted with US Boundary= 1
Upstream Boundary Weight= 1
Weight of XSs Associated with US Boundary= 0
Number of US XS's Weighted with DS Boundary= 1
Downstream Boundary Weight= 0.5
Weight of XSs Associated with DS Boundary= 0.5
Sediment Output Level= 4
Mass or Volume Output= 0
Output Increment Type= 1
Profile and TS Output Increment= 10
XS Output Flag= 0
XS Output Increment= 10
Disregard all LS=0
Disregard all Conn=0
Disregard all Breaches=0
Disregard all Pumps=0

--- DTL_Cow_Branch.p02 (plan) ---

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Plan Title=DTL_Cow_Branch_Future
Short Identifier=Future
Geom File=g01
Flow File=f02
Encroach Param=-1 ,0,0, 0

--- DTL_Cow_Branch.f01 (steady flow) ---

Flow Title=DTL_Cow_Branch
Program Version=4.00
Number of Profiles= 6
Profile Names=100-yr,FW,10-yr,25-yr,50-yr,500-yr
River Rch & RM=Cow Branch,Main            ,21222
     470     470     190     280     370     770
River Rch & RM=Cow Branch,Main            ,16772
     670     670     280     410     530    1090
River Rch & RM=Cow Branch,Main            ,12622
     850     850     360     530     680    1370
River Rch & RM=Cow Branch,Main            ,9012
    1000    1000     430     620     800    1590
River Rch & RM=Cow Branch,Main            ,4871
    1070    1070     460     670     850    1690
Boundary for River Rch & Prof#=Cow Branch,Main            , 1
Up Type= 0
Dn Type= 3
Dn Slope=0.00203
Boundary for River Rch & Prof#=Cow Branch,Main            , 2
Up Type= 0
Dn Type= 3
Dn Slope=0.00203
Boundary for River Rch & Prof#=Cow Branch,Main            , 3
Up Type= 0
Dn Type= 3
Dn Slope=0.00203
Boundary for River Rch & Prof#=Cow Branch,Main            , 4
Up Type= 0
Dn Type= 3
Dn Slope=0.00203
Boundary for River Rch & Prof#=Cow Branch,Main            , 5
Up Type= 0
Dn Type= 3
Dn Slope=0.00203
Boundary for River Rch & Prof#=Cow Branch,Main            , 6
Up Type= 0
Dn Type= 3
Dn Slope=0.00203
DSS Import GetInterval= 0
DSS Import GetPeak= 0
DSS Import FillOption= 0

--- DTL_Cow_Branch.f02 (steady flow) ---

Flow Title=DTL_Cow_Branch_Future
Program Version=4.00
Number of Profiles= 3
Profile Names=100-yr 10%,100-yr 20%,100-yr 35%
River Rch & RM=Cow Branch,Main            ,21222
     830    1060    1300
River Rch & RM=Cow Branch,Main            ,16772
    1180    1510    1850
River Rch & RM=Cow Branch,Main            ,12622
    1480    1900    2320
River Rch & RM=Cow Branch,Main            ,9012
    1730    2210    2700
River Rch & RM=Cow Branch,Main            ,4871
    1830    2350    2870
Boundary for River Rch & Prof#=Cow Branch,Main            , 1
Up Type= 0
Dn Type= 3
Dn Slope=0.00203
Boundary for River Rch & Prof#=Cow Branch,Main            , 2
Up Type= 0
Dn Type= 3
Dn Slope=0.00203
Boundary for River Rch & Prof#=Cow Branch,Main            , 3
Up Type= 0
Dn Type= 3
Dn Slope=0.00203
DSS Import GetInterval= 0
DSS Import GetPeak= 0
DSS Import FillOption= 0

--- DTL_Cow_Branch.g01 (geometry) ---

Geom Title=DTL_Cow_Branch
Program Version=4.00

River Reach=Cow Branch      ,Main
Reach XY= 30
2357196.36505805618793.3534543072357170.84945469619023.683495983
2356846.04271923619439.5188706222356997.04839176619965.940333858
2357200.50272346620365.6663136782357801.15382023620657.371725738
2358134.23588648621216.6461682622358131.47744285621619.378935754
2357796.32654391622091.0727935582357620.29726121623946.542990446
2358070.10207245624737.1098292472358017.00203291625663.257272303
2358354.22176458626365.2811717692358634.89340223629063.728636101
2358905.91048718629415.4301967622359082.45087838630355.369857848
2359270.71465501630607.7674484252359256.23282604631389.786212713
2359406.56800291631651.8383559292359278.98998582632496.611712411
2359387.25889762632613.1559550322359219.68344815632802.109342515
2359372.08745775633451.0332024692359089.34698743634043.408968329
2359242.44060794634280.6351190362359381.05239949635208.851394773
2359246.57827334635401.9424476772359312.09130916635686.751750723
2359171.41068494636459.8055732552359351.34257299637095.575231478

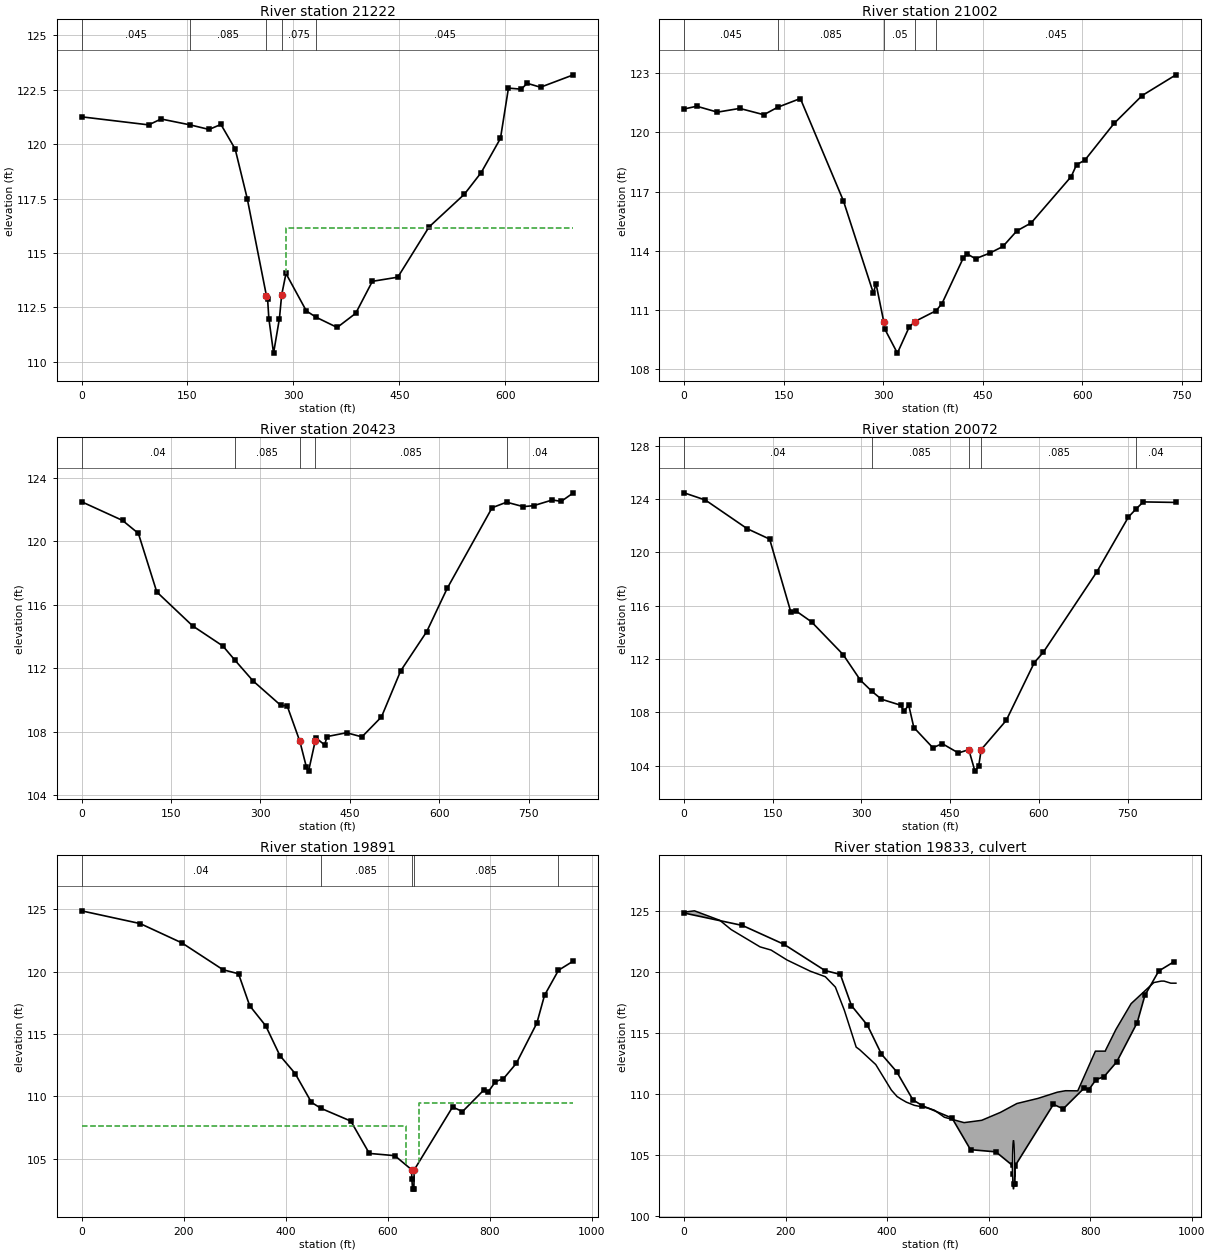
Type RM Length L Ch R = 1 ,21222   ,192.17,219.12,284.4
XS GIS Cut Line= 3
2356923.15454826618798.2531949432357196.36505805618793.353454307
 2357618.6284703618767.845009103
#Sta/Elev= 30
       0  121.26   95.05  120.89  112.63  121.16  154.02120.8876  180.56  120.68
  197.34  120.91  217.51  119.78  234.62   117.5  261.81  113.03  263.41  112.89
   265.2  111.99  271.85   110.4  280.17  111.99  283.32  113.07  289.42  114.06
  318.27  112.34  332.06  112.05  361.92  111.58  388.15  112.23  411.74   113.7
  447.73  113.89     492   116.2   541.9   117.7  565.82   118.7  593.07  120.27
  604.36  122.58  622.45  122.53  630.87   122.8  649.77  122.62  696.29  123.19
#Mann= 5 ,-1 , 0
       0    .045       0  154.02    .085       0  261.81     .05       0
  283.32    .075       0  332.06    .045       0
#XS Ineff= 2 , 0
       0                     290       0  116.13
Permanent Ineff=
       F       F
Bank Sta=261.81,283.32
XS Rating Curve= 0 ,0
Exp/Cntr=0.3,0.1

Type RM Length L Ch R = 1 ,21002   ,659.57,579.7,479.83
XS GIS Cut Line= 2
2356918.62293041618839.0377558082357539.61971966619243.651664098
#Sta/Elev= 30
       0  121.18   19.14  121.32   50.29  121.02   83.86  121.21  120.22  120.89
   141.2  121.27  175.24  121.71  240.13  116.53  285.22  111.86  289.29  112.33
  301.04  110.39  302.49  110.04  321.44  108.82  339.09  110.13  347.82  110.42
  379.86  110.97  388.67  111.33  420.64  113.63  426.64  113.84  439.18   113.6
  460.43  113.88  480.45  114.22  501.49  115.01     523  115.41  583.39  117.76
  591.48  118.36  603.94  118.59  647.98  120.45  690.23  121.86  741.18  122.91
#Mann= 5 ,-1 , 0
       0    .045       0   141.2    .085       0  301.04     .05       0
  347.82    .075       0  379.86    .045       0
Bank Sta=301.04,347.82
XS Rating Curve= 0 ,0
Exp/Cntr=0.3,0.1

Type RM Length L Ch R = 1 ,20423   ,360.53,351.06,308.98
XS GIS Cut Line= 3
2356469.42230764619496.8680160342357028.40934874 619456.25784637
2357286.40336767 619513.58985059
#Sta/Elev= 30
       0   122.5   68.73  121.32   95.37   120.5  126.19  116.81   186.3  114.67
  237.03   113.4  257.16  112.51   287.6   111.2  334.35  109.65  344.69  109.64
  366.08  107.39  377.18  105.75  380.71  105.51  391.67  107.38  393.78  107.59
  407.59  107.16   411.7  107.69  444.39  107.93  470.21  107.67  502.97  108.93
  535.12  111.83  578.87  114.31  613.08  117.03  688.45  122.12  712.75  122.47
  740.57  122.19  758.09  122.25  789.45  122.61  804.29  122.52  824.75  123.06
#Mann= 5 ,-1 , 0
       0     .04       0  257.16    .085       0  366.08     .05       0
  391.67    .085       0  712.75     .04       0
Bank Sta=366.08,391.67
XS Rating Curve= 0 ,0
Exp/Cntr=0.3,0.1

Type RM Length L Ch R = 1 ,20072   ,202.53,180.51,180.16
XS GIS Cut Line= 2
2356490.92180921619924.4692141412357291.18103468619697.530030772
#Sta/Elev= 30
       0  124.46   36.04  123.92  106.81  121.77  144.73  120.99  180.48  115.54
  189.83  115.59  215.52  114.79  268.92  112.34  298.33  110.41  317.67  109.58
  333.82  108.99  366.32  108.54  371.91  108.08  379.92  108.55  388.57  106.87
  420.77  105.35  436.59  105.66  463.94  104.96  481.48  105.21  491.89   103.6
  498.21  103.97  502.59  105.22  544.79   107.4  592.38  111.74  607.53  112.51
   698.4  118.56  751.52  122.65  763.94  123.23  776.58  123.78  831.81  123.74
#Mann= 5 ,-1 , 0
       0     .04       0  317.67    .085       0  481.48     .05       0
  502.59    .085       0  763.94     .04       0
Bank Sta=481.48,502.59
XS Rating Curve= 0 ,0
Exp/Cntr=0.5,0.3

Type RM Length L Ch R = 1 ,19891   ,118.39,117.2,113.24
BEGIN DESCRIPTION:
Surveyed Section
END DESCRIPTION:
XS GIS Cut Line= 6
2356372.47931616620107.1970738922356741.34705006 620072.83266075
2356848.91905379620041.6933965092357030.57960002619934.617100015
2357226.83648804619932.7059716582357294.77670096619910.059234023
#Sta/Elev= 30
       0  124.86  114.94  123.84   196.9  122.29  277.54  120.14  307.86  119.82
  329.77  117.26  361.21  115.65  388.94  113.27  418.85  111.83  450.86  109.52
   469.6  109.04     528  108.02 564.345  105.43  614.32  105.25 647.165  104.13
  647.65  103.42  649.16  102.57  651.72  102.61 652.319  104.11  727.67  109.15
  747.02  108.78  788.64   110.5  797.44  110.36  811.73  111.18  827.43  111.42
  852.48  112.64  892.85  115.87  907.84  118.09  935.24   120.1  964.47  120.84
#Mann= 5 ,-1 , 0
       0     .04       0   469.6    .085       0 647.165     .05       0
 652.319    .085       0  935.24     .04       0
#XS Ineff= 2 , 0
       0     637  107.65     661       0   109.5
Permanent Ineff=
       F       F
Bank Sta=647.165,652.319
XS Rating Curve= 0 ,0
Exp/Cntr=0.5,0.3

Type RM Length L Ch R = 2 ,19833   ,,,
BEGIN DESCRIPTION:
Shine Road (+/- 0.25 mi)
END DESCRIPTION:
Bridge Culvert--1,0,-1,-1, 0
Deck Dist Width WeirC Skew NumUp NumDn MinLoCord MaxHiCord MaxSubmerge Is_Ogee
51.5,9.5,2.6,0, 41, 41, , , 0.98, 0, 1,1,,
       0    20.5   70.48    92.8  149.74  171.38  202.98  248.86  278.33  298.11
  315.76   339.1  345.92  377.64  408.46  419.96   421.3  427.15  438.06  453.72
   480.3  493.23  512.96 551.643 586.353 623.208 655.754 697.254 735.415  751.47
  775.64  810.39  830.06  830.63  850.82  880.75   925.5  940.02   945.7  958.93
  969.06
  124.93  125.04  124.26   123.5  122.08  121.82     121  120.08  119.63  118.78
  116.88  113.85  113.64  112.42  110.32  109.78  109.75  109.59  109.33  109.07
  108.85  108.67  108.09  107.65  107.84  108.49  109.22  109.64  110.15  110.27
  110.26  113.52  113.52  113.61   115.3  117.42  119.15  119.27  119.27   119.1
   119.1
                                                                                
                                                                                
                                                                                
                                                                                
        
       0    20.5   70.48    92.8  149.74  171.38  202.98  248.86  278.33  298.11
  315.76   339.1  345.92  377.64  408.46  419.96   421.3  427.15  438.06  453.72
   480.3  493.23  512.96 551.643 586.353 623.208 655.754 697.254 735.415  751.47
  775.64  810.39  830.06  830.63  850.82  880.75   925.5  940.02   945.7  958.93
  969.06
  124.93  125.04  124.26   123.5  122.08  121.82     121  120.08  119.63  118.78
  116.88  113.85  113.64  112.42  110.32  109.78  109.75  109.59  109.33  109.07
  108.85  108.67  108.09  107.65  107.84  108.49  109.22  109.64  110.15  110.27
  110.26  113.52  113.52  113.61   115.3  117.42  119.15  119.27  119.27   119.1
   119.1
                                                                                
                                                                                
                                                                                
                                                                                
        
BR Coef= 1 , 1 , 0 ,1.25, 0 ,,,0.8,0,2,0,
WSPro=,,,, 1 ,,,, 0 ,,,, 0 ,,,,-1 ,-1 ,-1 , 0 , 0 , 0 , 0 , 0
Culvert=1,4,,21,0.024,0.5,1,2,1,102.19,649,102,657,Culvert #1  , 0 ,46.5
Culvert Bottom n=0.024
BC Design=,, 0 ,, 0 ,,,,,,
BC Use User HTab Curves=0
BC User HTab FreeFlow(D)= 0

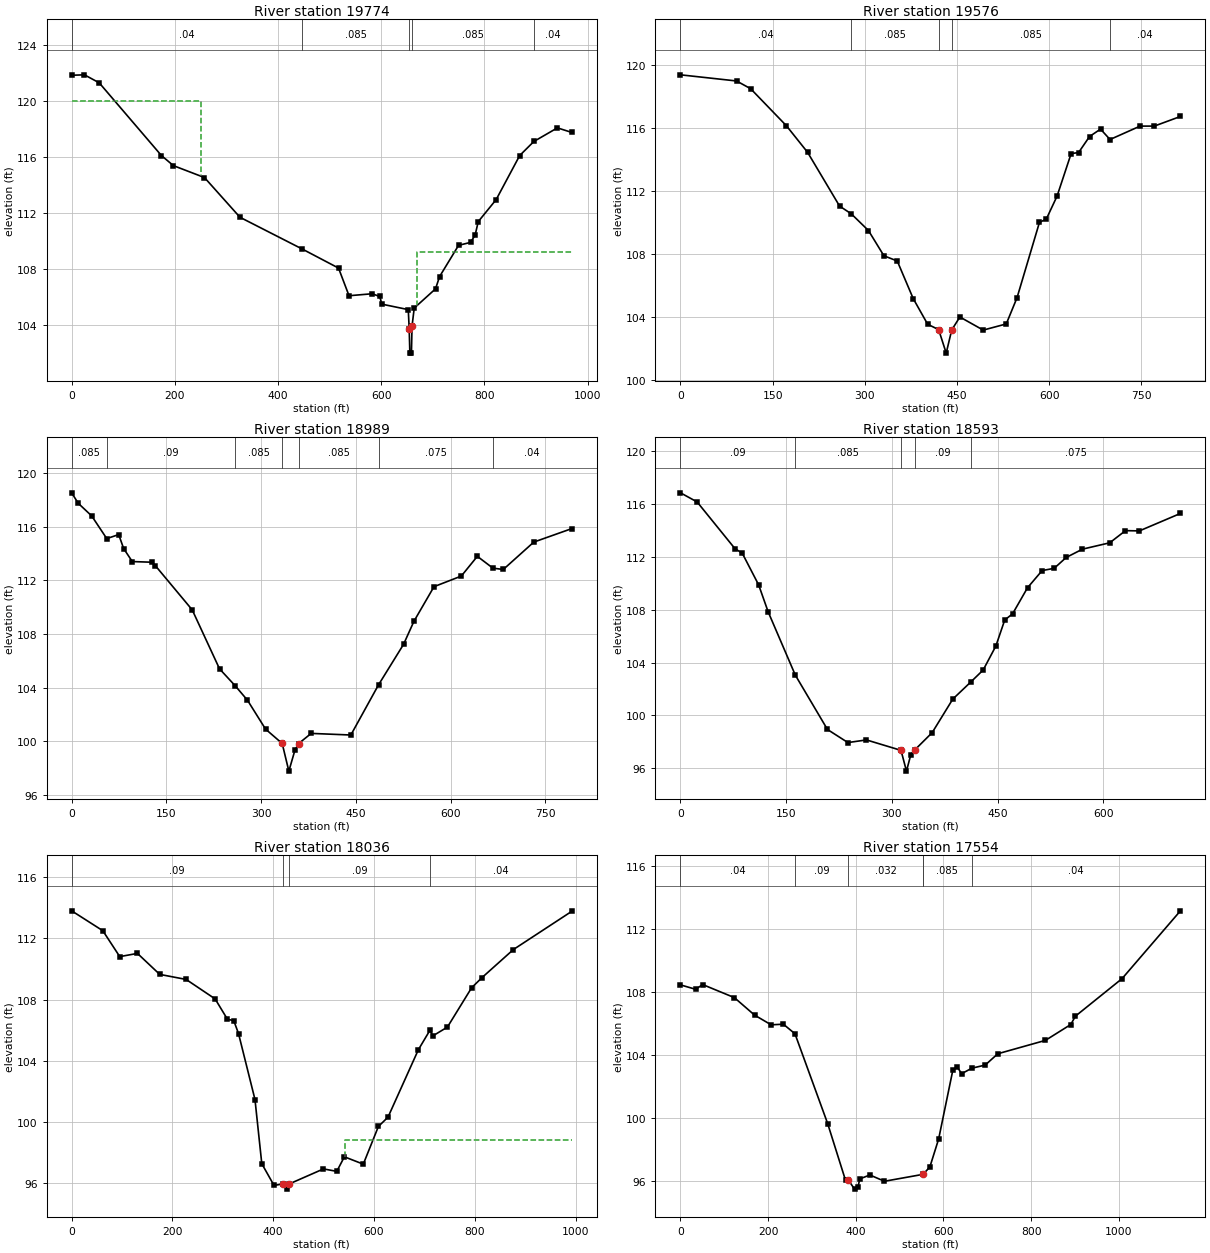
Type RM Length L Ch R = 1 ,19774   ,177.31,198.18,159.52
BEGIN DESCRIPTION:
Surveyed Section
END DESCRIPTION:
XS GIS Cut Line= 6
2356422.34105623620216.2696302092356763.99378772620183.235506698
2357006.96910001620098.007499993    2357089.8928620035.837700009
2357245.23696235620038.8625543122357345.82203303619999.163303822
#Sta/Elev= 30
       0  121.83   24.81  121.86   53.41  121.29  173.97  116.11  197.22  115.39
  257.43  114.54  326.26  111.71  447.03109.4455  517.29  108.09  537.65  106.12
  582.43  106.26  597.02  106.07 601.262  105.52  652.48  105.13 654.257  103.78
  655.55  102.06  658.62  102.03 659.768  103.95 664.015  105.24 705.303  106.61
  713.25  107.49  749.99  109.71  773.13  109.92  782.09  110.44  788.11   111.4
  822.87  112.97  868.49  116.11  895.89  117.11  941.54  118.08  969.06  117.76
#Mann= 5 ,-1 , 0
       0     .04       0  447.03    .085       0 654.257     .05       0
 659.768    .085       0  895.89     .04       0
#XS Ineff= 3 ,-1
       0     250     120                             669    1000  109.22
Permanent Ineff=
       F       F       F
Bank Sta=654.257,659.768
XS Rating Curve= 0 ,0
Exp/Cntr=0.5,0.3

Type RM Length L Ch R = 1 ,19576   ,640.72,586.72,499.22
XS GIS Cut Line= 4
2356714.70012614620404.7117306292357054.86282416620270.814687401
2357222.94408005620189.4279740452357421.63251424620019.524211496
#Sta/Elev= 30
       0  119.37   91.29  118.98  114.18  118.49  172.44  116.14  206.85  114.46
  258.96  111.05  277.97  110.56  305.95   109.5  331.12   107.9  352.83  107.57
  378.76  105.19  402.31  103.56  420.21  103.22   432.5  101.73  441.49   103.2
  454.76  104.02  492.77  103.19  530.26  103.58  547.86  105.25   584.3  110.02
  595.36  110.22  612.94  111.68  635.88  114.38  647.92  114.44  665.84  115.46
   683.7  115.93  699.17  115.27  748.12  116.12  771.23  116.12  813.74  116.73
#Mann= 5 ,-1 , 0
       0     .04       0  277.97    .085       0  420.21     .05       0
  441.49    .085       0  699.17     .04       0
Bank Sta=420.21,441.49
XS Rating Curve= 0 ,0
Exp/Cntr=0.3,0.1

Type RM Length L Ch R = 1 ,18989   ,327.46,396.49,414.11
XS GIS Cut Line= 2
2357374.05052654620882.7974161652357768.30128142620196.257308528
#Sta/Elev= 30
       0  118.52   10.43  117.74   31.72   116.8   55.58  115.11   74.47  115.41
   82.34  114.37   95.99   113.4  127.43  113.35   132.6  113.09  190.93   109.8
  234.15  105.41  259.12  104.14  278.43  103.07  307.05  100.92   333.4   99.85
  343.94   97.79  353.44   99.33  359.32   99.84  379.35   100.6  442.12  100.48
   486.1  104.23  525.55  107.23  542.03  108.95  573.81  111.53  617.06  112.32
  642.43  113.79  667.08  112.91  683.51  112.81  731.82  114.85  791.69  115.85
#Mann= 7 ,-1 , 0
       0    .085       0   55.58     .09       0  259.12    .085       0
   333.4     .05       0  359.32    .085       0   486.1    .075       0
  667.08     .04       0
Bank Sta=333.4,359.32
XS Rating Curve= 0 ,0
Exp/Cntr=0.3,0.1

Type RM Length L Ch R = 1 ,18593   ,503.87,557.1,581.5
XS GIS Cut Line= 3
2357616.49208273620980.2272004042358096.96661048620565.620363787
2358128.56490226620497.609897017
#Sta/Elev= 30
       0  116.84   23.61  116.15   77.26  112.62   87.69  112.27  110.92  109.88
  124.43  107.84     163  103.05  208.61   98.94  237.62   97.95     264   98.15
  313.02   97.36  320.76   95.79  326.95   97.04  332.65    97.4  357.22    98.7
  386.53  101.24  412.43  102.55  429.66  103.44  447.63  105.25  460.23  107.22
  471.41  107.69  492.58  109.66  513.34  110.96  530.45  111.13  547.43  111.95
  570.61  112.58  609.28  113.06  631.66  113.98  651.36  113.96  709.62  115.28
#Mann= 5 ,-1 , 0
       0     .09       0     163    .085       0  313.02     .05       0
  332.65     .09       0  412.43    .075       0
Bank Sta=313.02,332.65
XS Rating Curve= 0 ,0
Exp/Cntr=0.3,0.1

Type RM Length L Ch R = 1 ,18036   ,428.91,481.31,555.96
XS GIS Cut Line= 4
2357720.71929379 621209.073902952358017.34917347621253.426555529
2358563.61325505621111.8844453392358690.48551844621127.504781261
#Sta/Elev= 30
       0  113.79   61.86  112.49   95.44   110.8  130.53  111.01  174.75  109.64
  227.16  109.31  284.66  108.04  309.15  106.71  321.68  106.62  331.17  105.77
  363.78  101.47   377.3   97.28  401.59   95.86   419.1   95.96  428.23   95.62
  431.15   95.95   499.7   96.94  526.08   96.78   541.2   97.73   578.7   97.25
  608.69   99.71  627.77  100.32  687.98  104.72  710.91  105.99  717.01  105.63
  745.68   106.2  793.74  108.77  814.28  109.43  876.48  111.26  992.06  113.75
#Mann= 4 ,-1 , 0
       0     .09       0   419.1     .05       0  431.15     .09       0
  710.91     .04       0
#XS Ineff= 2 , 0
                          542.89           98.84
Permanent Ineff=
       F       F
Bank Sta=419.1,431.15
XS Rating Curve= 0 ,0
Exp/Cntr=0.3,0.1

Type RM Length L Ch R = 1 ,17554   ,327.39,332.4,326.96
XS GIS Cut Line= 5
2357656.33241129621524.0474019942358032.42764585 621657.39025788
2358206.79907276621751.4140665232358263.21335797 621831.76168482
2358548.70383145622173.666443512
#Sta/Elev= 30
       0  108.45    34.5  108.17   50.65  108.47  122.92  107.64   168.9  106.53
  206.91  105.91  234.78  105.95  261.23  105.34   335.8   99.63  376.67   96.01
  382.65   96.06  397.05   95.46  404.99    95.6  409.15   96.11  432.07   96.36
  465.45   95.96  553.49    96.4  569.02   96.87  589.06   98.65  621.38  103.02
  631.29  103.24  641.51   102.8  664.59  103.15  695.31  103.35  724.04  104.07
  832.64  104.92  890.58  105.93  901.13  106.46 1007.65  108.85 1140.74  113.16
#Mann= 6 ,-1 , 0
       0     .04       0  261.23     .09       0  382.65    .032       0
  553.49    .032       0  553.49    .085       0  664.59     .04       0
Bank Sta=382.65,553.49
XS Rating Curve= 0 ,0
Exp/Cntr=0.3,0.1

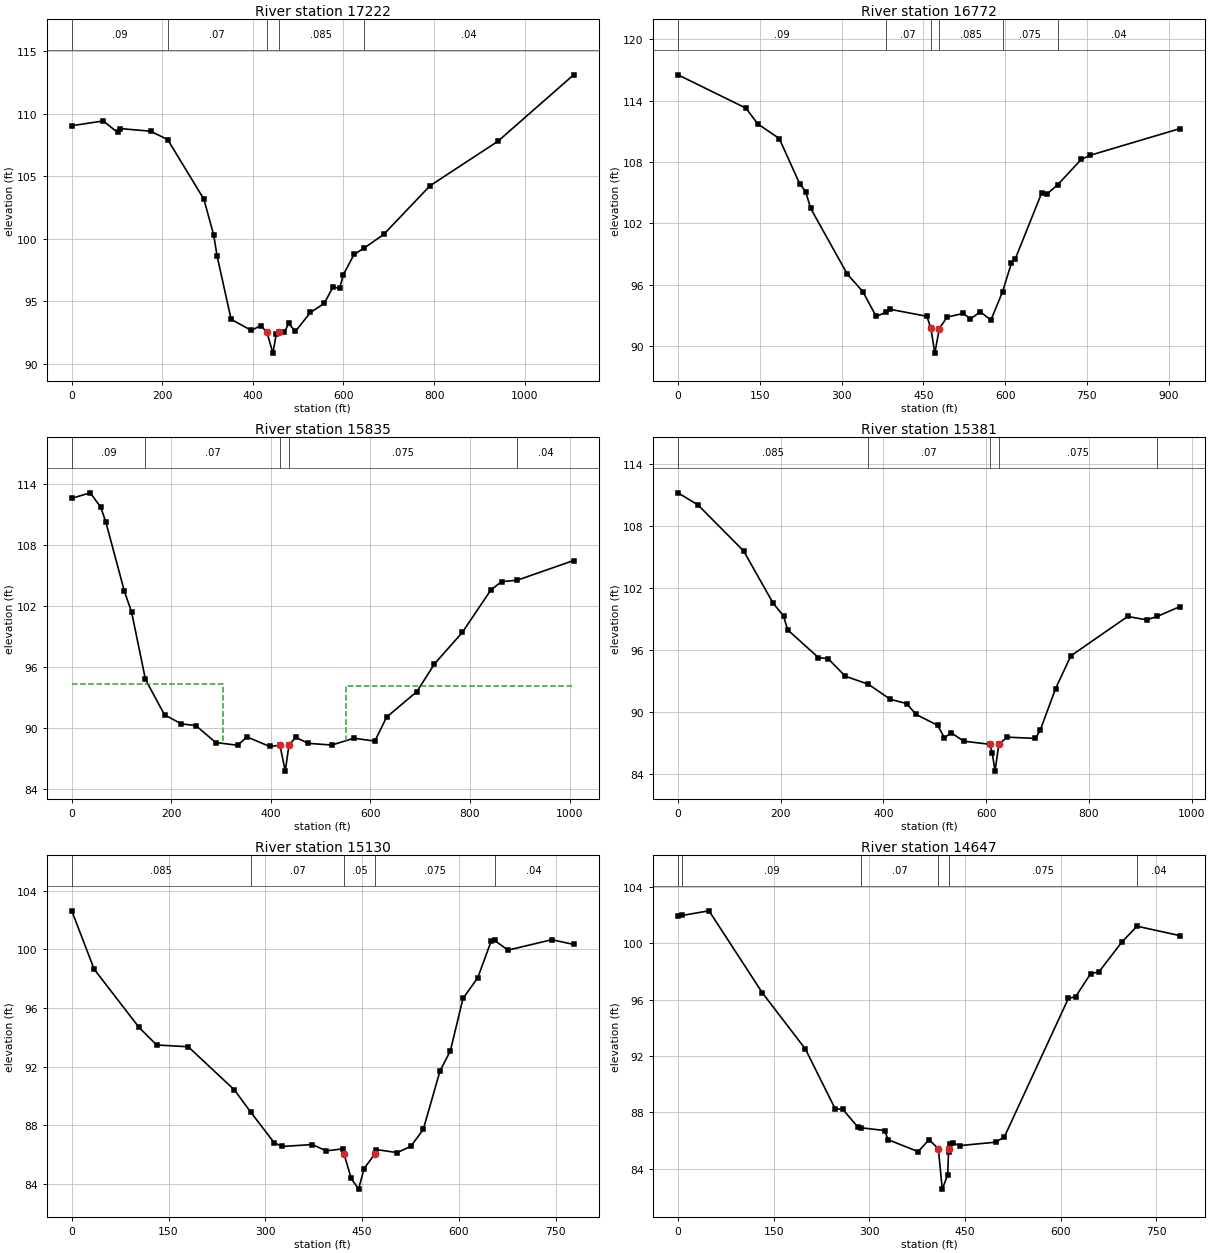
Type RM Length L Ch R = 1 ,17222   ,463.99,449.68,376.16
XS GIS Cut Line= 4
2357580.23913975621650.9066455072357764.03241029621877.918827251
2358076.87526447622052.2902541612358497.41811764622233.499776289
#Sta/Elev= 30
       0  109.03   69.58  109.41  101.32  108.49  107.27   108.8  174.06  108.59
  211.77  107.92  291.76  103.15  313.26   100.3  321.08   98.58  351.85   93.54
  396.57   92.66  417.39   93.04  430.97    92.5  444.17   90.84   451.6   92.39
  456.51   92.51  469.66   92.52  479.05   93.22  493.54   92.57     527   94.09
  557.22   94.81  576.76   96.12  591.65   96.03  599.79   97.12   623.2   98.73
  645.17   99.23  688.92  100.34  790.86  104.22  940.78  107.78 1108.17   113.1
#Mann= 5 ,-1 , 0
       0     .09       0  211.77     .07       0  430.97     .05       0
  456.51    .085       0  645.17     .04       0
Bank Sta=430.97,456.51
XS Rating Curve= 0 ,0
Exp/Cntr=0.3,0.1

Type RM Length L Ch R = 1 ,16772   ,888.26,937.15,954.21
XS GIS Cut Line= 4
2357312.87368526622321.5860905652357400.31403689 622348.16631408
2358015.13757804622361.4358869052358214.66564184622439.408155248
#Sta/Elev= 30
       0  116.54  124.61  113.28  146.33  111.74   185.7  110.31  222.93  105.91
  234.29  105.09  243.39  103.47  310.44   97.06  339.08   95.33   363.5   92.91
  380.66    93.3  389.74    93.6  456.55   92.92  463.84   91.75  471.01   89.32
  479.35   91.72  493.38   92.84     523    93.2  536.41   92.67  554.54   93.36
  573.99   92.55  595.25   95.32  611.51   98.12  618.35    98.5  667.01  104.98
  677.06  104.89  696.79  105.81   739.6  108.26  756.03  108.67  920.58  111.28
#Mann= 6 ,-1 , 0
       0     .09       0  380.66     .07       0  463.84     .05       0
  479.35    .085       0  595.25    .075       0  696.79     .04       0
Bank Sta=463.84,479.35
XS Rating Curve= 0 ,0
Exp/Cntr=0.3,0.1

Type RM Length L Ch R = 1 ,15835   ,522.22,454.33,406.03
XS GIS Cut Line= 3
2357236.65597196623086.8392016742357979.75205052623394.250972256
2358182.94431672623413.705997765
#Sta/Elev= 30
       0  112.63   37.13  113.17   58.12  111.76   68.46  110.29  105.79  103.46
  120.29   101.4  148.02   94.78  186.38   91.29  220.05    90.4  249.27   90.23
  289.21   88.56  333.21   88.29  352.11   89.11  397.64   88.17  418.27   88.28
  428.97   85.74  436.27   88.28  449.77   89.07  475.06   88.48  522.39   88.31
   566.6   88.98  608.97    88.7  632.45   91.06  693.37   93.58  728.71   96.31
  784.62   99.41  841.92  103.59   863.5  104.42  894.56104.5502 1008.29   106.5
#Mann= 5 ,-1 , 0
       0     .09       0  148.02     .07       0  418.27     .05       0
  436.27    .075       0  894.56     .04       0
#XS Ineff= 2 , 0
       0  304.41   94.33     550       0   94.17
Permanent Ineff=
       F       F
Bank Sta=418.27,436.27
XS Rating Curve= 0 ,0
Exp/Cntr=0.3,0.1

Type RM Length L Ch R = 1 ,15381   ,302.42,250.27,224.88
XS GIS Cut Line= 2
2356995.66043423623753.5773382042357968.69407314623664.065619811
#Sta/Elev= 30
       0  111.19   38.85  110.02  127.75  105.56  184.94  100.52  205.43   99.25
  213.58   97.91  273.33   95.23  292.39   95.12  325.53   93.43  370.83   92.64
   413.3   91.19  445.42   90.77  463.45   89.72  505.47   88.67  518.75   87.45
  531.52   87.95  556.45   87.13  607.02   86.83  611.86   85.97  617.21   84.23
  624.63   86.84  640.92   87.52     696    87.4  705.35   88.21  735.13   92.23
  764.91    95.4  875.39   99.21  912.34   98.89  933.37   99.22  977.14  100.17
#Mann= 5 ,-1 , 0
       0    .085       0  370.83     .07       0  607.02     .05       0
  624.63    .075       0  933.37     .04       0
Bank Sta=607.02,624.63
XS Rating Curve= 0 ,0
Exp/Cntr=0.3,0.1

Type RM Length L Ch R = 1 ,15130   ,487.01,482.95,459.61
BEGIN DESCRIPTION:
Surveyed Section
END DESCRIPTION:
XS GIS Cut Line= 6
2357263.02588867624179.549418181    2357575.2142     623970.7984
2357590.04310003623958.7134000212357624.45680003623945.982900009
2357682.54650003623920.2750999932357945.03437845623814.754179463
#Sta/Elev= 30
       0  102.63    34.7   98.65  104.29   94.68  131.62   93.48  180.61   93.36
  252.29   90.41  277.63   88.89  313.87   86.81  326.37   86.56     373   86.69
 394.625   86.26 420.579    86.4 421.963   86.07  433.25   84.38  444.66   83.65
  453.21   85.05 470.049   86.06 471.912   86.35  504.37   86.14  525.52   86.56
  544.97   87.72  570.98   91.72  586.92   93.07  606.61   96.66  629.51   98.07
  650.51   100.6  655.48  100.61  676.43   99.95  744.25  100.66  778.11  100.34
#Mann= 5 ,-1 , 0
       0    .085       0  277.63     .07       0 421.963     .05       0
 470.049    .075       0  655.48     .04       0
Bank Sta=421.963,470.049
XS Rating Curve= 0 ,0
Exp/Cntr=0.3,0.1

Type RM Length L Ch R = 1 ,14647   ,405.39,460.85,500.41
XS GIS Cut Line= 2
2357575.70752187 624551.142083692358228.26049545624111.575150087
#Sta/Elev= 30
       0  101.96    5.98  101.97   48.59   102.3  132.25   96.48  199.59    92.5
   246.4   88.25  258.43   88.21  281.91   86.95  287.65    86.9  323.85   86.71
  329.34   86.06  376.45   85.21   393.5   86.06  408.15   85.42  414.25   82.55
   422.8   83.56  424.11   85.21  424.93   85.42  426.28   85.74  430.63   85.83
  442.08   85.64  497.94   85.88  511.55   86.25  611.94   96.08  623.38   96.21
  646.77   97.83  659.97   97.97  695.59  100.07   719.6  101.21  786.79  100.54
#Mann= 6 ,-1 , 0
       0    .045       0    5.98     .09       0  287.65     .07       0
  408.15     .05       0  424.93    .075       0   719.6     .04       0
Bank Sta=408.15,424.93
XS Rating Curve= 0 ,0
Exp/Cntr=0.3,0.1

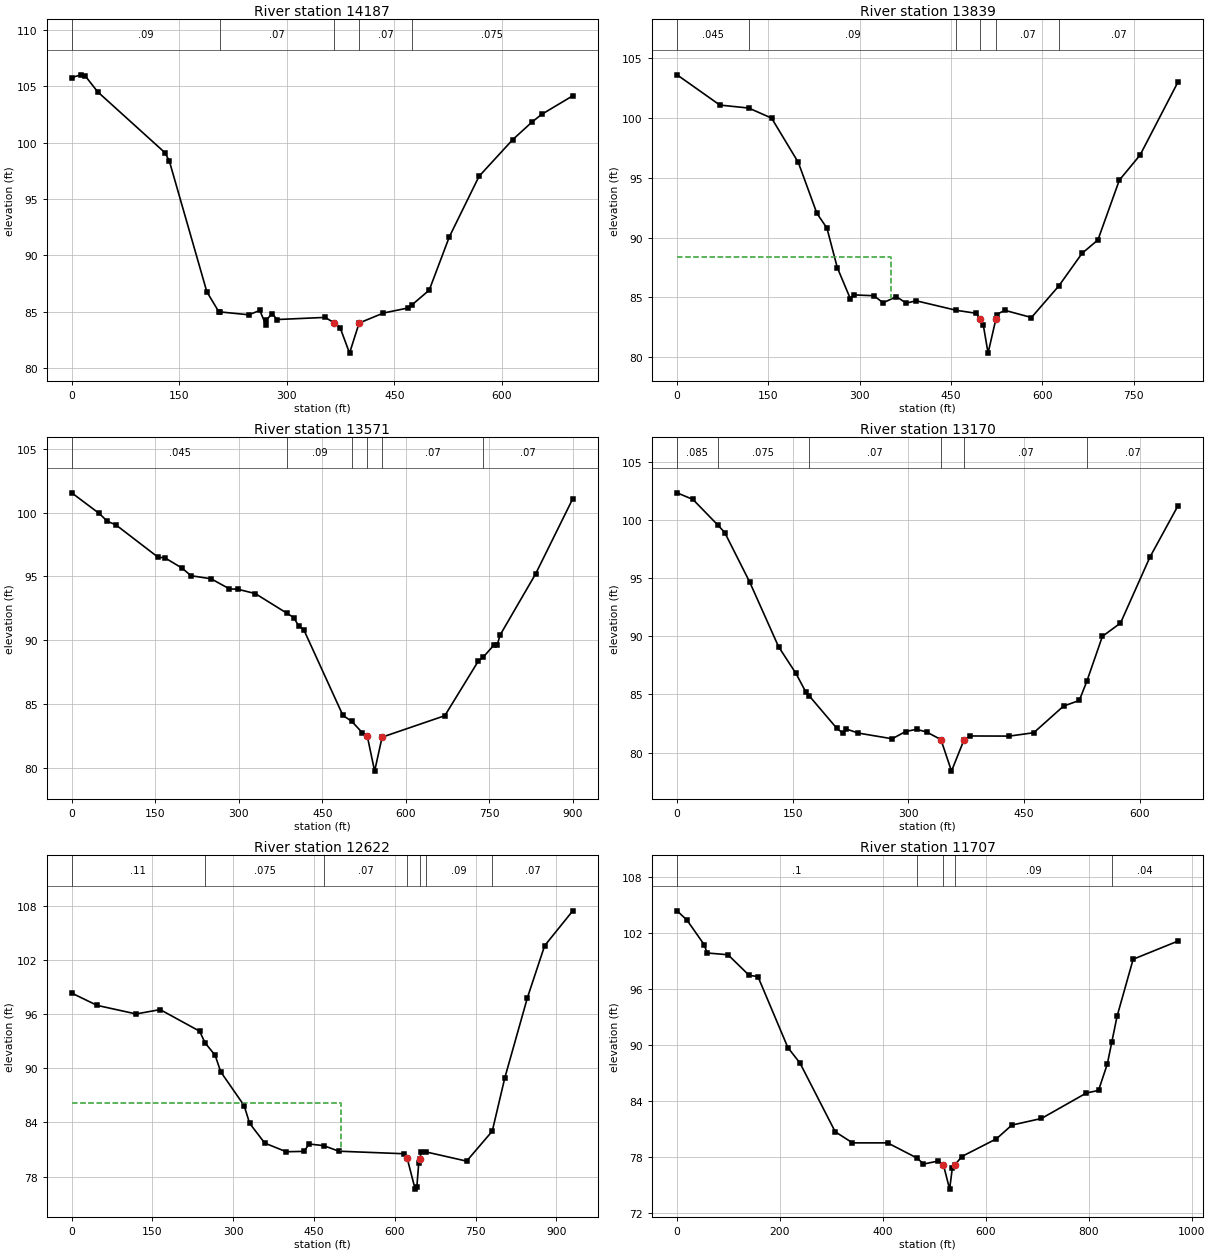
Type RM Length L Ch R = 1 ,14187   ,314.04,347.35,332.7
XS GIS Cut Line= 3
2357695.79539549624795.8494487852358246.69365878624721.119801164
2358389.13292992624730.140989661
#Sta/Elev= 30
       0  105.78   13.02  106.02   18.85  105.92   36.24  104.51  129.85   99.12
  136.03   98.39  188.42   86.77  204.99   85.01  206.46   84.99  247.09   84.73
  262.24   85.12   270.9   83.81  271.33   84.27  279.51   84.84   286.2   84.31
  353.38    84.5  365.95   84.02  374.17    83.6  387.41   81.33  400.74      84
  434.73   84.89  468.75   85.33  474.26    85.6  498.51   86.92  526.49   91.64
     568   97.02  615.06  100.28  641.64  101.82  655.23  102.51  698.67  104.16
#Mann= 5 ,-1 , 0
       0     .09       0  206.46     .07       0  365.95     .05       0
  400.74     .07       0  474.26    .075       0
Bank Sta=365.95,400.74
XS Rating Curve= 0 ,0
Exp/Cntr=0.3,0.1

Type RM Length L Ch R = 1 ,13839   ,244.35,268.35,241.54
XS GIS Cut Line= 3
2357537.18876992625006.5696798562357800.02260654 625083.60718368
2358348.34836906 625058.68328537
#Sta/Elev= 30
       0  103.62   70.31  101.09  117.74  100.84  155.18     100  199.12   96.29
  229.64   92.03  246.09    90.8  263.06    87.5  284.55   84.89  291.09   85.21
  323.35   85.14  338.18   84.55  360.31   85.06  376.23   84.52   392.5   84.72
  458.69   83.92  491.67   83.67  497.58   83.17  502.81   82.71  510.69   80.34
  523.51   83.18  524.65   83.57  538.15   83.92  581.95   83.32  626.88   85.96
  665.08   88.69  691.08   89.81  726.26   94.81  760.33   96.91  822.78  103.04
#Mann= 6 ,-1 , 0
       0    .045       0  117.74     .09       0  458.69     .07       0
  497.58     .05       0  523.51     .07       0  626.88     .07       0
#XS Ineff= 2 , 0
       0  350.49   88.42               0
Permanent Ineff=
       F       F
Bank Sta=497.58,523.51
XS Rating Curve= 0 ,0
Exp/Cntr=0.3,0.1

Type RM Length L Ch R = 1 ,13571   ,412.23,401,383.98
XS GIS Cut Line= 4
2357496.40420906 625369.099109652357958.62923205625319.251313031
2358264.51343843625303.3906504962358389.13292992625335.111975595
#Sta/Elev= 30
       0  101.55   49.19   99.94   64.05   99.32   79.34   99.04  154.68   96.52
  167.76   96.45  197.98   95.66  214.22   95.06  250.27   94.82  283.17   94.03
  298.37      94   329.7   93.66  386.91   92.11  398.69   91.78  407.45   91.14
  416.74   90.83  487.05   84.12  502.89 83.6593  521.55   82.78  530.64   82.53
  543.94   79.76  557.37   82.42     670    84.1   729.8   88.35  739.27    88.7
  758.63   89.65  764.11   89.64  769.22   90.41  833.02    95.2  899.79  101.09
#Mann= 6 ,-1 , 0
       0    .045       0  386.91     .09       0  502.89     .07       0
  530.64     .05       0  557.37     .07       0  739.27     .07       0
Bank Sta=530.64,557.37
XS Rating Curve= 0 ,0
Exp/Cntr=0.3,0.1

Type RM Length L Ch R = 1 ,13170   ,520.23,547.71,497.82
XS GIS Cut Line= 3
2357679.93473293625776.9447181522358057.15789197  625698.7334539
2358321.15866186625684.046551749
#Sta/Elev= 30
       0  102.31   20.62  101.74   52.56   99.56   61.79    98.9   94.12   94.65
   131.6   89.09  154.07    86.8  166.75   85.22  171.05   84.89  206.83    82.1
  215.07   81.65  219.01   82.03  234.78   81.67   278.9   81.18  296.24    81.8
  310.49   81.99  323.61   81.76  342.13   81.11  355.82    78.4  372.07   81.09
   380.4   81.42  430.89   81.41  462.46    81.7  501.14   83.99  521.51   84.47
  531.29   86.12  551.48   89.98  574.94   91.12  613.05   96.78  649.65  101.22
#Mann= 6 ,-1 , 0
       0    .085       0   52.56    .075       0  171.05     .07       0
  342.13     .05       0  372.07     .07       0  531.29     .07       0
Bank Sta=342.13,372.07
XS Rating Curve= 0 ,0
Exp/Cntr=0.3,0.1

Type RM Length L Ch R = 1 ,12622   ,856.5,914.86,873.59
XS GIS Cut Line= 3
2357650.47921677626277.6884930132357820.51717649626295.864231274
2358545.47374652626069.234070882
#Sta/Elev= 30
       0   98.33   47.07   96.97  119.48   96.02  164.26    96.5  237.52   94.11
  247.72   92.81   266.3   91.45  276.74   89.61  320.12   85.88  330.41   83.91
  358.46   81.72   398.4   80.76  431.62    80.8  440.77   81.62  468.35   81.43
  495.94   80.82   616.5   80.54  623.01   80.04  637.77   76.62  641.04   76.91
  644.39   79.46  646.37   79.97  649.35   80.74  657.26   80.75   733.4   79.72
  781.02   83.04   804.4   88.96  846.42   97.84  878.34  103.58  930.56  107.44
#Mann= 7 ,-1 , 0
       0     .11       0  247.72    .075       0  468.35     .07       0
  623.01     .05       0  646.37     .07       0  657.26     .09       0
  781.02     .07       0
#XS Ineff= 2 , 0
       0     500    86.2               0
Permanent Ineff=
       F       F
Bank Sta=623.01,646.37
XS Rating Curve= 0 ,0
Exp/Cntr=0.3,0.1

Type RM Length L Ch R = 1 ,11707   ,618.83,637,615.41
XS GIS Cut Line= 2
2357915.61578178627103.0965784942358871.02502561626915.110963404
#Sta/Elev= 30
       0  104.36   19.21  103.37   52.57  100.75   58.45   99.85   98.99   99.66
  140.18   97.45   157.1   97.33  215.32   89.73  238.87   88.07  307.32   80.72
  340.93   79.53  409.08   79.53   466.9   77.89  478.73   77.26  507.09   77.58
   517.5    77.2  529.69   74.58  534.97   76.86   540.4    77.2  553.34   78.07
  620.58   79.96  650.55   81.43   708.1   82.14   795.6   84.87  819.03   85.14
  836.11   87.96  844.71   90.28  855.19    93.1  886.34   99.18  973.73  101.13
#Mann= 5 ,-1 , 0
       0      .1       0   466.9     .07       0   517.5     .05       0
   540.4     .09       0  844.71     .04       0
Bank Sta=517.5,540.4
XS Rating Curve= 0 ,0
Exp/Cntr=0.3,0.1