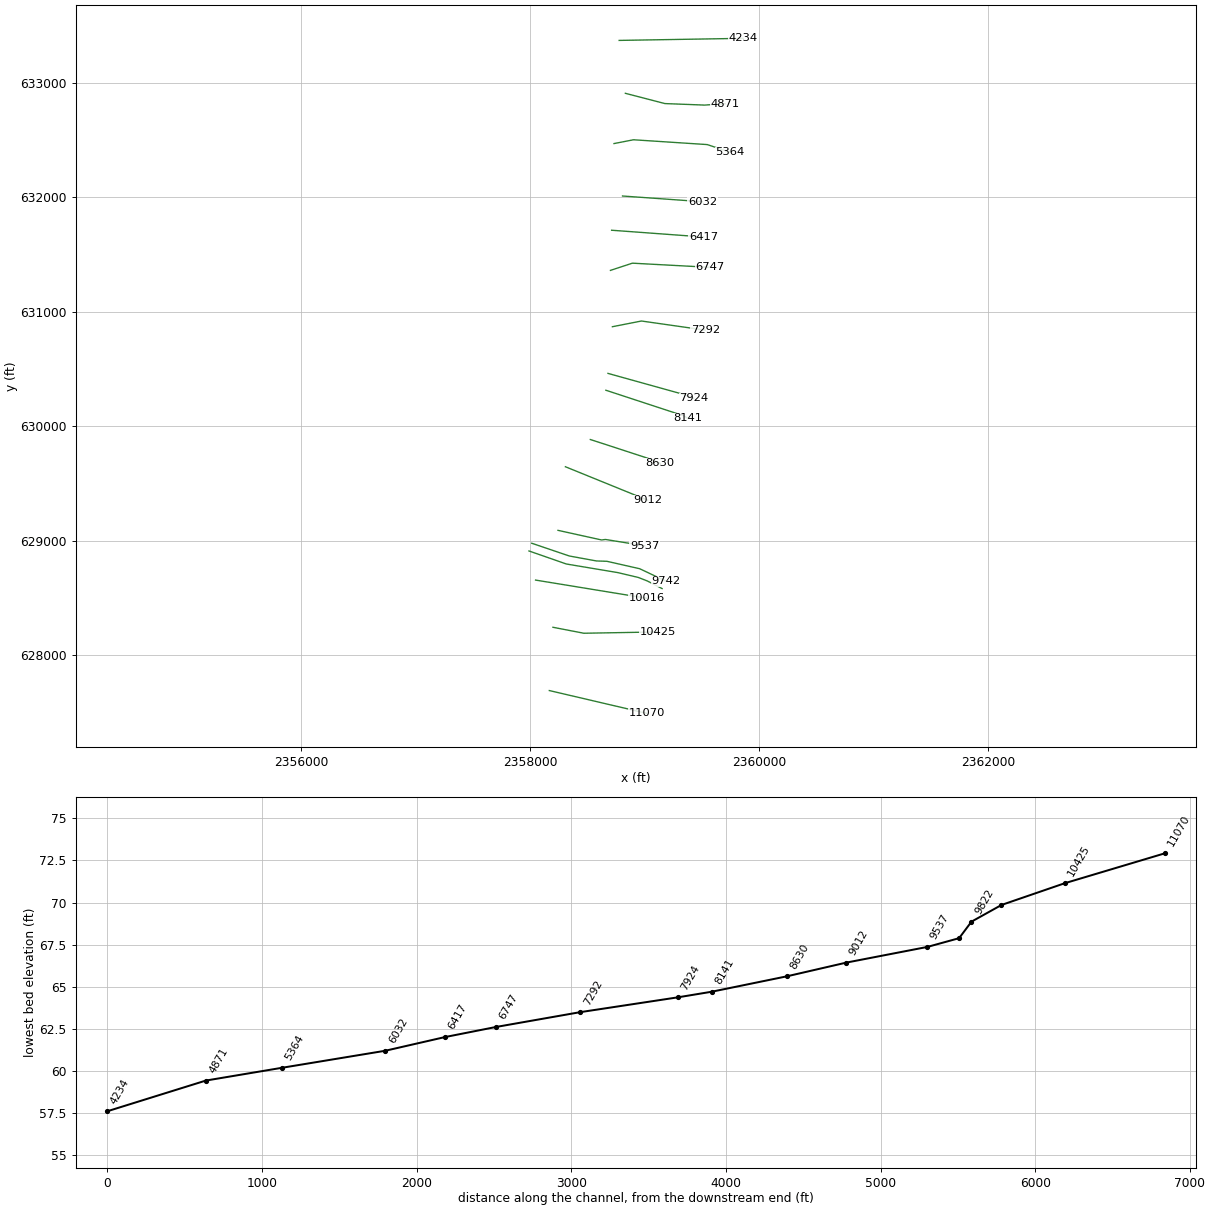
HEC-RAS study DTL_Cow_Branch.prj: DTL_Cow_Branch

--- DTL_Cow_Branch.g01 (geometry) --- (continued)

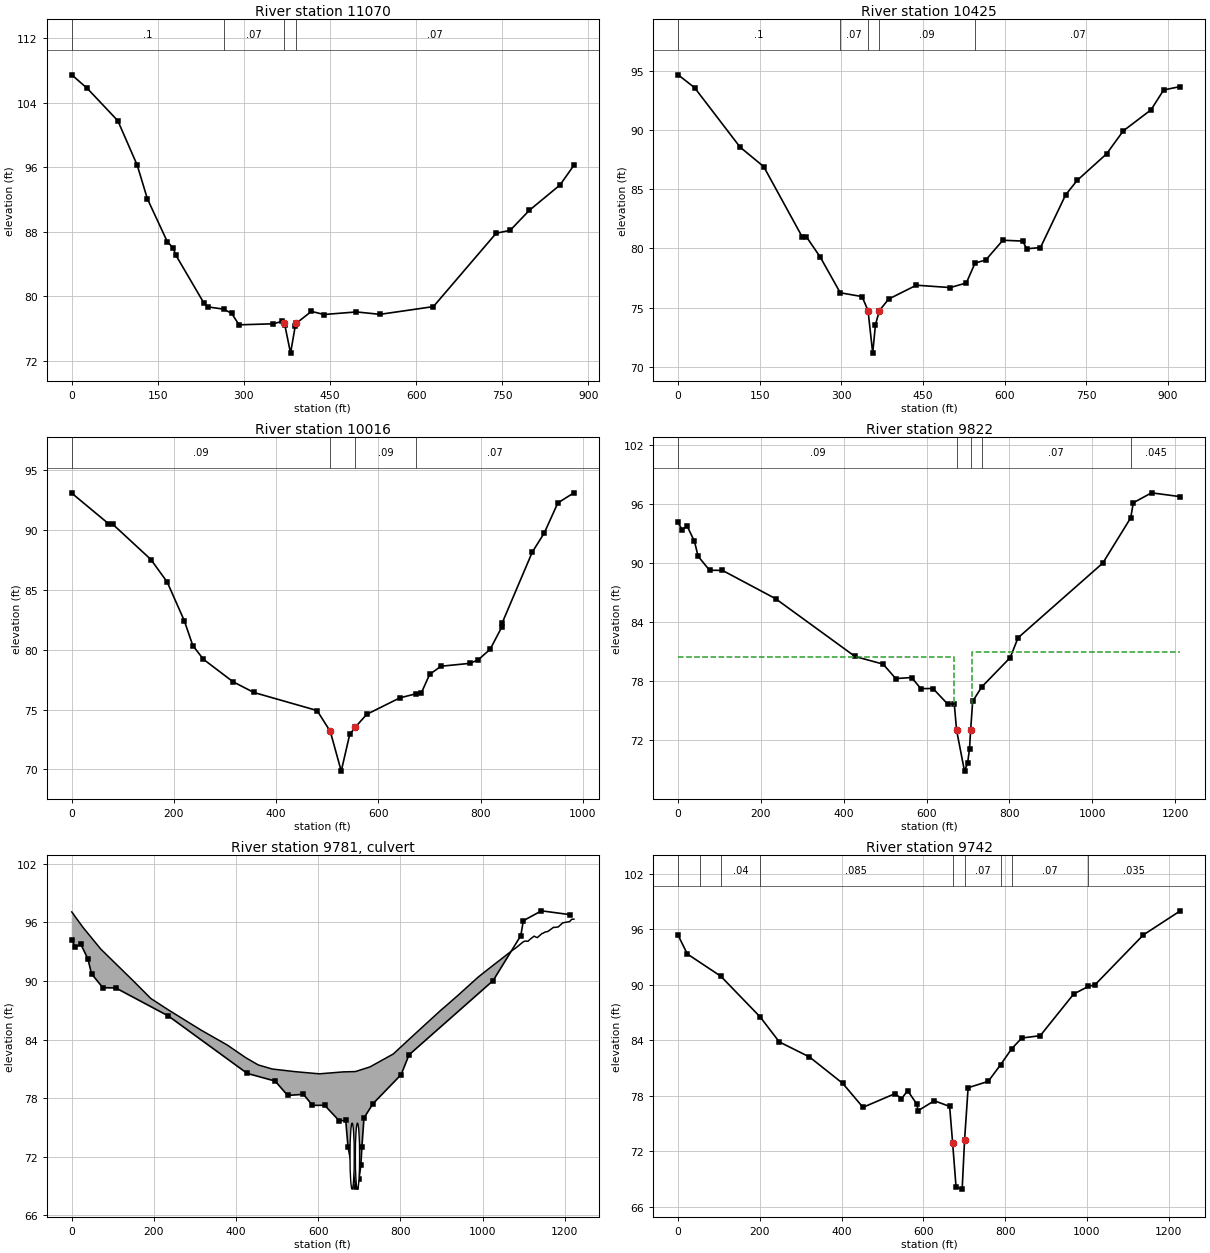
Type RM Length L Ch R = 1 ,11070   ,574.36,645.48,628.84
XS GIS Cut Line= 2
2358167.08365417627691.5532691332359019.02781415627492.162082762
#Sta/Elev= 30
       0  107.44   27.08  105.75   80.18  101.75  114.02   96.24  131.69   92.07
  166.53   86.73  176.82   85.95  180.89   85.13  230.62   79.08  237.41   78.65
  264.41   78.38  278.66   77.85  291.42   76.43  351.46   76.56  365.51   76.85
   369.7   76.64  371.34   76.37  381.24   72.92  389.49   76.32  391.55   76.64
   417.6    78.1  439.37   77.71  496.12   78.03  536.98   77.73  630.12   78.69
  739.49   87.79  763.94   88.15  797.11   90.62  850.66   93.77  874.97   96.22
#Mann= 4 ,-1 , 0
       0      .1       0  264.41     .07       0   369.7     .05       0
  391.55     .07       0
Bank Sta=369.7,391.55
XS Rating Curve= 0 ,0
Exp/Cntr=0.3,0.1

Type RM Length L Ch R = 1 ,10425   ,394.65,408.83,354.75
XS GIS Cut Line= 3
2358198.80497928628244.4106495382358468.43624267628192.297043994
2359116.45759837628203.626088709
#Sta/Elev= 30
       0   94.67    30.2   93.58  113.76   88.56  157.21   86.91  227.87   80.98
   235.8   80.97   260.9   79.28  297.85   76.25  337.82   75.93  348.88   74.75
  357.48   71.15   362.5   73.55  369.85   74.75  386.81   75.72  437.67   76.89
  499.99   76.69  529.51   77.08  545.52   78.76   565.2   79.02  596.69   80.69
  632.92   80.62   640.7   79.97  665.76   80.07  711.94   84.52  733.03   85.74
  787.22   87.99   817.9   89.93  868.87   91.71  892.15   93.39  922.74   93.68
#Mann= 5 ,-1 , 0
       0      .1       0  297.85     .07       0  348.88     .05       0
  369.85     .09       0  545.52     .07       0
Bank Sta=348.88,369.85
XS Rating Curve= 0 ,0
Exp/Cntr=0.3,0.1

Type RM Length L Ch R = 1 ,10016   ,181.34,193.99,179.86
XS GIS Cut Line= 2
2358046.99578054628656.7878759212359016.76200525628498.181250378
#Sta/Elev= 30
       0   93.07   71.67   90.53   80.36   90.47  154.87   87.53  186.75   85.65
  220.39    82.4  236.82   80.35  257.59    79.2  315.35   77.33  356.18   76.43
  480.04   74.92  505.94   73.17  527.32   69.86  543.94   72.93  555.07   73.54
  577.13    74.6  641.62   75.97  673.61   76.32  684.37   76.42  700.31   77.94
  722.56   78.62  779.07   78.86  795.17   79.15  818.66   80.03  841.18   81.86
  842.64   82.27   901.1   88.14  924.79   89.76  951.26   92.26  982.65    93.1
#Mann= 4 ,-1 , 0
       0     .09       0  505.94     .05       0  555.07     .09       0
  673.61     .07       0
Bank Sta=505.94,555.07
XS Rating Curve= 0 ,0
Exp/Cntr=0.5,0.3

Type RM Length L Ch R = 1 ,9822    ,71.37,79.94,80.06
BEGIN DESCRIPTION:
Surveyed Section
END DESCRIPTION:
XS GIS Cut Line= 6
2357989.23984104 628911.286231162358315.40649298628797.386765406
2358764.26770002628722.1455000042358944.44217885628679.604363337
2359023.39521764628648.5408726782359151.53211658628582.530955017
#Sta/Elev= 30
       0   94.17    8.73   93.44   21.86   93.77   39.37   92.23   48.14   90.72
   75.71    89.3  107.01   89.28  235.12   86.41   427.2   80.53  494.98   79.75
  525.53   78.28  564.08   78.39  585.91   77.26 615.542   77.27  651.15   75.68
 666.894   75.72 672.382   73.05 691.595   68.87 699.117    69.7 703.689   71.13
 706.357   73.04  711.33   75.97  733.19   77.43 801.856   80.41  820.98   82.43
 1025.71   90.03  1093.1   94.63 1099.28   96.16 1143.41   97.17 1212.85   96.78
#Mann= 5 ,-1 , 0
       0     .09       0 672.382     .05       0 706.357     .09       0
  733.19     .07       0  1093.1    .045       0
#XS Ineff= 2 , 0
       0  667.38   80.49  710.63       0   80.99
Permanent Ineff=
       F       F
Bank Sta=672.382,706.357
XS Rating Curve= 0 ,0
Exp/Cntr=0.5,0.3

Type RM Length L Ch R = 2 ,9781    ,,,
BEGIN DESCRIPTION:
Cow Branch Road
END DESCRIPTION:
Bridge Culvert--1,0,-1,-1, 0
Deck Dist Width WeirC Skew NumUp NumDn MinLoCord MaxHiCord MaxSubmerge Is_Ogee
29.5,19.5,2.6,0, 49, 49, , , 0.98, 0, 1,1,,
       0   26.86   70.54  149.55  192.44  234.49  315.28  378.05  423.93  453.97
 488.246 544.354 602.532 661.497 690.388 726.031 782.634 840.282 899.044  910.74
  941.74  988.55 1010.94 1073.02  1082.2 1082.69 1083.04 1098.73 1103.98 1110.49
 1115.12 1125.54 1130.38  1133.3 1144.68 1147.58 1152.61 1158.68 1171.07 1171.89
 1172.83 1175.42 1184.24 1194.84    1195 1195.14 1211.85 1217.08 1222.38
   97.06    95.5   93.26   90.01    88.2   87.05   84.95   83.45   82.13    81.4
   80.98   80.71   80.49   80.69   80.72    81.2   82.52   84.76   87.02   87.44
   88.58   90.36   91.11   93.14   93.41   93.43   93.44   93.99   94.08   94.05
   94.24   94.58   94.47   94.43   94.85   94.88   95.01   95.05   95.43   95.46
   95.49   95.47   95.52   95.93   95.94   95.94   96.07    96.3   96.32
                                                                                
                                                                                
                                                                                
                                                                                
                                                                        
       0   26.86   70.54  149.55  192.44  234.49  315.28  378.05  423.93  453.97
 488.246 544.354 602.532 661.497 690.388 726.031 782.634 840.282 899.044  910.74
  941.74  988.55 1010.94 1073.02  1082.2 1082.69 1083.04 1098.73 1103.98 1110.49
 1115.12 1125.54 1130.38  1133.3 1144.68 1147.58 1152.61 1158.68 1171.07 1171.89
 1172.83 1175.42 1184.24 1194.84    1195 1195.14 1211.85 1217.08 1222.38
   97.06    95.5   93.26   90.01    88.2   87.05   84.95   83.45   82.13    81.4
   80.98   80.71   80.49   80.69   80.72    81.2   82.52   84.76   87.02   87.44
   88.58   90.36   91.11   93.14   93.41   93.43   93.44   93.99   94.08   94.05
   94.24   94.58   94.47   94.43   94.85   94.88   95.01   95.05   95.43   95.46
   95.49   95.47   95.52   95.93   95.94   95.94   96.07    96.3   96.32
                                                                                
                                                                                
                                                                                
                                                                                
                                                                        
BR Coef=-1 , 1 , 0 ,1.25, 0 ,,,0.8,0,2,0,
WSPro=,,,, 1 ,,,, 0 ,,,, 0 ,,,,-1 ,-1 ,-1 , 0 , 0 , 0 , 0 , 0
Multiple Barrel Culv=3,6.75,10.25,55,0.024,0.9,1,34,3,68.69,67.95, 2,Culvert #1  , 0 ,13.5
   682.5   679.5   695.5   692.5
Culvert Bottom n=0.024
BC Design=,, 0 ,, 0 ,,,,,,
BC Use User HTab Curves=0
BC User HTab FreeFlow(D)= 0

Type RM Length L Ch R = 1 ,9742    ,194.61,205.53,189.59
BEGIN DESCRIPTION:
Surveyed Section
END DESCRIPTION:
XS GIS Cut Line= 6
2358013.83177114628978.590460926 2358341.2927352628867.279619396
2358578.24850005628823.9244000022358670.39619999 628820.77670002
2358956.09098782 628755.968777882359185.18423146628647.246560574
#Sta/Elev= 30
       0   95.34   22.39   93.33   104.2   90.93  200.42   86.53  247.44   83.82
  321.25   82.19  402.72   79.33  452.24   76.74  531.16   78.23  546.33   77.65
  561.53   78.55  584.49   77.05 586.934   76.37  626.84   77.45 664.311   76.84
 671.574   72.92  680.05    68.1  695.01   67.89 700.805   73.16 709.532   78.86
 758.788   79.55  789.39  81.371  816.18   83.08  840.91   84.24  886.04   84.49
  967.93      89 1004.07   89.83 1019.87   89.99 1138.55    95.4 1228.82      98
#Mann= 9 ,-1 , 0
       0     .04       0   54.19    .035       0   104.2     .04       0
  200.42    .085       0 671.574     .05       0 700.805     .07       0
  789.39    .035       0  816.18     .07       0 1004.07    .035       0
#XS Ineff= 2 , 0
       0  664.38    74.7  707.63       0    74.7
Permanent Ineff=
       F       F
Bank Sta=671.574,700.805
XS Rating Curve= 0 ,0
Exp/Cntr=0.5,0.3

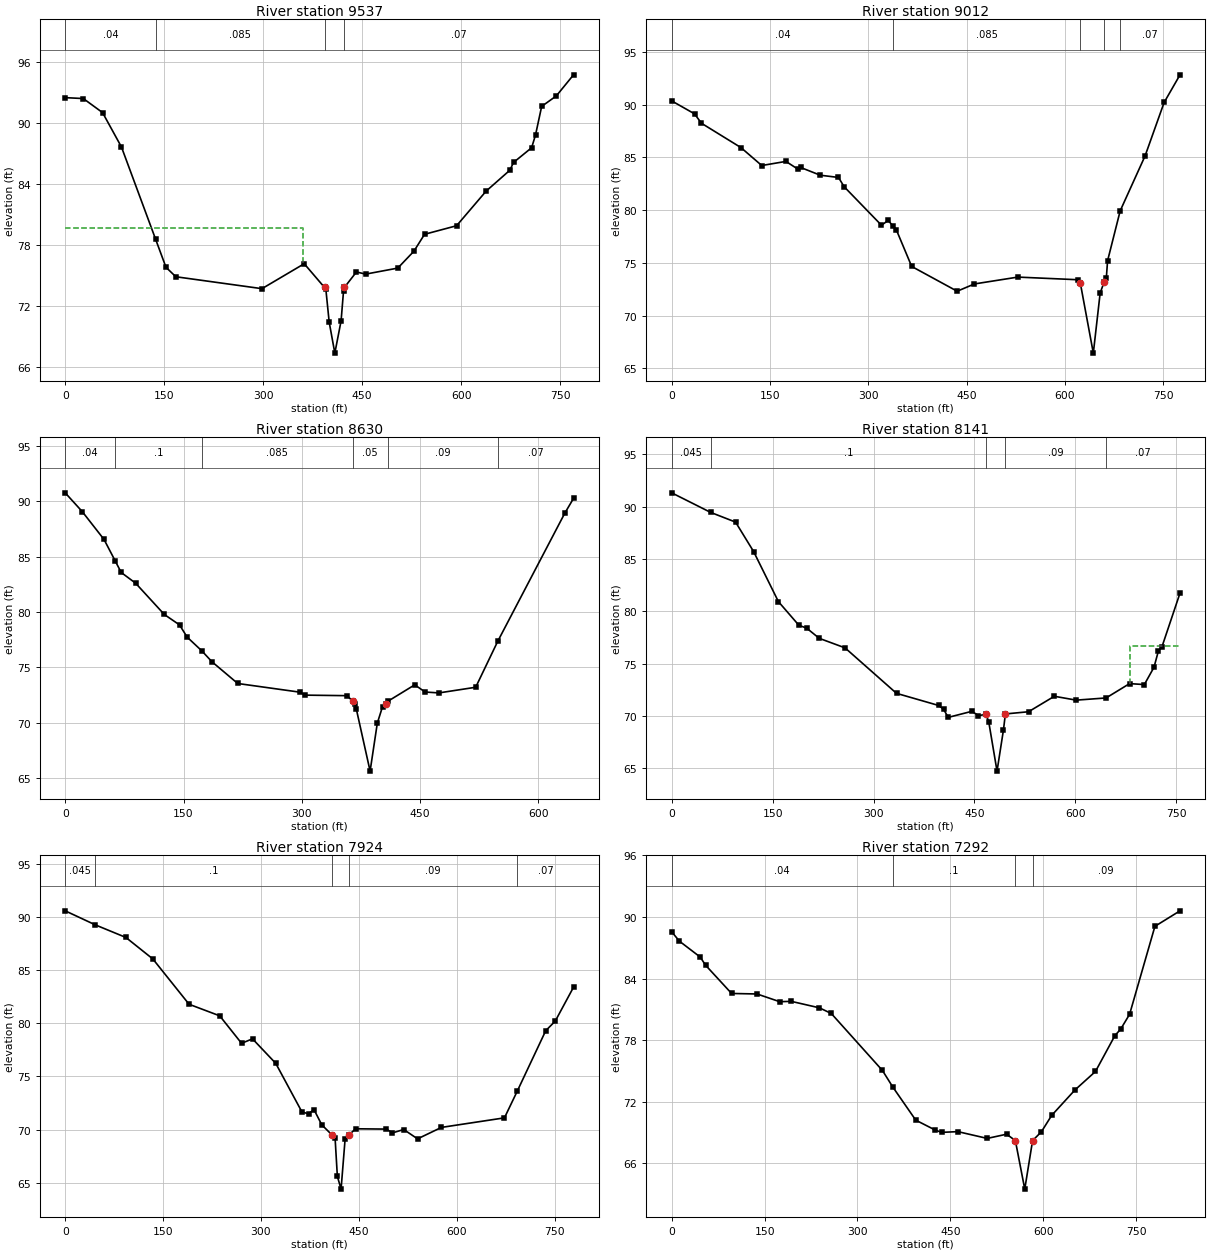
Type RM Length L Ch R = 1 ,9537    ,494.71,524.03,433.64
XS GIS Cut Line= 4
2358242.93191165629091.3209076822358623.32633275629007.280279741
2358656.50026485629011.703470677  2358999.297563 628956.41358389
#Sta/Elev= 30
       0   92.46   27.44   92.37   56.61   90.99   85.25   87.61  136.95   78.56
  152.69    75.8  167.65   74.87  298.15    73.7  362.17   76.15  392.91   73.82
  394.97   73.63     400   70.42  408.55   67.37  418.05   70.54  421.75   73.48
  423.04   73.82  441.28   75.34  455.31   75.13  503.96   75.72   528.4   77.38
  544.52   79.04  593.02   79.88  637.82   83.28  673.74   85.33  679.41    86.1
  706.75   87.54  712.65   88.79  721.95    91.6  744.19   92.63  770.26    94.7
#Mann= 4 ,-1 , 0
       0     .04       0  136.95    .085       0  392.91     .05       0
  423.04     .07       0
#XS Ineff= 2 , 0
       0   359.8   79.61               0
Permanent Ineff=
       F       F
Bank Sta=392.91,423.04
XS Rating Curve= 0 ,0
Exp/Cntr=0.3,0.1

Type RM Length L Ch R = 1 ,9012    ,327.69,382.46,345.5
XS GIS Cut Line= 2
 2358307.5638082629646.9463809882359025.82524098629354.657028213
#Sta/Elev= 30
       0   90.36   34.88   89.13   45.38   88.24  105.69   85.93  137.42   84.23
  174.29   84.62  193.19   83.86  196.54   84.05  226.73   83.31  254.48    83.1
  263.09   82.22  320.01   78.57  330.32   79.02  338.25   78.45  342.75   78.13
  366.14   74.66  435.53   72.31  461.82      73   528.1   73.65  619.51    73.4
  623.29   73.12  643.23   66.44  653.68   72.15  659.75   73.18  663.05   73.55
  664.99    75.2  684.19   79.93  722.19   85.14  751.25   90.21  775.46   92.83
#Mann= 5 ,-1 , 0
       0     .04       0  338.25    .085       0  623.29     .05       0
  659.75     .09       0  684.19     .07       0
Bank Sta=623.29,659.75
XS Rating Curve= 0 ,0
Exp/Cntr=0.3,0.1

Type RM Length L Ch R = 1 ,8630    ,452.62,488.88,466.15
XS GIS Cut Line= 4
2358525.08146609629884.8563192642358687.46260148629832.205390722
 2359039.1062815 629717.202426212359134.58406991629676.401897162
#Sta/Elev= 30
       0   90.75   21.67   89.05   49.23   86.54   63.35   84.61   71.01   83.56
   89.32   82.59  125.64   79.77  144.94   78.83  154.56   77.73  173.44   76.47
  185.94   75.51  218.76   73.54  298.25   72.75  303.79   72.49  357.68   72.44
  364.56   71.92  367.34   71.71  369.12   71.23  386.58   65.63  395.72   69.96
  402.38   71.46  406.15   71.73  408.75   71.92  443.19   73.42  456.33   72.77
  473.81   72.69  520.45    73.2  548.35   77.34  633.48   88.92  644.51   90.25
#Mann= 6 ,-1 , 0
       0     .04       0   63.35      .1       0  173.44    .085       0
  364.56     .05       0  408.75     .09       0  548.35     .07       0
Bank Sta=364.56,406.15
XS Rating Curve= 0 ,0
Exp/Cntr=0.3,0.1

Type RM Length L Ch R = 1 ,8141    ,160.93,217.35,172.28
XS GIS Cut Line= 3
2358661.03000227630315.3600171212359337.67167017630093.173656404
2359374.75981714630070.652652025
#Sta/Elev= 30
       0   91.33   57.88   89.46   94.97   88.53  121.82   85.71  158.69   80.92
   189.1   78.66  200.59   78.39  219.44   77.41  257.71    76.5   334.2   72.15
  396.81   70.99  404.15   70.63  411.03   69.85  446.17   70.43  455.98   70.03
  467.23   70.13  471.26   69.44  483.61   64.71  493.11   68.63  496.05   70.18
  530.46   70.39  568.79   71.87  601.29    71.5  645.72   71.71  680.61   73.08
  702.57   72.99  716.89   74.64  723.52   76.21  728.86   76.62  755.58   81.74
#Mann= 5 ,-1 , 0
       0    .045       0   57.88      .1       0  467.23     .05       0
  496.05     .09       0  645.72     .07       0
#XS Ineff= 2 , 0
       0                  681.37       0   76.68
Permanent Ineff=
       F       F
Bank Sta=467.23,496.05
XS Rating Curve= 0 ,0
Exp/Cntr=0.3,0.1

Type RM Length L Ch R = 1 ,7924    ,544.37,631.64,573.74
XS GIS Cut Line= 3
2358679.15647374630462.6375979632359331.03688377630281.159271523
2359426.87342262630245.119940102
#Sta/Elev= 30
       0   90.62   46.35   89.29      93   88.11  134.34   86.08  189.85   81.81
   236.8   80.72  270.27   78.13  287.07   78.55  322.67   76.24  362.79   71.66
  372.89   71.48  381.28   71.88  393.15   70.45   408.5   69.51  413.64   69.18
   417.1   65.58   422.8   64.38  429.04   69.15  434.97   69.49  444.92   70.07
  492.34   70.04   501.3   69.68  518.85      70  540.02   69.12  576.61    70.2
  673.18    71.1  693.13   73.66  736.47   79.32  751.02   80.22  779.06   83.42
#Mann= 5 ,-1 , 0
       0    .045       0   46.35      .1       0   408.5     .05       0
  434.97     .09       0  693.13     .07       0
Bank Sta=408.5,434.97
XS Rating Curve= 0 ,0
Exp/Cntr=0.3,0.1

Type RM Length L Ch R = 1 ,7292    ,516.67,545.02,534.54
XS GIS Cut Line= 3
2358717.67522565630870.4832064662358971.44582653 630920.33100307
2359527.86888075 630840.69292587
#Sta/Elev= 30
       0   88.57   12.57   87.65   46.02   86.11   54.62   85.32   96.75   82.56
  137.81   82.51  174.36   81.76  193.19   81.79  238.56   81.16  257.68   80.61
  340.26   75.06  357.09   73.44  394.07   70.22   425.3   69.26  435.68   69.03
  462.12    69.1  509.48   68.44  540.74   68.85   554.9   68.23  570.07    63.5
  582.68   68.22  596.97   69.09   613.5   70.68  650.95   73.15  684.21   74.96
  715.67   78.46  724.88   79.08  739.33   80.53  780.21    89.1  820.71   90.61
#Mann= 4 ,-1 , 0
       0     .04       0  357.09      .1       0   554.9     .05       0
  582.68     .09       0
Bank Sta=554.9,582.68
XS Rating Curve= 0 ,0
Exp/Cntr=0.3,0.1

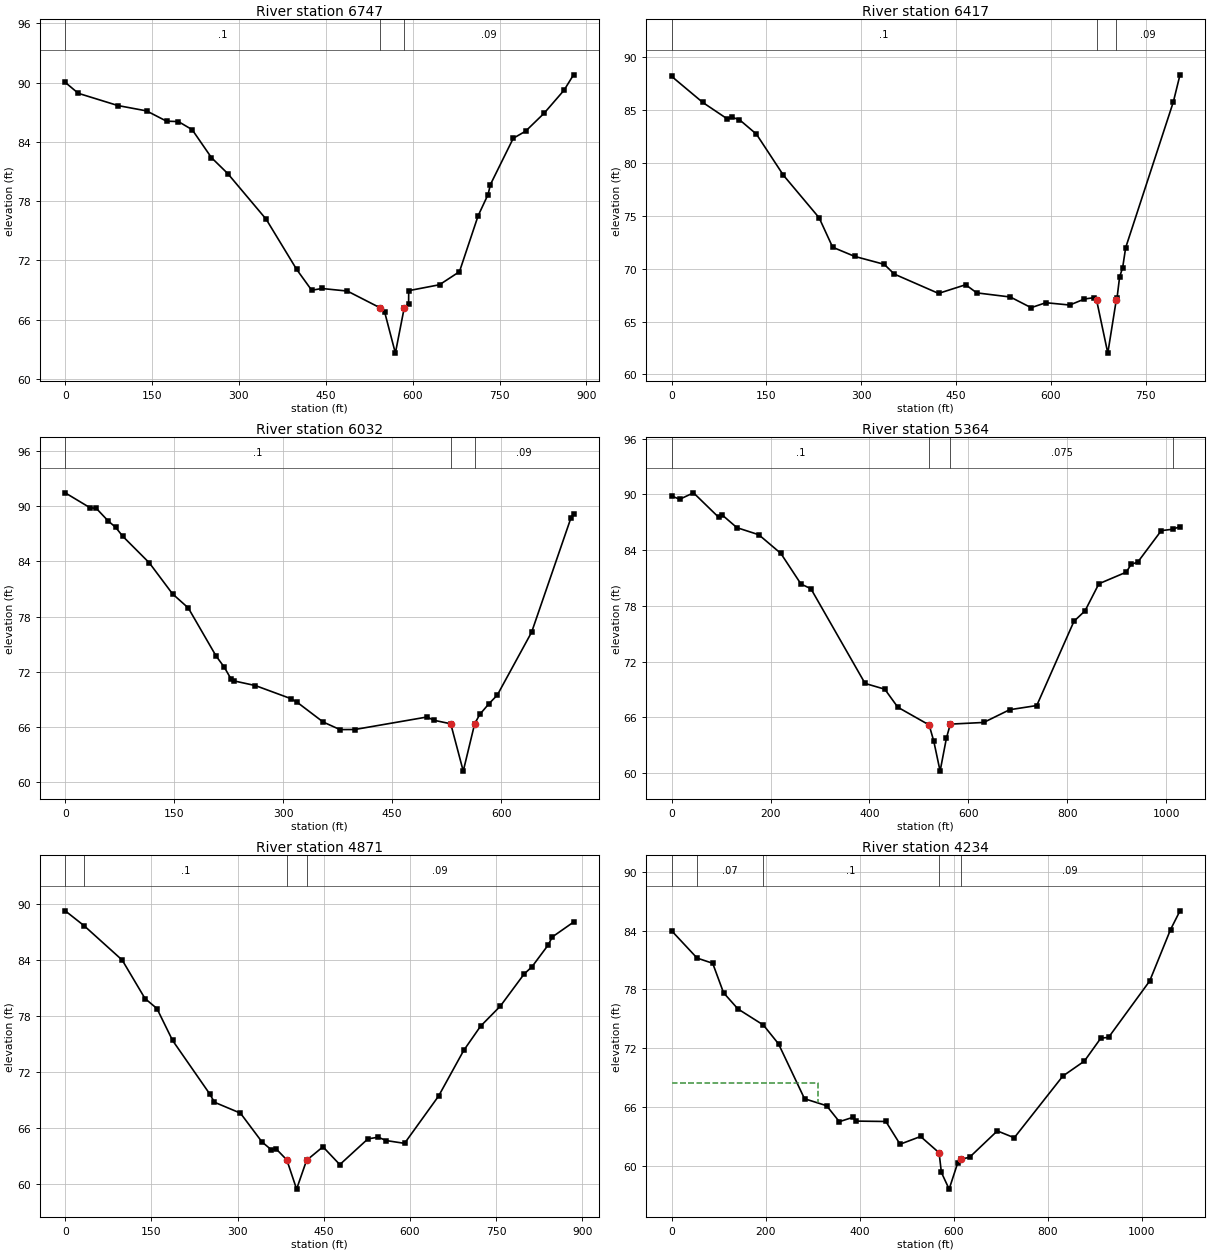
Type RM Length L Ch R = 1 ,6747    ,268.72,330.38,272.55
XS GIS Cut Line= 3
2358700.73217428631362.6294572352358892.14251371631425.606395811
2359567.35357668631389.353452832
#Sta/Elev= 30
       0   90.02   22.58   88.91   91.07   87.67  140.48   87.13  174.98   86.09
  195.45   86.05  219.21   85.23  252.52    82.4  280.61   80.79  346.95   76.17
  399.63   71.09  425.61   68.98  443.09   69.16   487.2    68.9  543.19   67.22
  551.64   66.76  570.07   62.62  585.43   67.22  592.93    67.6   593.1   68.94
  646.27   69.54  680.72   70.86  712.96   76.52  730.11   78.67   734.2   79.68
  773.64   84.36  794.99   85.08  826.85   86.89  861.26   89.22  877.69   90.78
#Mann= 3 , 0 , 0
       0      .1       0  543.19     .05       0  585.43     .09       0
Bank Sta=543.19,585.43
XS Rating Curve= 0 ,0
Exp/Cntr=0.3,0.1

Type RM Length L Ch R = 1 ,6417    ,306.8,384.95,319.72
XS GIS Cut Line= 2
2358710.87779887631713.3641307062359512.97416222631654.453098357
#Sta/Elev= 30
       0    88.2   49.14   85.74   88.23   84.17   94.76   84.35  107.29    84.1
  134.07   82.74   176.8   78.85  233.24   74.83  254.69   72.04  289.62   71.17
  336.36   70.42  352.16    69.5  422.21   67.67  465.09   68.49  482.77   67.72
  535.83   67.33   568.7   66.32  592.01   66.79  629.81   66.57  653.05   67.14
  668.36   67.27  672.18   67.07  690.02   62.02  703.56   67.09  704.71   67.27
  708.71   69.22  713.56   70.12  718.27   71.99  793.73   85.79  804.26   88.35
#Mann= 3 , 0 , 0
       0      .1       0  672.18     .05       0  703.56     .09       0
Bank Sta=672.18,703.56
XS Rating Curve= 0 ,0
Exp/Cntr=0.3,0.1

Type RM Length L Ch R = 1 ,6032    ,507,667.4,504.92
XS GIS Cut Line= 2
2358806.04177418632012.4509102552359503.91092648631962.603113666
#Sta/Elev= 30
       0   91.43   34.19   89.81   42.83   89.74    59.1   88.38   69.34   87.69
   79.24   86.71  115.83   83.82  147.69   80.46  169.38   78.93  207.66   73.71
  218.82   72.51  228.68   71.16  232.72      71  261.77    70.5  310.28   69.09
  319.36   68.68  355.07   66.54  378.21   65.72  398.58   65.73  498.23   67.09
  507.02   66.74  530.64   66.35  547.86   61.21  563.56   66.35  570.63   67.37
  583.26   68.53  594.73   69.47  641.98    76.3  695.92   88.67  699.65   89.13
#Mann= 3 , 0 , 0
       0      .1       0  530.64     .05       0  563.56     .09       0
Bank Sta=530.64,563.56
XS Rating Curve= 0 ,0
Exp/Cntr=0.3,0.1

Type RM Length L Ch R = 1 ,5364    ,357.34,493.26,358.75
XS GIS Cut Line= 4
2358731.69451089632470.6387886112358901.98736222632503.812720686
2359545.56164452632461.7924067232359744.60523699632395.444542572
#Sta/Elev= 30
       0   89.81   16.32   89.47   44.14   90.16   95.17   87.52  102.57   87.76
  131.95   86.41  176.16   85.65  220.79   83.64  261.57   80.34   281.6   79.84
   391.2   69.64   431.1   69.02  457.41   67.08  520.78   65.17  530.17   63.43
  542.99    60.2  555.82   63.77  563.65   65.26  631.22   65.44  683.62   66.81
  738.48   67.26  813.76   76.33  836.19   77.46  864.17   80.37  919.57   81.62
  929.48   82.47  942.65   82.69  990.38   86.09 1013.55   86.24 1028.25   86.52
#Mann= 4 ,-1 , 0
       0      .1       0  520.78     .05       0  563.65    .075       0
 1013.55    .032       0
Bank Sta=520.78,563.65
XS Rating Curve= 0 ,0
Exp/Cntr=0.3,0.1

Type RM Length L Ch R = 1 ,4871    ,570.4,636.77,572.31
XS GIS Cut Line= 4
2358830.96567248632909.7112489492359176.22520073632820.070873156
2359523.44568978632806.8013003322359703.30211285632819.078891531
#Sta/Elev= 30
       0   89.29   32.72    87.7   99.12   84.01  138.88   79.88   159.6   78.81
   186.8   75.39  251.78   69.62  259.64   68.76  304.87   67.59   342.4    64.5
  358.07   63.69  367.27   63.74  385.63   62.57  402.61   59.44  419.99   62.53
  448.49   63.98  477.78   62.07   526.7   64.83  544.66   65.01  558.35   64.65
  590.45   64.35  649.56   69.41  693.31   74.31  722.76   76.92  757.12   79.07
  798.58   82.52  812.16   83.29  840.05    85.6  847.56   86.49  884.46   88.08
#Mann= 4 ,-1 , 0
       0    .045       0   32.72      .1       0  385.63     .05       0
  419.99     .09       0
Bank Sta=385.63,419.99
XS Rating Curve= 0 ,0
Exp/Cntr=0.3,0.1

Type RM Length L Ch R = 1 ,4234    ,639.6,755.14,648.22
XS GIS Cut Line= 2
2358776.58625802633371.9362719212359857.37712049 633390.06274341
#Sta/Elev= 30
       0   83.97   54.05   81.19   87.21   80.66  110.33   77.65  140.94      76
     195   74.36  227.18   72.44  282.53   66.84  329.42   66.13  356.52    64.5
  385.65   64.95  392.32   64.56   455.5   64.52  485.67    62.2  529.33   62.99
  568.65   61.33  573.55   59.32  590.02   57.62     608   60.26  614.23   60.66
  633.47   60.87  692.46   63.56  728.49   62.86  831.74   69.15   877.6   70.68
  912.55   73.02  929.04    73.1 1016.46   78.85 1060.76   84.09 1080.94   86.01
#Mann= 5 ,-1 , 0
       0    .045       0   54.05     .07       0     195      .1       0
  568.65     .05       0  614.23     .09       0
#XS Ineff= 2 , 0
       0  310.29   68.42               0
Permanent Ineff=
       F       F
Bank Sta=568.65,614.23
XS Rating Curve= 0 ,0
Exp/Cntr=0.3,0.1