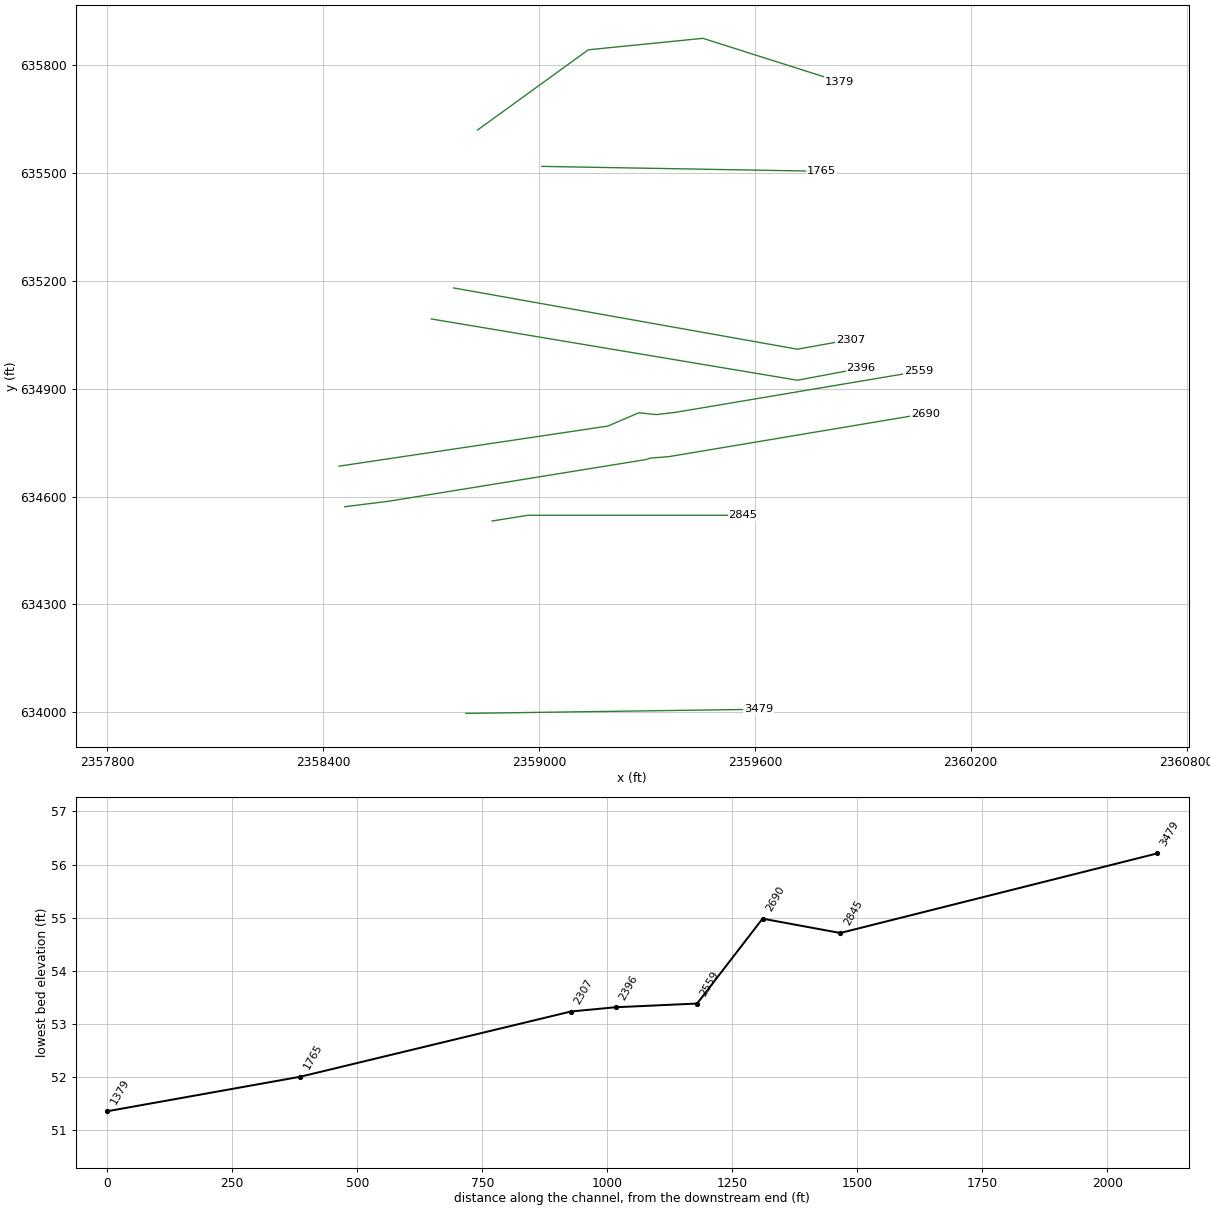
HEC-RAS study DTL_Cow_Branch.prj: DTL_Cow_Branch

--- DTL_Cow_Branch.g01 (geometry) --- (continued)

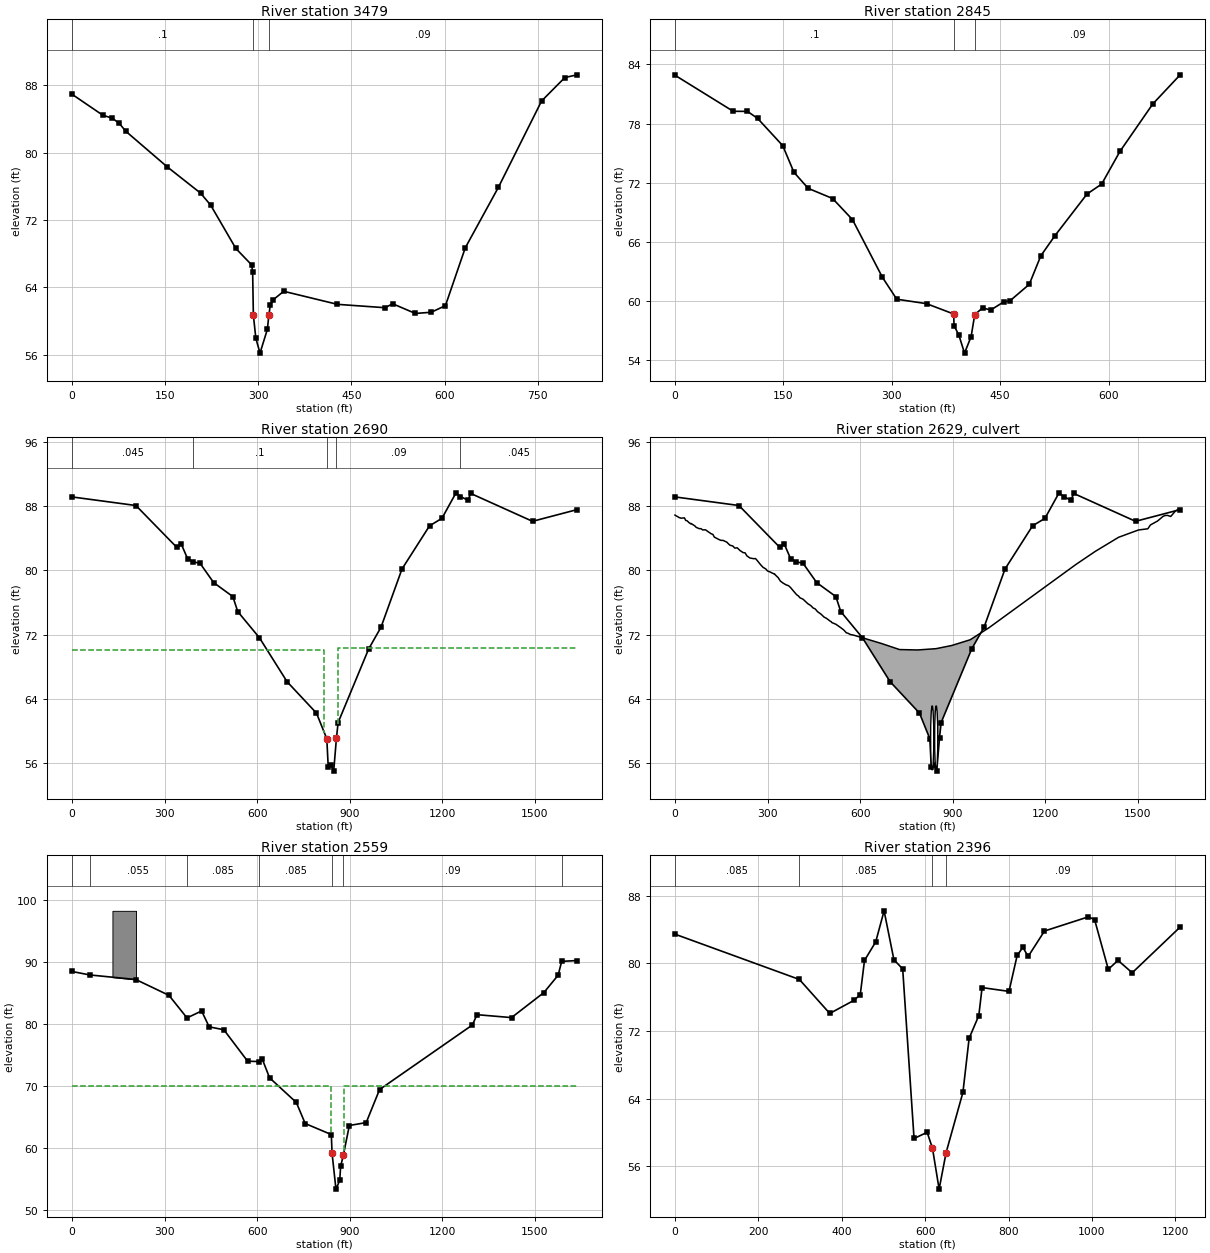
Type RM Length L Ch R = 1 ,3479    ,571.56,633.78,551.22
XS GIS Cut Line= 2
2358796.97853845633997.2995382852359610.40394649634008.628582984
#Sta/Elev= 30
       0   86.94   49.66   84.45   65.08   84.09    76.4   83.47   86.48   82.56
  152.92   78.35  207.12    75.2  223.35   73.78  263.96   68.63  289.43   66.68
  291.01   65.82  292.16   60.72  296.14   57.98  302.85   56.21  314.73   59.04
   317.1   60.72  319.48   61.93     324   62.54  341.05   63.55  427.53      62
  504.26    61.6  516.44   62.07  552.98   60.92  578.56   61.06  601.45   61.85
  633.39   68.71  686.59   75.87  756.32   86.14  793.78   88.92   813.5   89.24
#Mann= 3 , 0 , 0
       0      .1       0  292.16     .05       0   317.1     .09       0
Bank Sta=292.16,317.1
XS Rating Curve= 0 ,0
Exp/Cntr=0.3,0.1

Type RM Length L Ch R = 1 ,2845    ,146.09,155.55,161.02
XS GIS Cut Line= 3
2358869.48442438  634532.03044722358969.18001756634547.891109765
2359567.35357668634547.891109765
#Sta/Elev= 30
       0   82.91    80.6   79.25  100.38   79.24   114.5   78.52  149.18   75.76
  164.65   73.06  184.41   71.43  218.16    70.4  245.63   68.26  287.19   62.39
  306.95   60.18  348.12   59.73  385.75   58.68  386.19   57.51  392.9856.52015
  400.71   54.71  409.86   56.39  414.85   58.62  425.79    59.3  436.89   59.08
  455.41   59.93  463.35      60   490.3   61.69  506.32   64.59  525.88   66.63
  570.19   70.85  590.55   71.87  615.72   75.17   661.2   79.99  699.12   82.95
#Mann= 3 , 0 , 0
       0      .1       0  385.75     .05       0  414.85     .09       0
Bank Sta=385.75,414.85
XS Rating Curve= 0 ,0
Exp/Cntr=0.5,0.3

Type RM Length L Ch R = 1 ,2690    ,128.98,130.81,119.75
BEGIN DESCRIPTION:
Surveyed Section
END DESCRIPTION:
XS GIS Cut Line= 6
2358459.66826788634571.6544868352358583.51761431634587.135655165
2359298.34310003634702.9782000182359309.76100001634706.873200014
2359361.54050002634711.0141000152360074.13296227634830.411157042
#Sta/Elev= 30
       0   89.15  207.31   88.08  340.13   82.85  354.09   83.29  374.64   81.46
  392.55   81.07  415.25   80.87  459.32   78.47  521.38   76.73  537.35   74.86
  607.51    71.6  697.21   66.12 792.353   62.21 825.894   59.01 830.546   55.45
 837.847    55.8  848.15   54.98  857.24   59.15 862.491   61.03 961.558   70.21
 1001.45   72.91 1069.51   80.17 1158.82   85.55 1198.89   86.48 1244.54   89.66
    1259    89.2 1283.08   88.74 1292.26   89.58 1492.44   86.11 1636.97   87.57
#Mann= 5 ,-1 , 0
       0    .045       0  392.55      .1       0 825.894     .05       0
  857.24     .09       0    1259    .045       0
#XS Ineff= 2 , 0
       0  818.04   70.08  861.96       0   70.36
Permanent Ineff=
       F       F
Bank Sta=825.894,857.24
XS Rating Curve= 0 ,0
Exp/Cntr=0.5,0.3

Type RM Length L Ch R = 2 ,2629    ,,,
BEGIN DESCRIPTION:
Fort Run Road (CMP, Chart# reflects concrete b/c no CMP chart# matchs)
END DESCRIPTION:
Bridge Culvert--1,0,-1,-1, 0
Deck Dist Width WeirC Skew NumUp NumDn MinLoCord MaxHiCord MaxSubmerge Is_Ogee
50.3,20.5,2.6,0, 107, 107, , , 0.98, 0, 1,1,,
       0    5.42    8.32   12.61   20.01   30.75    34.9    39.2   46.31   51.12
   52.05   64.07   68.75   78.22   84.51   89.63   98.99  110.71  112.62  115.68
     123  127.62   129.2   137.6  142.03  149.51  155.42  168.26  172.05  178.27
  187.21  194.19  201.78  211.55  215.36   220.2  227.29  232.94  242.76  255.32
  260.96  265.36  278.43  285.66  294.16  300.04   308.6  321.08  322.57  324.67
  334.44  341.47  349.21  359.53  367.94  374.28  384.74  394.62  400.32  404.68
  415.21  429.22  429.69  430.36  440.47   447.7  454.23  462.32  473.68   482.9
  490.86  503.69  506.32   508.6  521.57   536.7  536.71  536.72  547.35  555.17
  560.61   568.1  580.51 669.595 727.675 786.475 845.931 897.283 956.5891017.534
 1299.11 1361.76  1437.5 1501.89 1532.23 1540.71 1560.52 1563.16 1570.95  1582.2
 1589.63 1596.08 1606.21 1606.32 1606.39 1622.24 1634.13
   86.89   86.75   86.71   86.59    86.5   86.54   86.22   86.18   85.92    85.8
   85.84   85.55   85.36    85.2   85.19   85.04   85.05   84.73   84.69   84.59
   84.47   84.14   84.11   83.94   83.85   83.73   83.74   83.51   83.35   83.13
   83.04   82.77   82.81   82.44   82.36   82.22   82.18   81.81   81.54   81.45
   81.47   81.28   80.66   80.37   80.18   79.92   79.79   79.55   79.57   79.45
   79.09   78.67   78.44    78.2   78.09   77.87   77.39   76.95    76.8   76.59
    76.4   75.89   75.89   75.85    75.6   75.31    75.2   74.84   74.53   74.18
   74.02   73.65    73.6   73.49   73.28   72.87   72.87   72.87   72.56   72.22
   72.16   72.01   71.91   70.88   70.13   70.08   70.24   70.64   71.35   72.85
   80.73   82.36   84.12   85.03   85.18   85.66   86.08   86.13   86.38   86.75
   86.84   86.85   86.71   86.71   86.71   87.42   87.63
                                                                                
                                                                                
                                                                                
                                                                                
                                                                                
                                                                                
                                                                                
                                                                                
                                                                                
                                                                                
                                                        
       0    5.42    8.32   12.61   20.01   30.75    34.9    39.2   46.31   51.12
   52.05   64.07   68.75   78.22   84.51   89.63   98.99  110.71  112.62  115.68
     123  127.62   129.2   137.6  142.03  149.51  155.42  168.26  172.05  178.27
  187.21  194.19  201.78  211.55  215.36   220.2  227.29  232.94  242.76  255.32
  260.96  265.36  278.43  285.66  294.16  300.04   308.6  321.08  322.57  324.67
  334.44  341.47  349.21  359.53  367.94  374.28  384.74  394.62  400.32  404.68
  415.21  429.22  429.69  430.36  440.47   447.7  454.23  462.32  473.68   482.9
  490.86  503.69  506.32   508.6  521.57   536.7  536.71  536.72  547.35  555.17
  560.61   568.1  580.51 669.595 727.675 786.475 845.931 897.283 956.5891017.534
 1299.11 1361.76  1437.5 1501.89 1532.23 1540.71 1560.52 1563.16 1570.95  1582.2
 1589.63 1596.08 1606.21 1606.32 1606.39 1622.24 1634.13
   86.89   86.75   86.71   86.59    86.5   86.54   86.22   86.18   85.92    85.8
   85.84   85.55   85.36    85.2   85.19   85.04   85.05   84.73   84.69   84.59
   84.47   84.14   84.11   83.94   83.85   83.73   83.74   83.51   83.35   83.13
   83.04   82.77   82.81   82.44   82.36   82.22   82.18   81.81   81.54   81.45
   81.47   81.28   80.66   80.37   80.18   79.92   79.79   79.55   79.57   79.45
   79.09   78.67   78.44    78.2   78.09   77.87   77.39   76.95    76.8   76.59
    76.4   75.89   75.89   75.85    75.6   75.31    75.2   74.84   74.53   74.18
   74.02   73.65    73.6   73.49   73.28   72.87   72.87   72.87   72.56   72.22
   72.16   72.01   71.91   70.88   70.13   70.08   70.24   70.64   71.35   72.85
   80.73   82.36   84.12   85.03   85.18   85.66   86.08   86.13   86.38   86.75
   86.84   86.85   86.71   86.71   86.71   87.42   87.63
                                                                                
                                                                                
                                                                                
                                                                                
                                                                                
                                                                                
                                                                                
                                                                                
                                                                                
                                                                                
                                                        
BR Coef=-1 , 1 , 0 ,1.25, 0 ,,,0.8,0,2,0,
WSPro=,,,, 1 ,,,, 0 ,,,, 0 ,,,,-1 ,-1 ,-1 , 0 , 0 , 0 , 0 , 0
Multiple Barrel Culv=4,8,10,80,0.024,0.9,1,30,1,55.12,54.99, 2,Culvert #1  , 0 ,21.3
   833.5   852.5   846.5   865.5
Culvert Bottom n=0.024
BC Design=,, 0 ,, 0 ,,,,,,
BC Use User HTab Curves=0
BC User HTab FreeFlow(D)= 0

Type RM Length L Ch R = 1 ,2559    ,181.08,163.13,160.15
BEGIN DESCRIPTION:
Surveyed Section
END DESCRIPTION:
XS GIS Cut Line= 6
2358444.18709955634684.445855916    2359191.5097634795.874899998
2359277.56500003634832.8558000182359325.98249999 634827.83950001
2359380.19550003634834.1676999932360054.22860302634947.625717074
#Sta/Elev= 30
       0   88.48   57.61   87.92  207.05   87.18  314.36   84.63  372.85   80.99
  420.13   82.11  444.63   79.55  492.16   79.08  569.21   74.01  607.06   73.95
  616.09   74.42   640.3   71.33  727.06   67.35 755.711   63.96 840.364   62.18
  842.76   59.18 855.352   53.38 867.623   54.78 870.543   57.05  879.51    58.9
 898.779   63.64 953.369   64.11  996.72   69.44 1297.39   79.85 1312.31   81.51
 1424.16   81.04 1528.88   85.07 1575.25   87.88 1586.64   90.11 1636.72   90.24
#Mann= 7 ,-1 , 0
       0    .045       0   57.61    .055       0  372.85    .085       0
  607.06    .085       0  842.76     .05       0  879.51     .09       0
 1586.64    .045       0
#XS Ineff= 2 , 0
       0  838.04   70.08  881.96       0   70.08
Permanent Ineff=
       F       F
#Block Obstruct= 1 ,-1
  131.23  207.74  98.258
Bank Sta=842.76,879.51
XS Rating Curve= 0 ,0
Exp/Cntr=0.5,0.3

Type RM Length L Ch R = 1 ,2396    ,91.11,89.28,91.83
XS GIS Cut Line= 3
2358700.73217428635093.5910181852359718.06609133634923.298166856
2359894.99372907634956.472098932
#Sta/Elev= 30
       0   83.47  298.39   78.11  371.24   74.09  429.19   75.64  444.39   76.32
  454.53   80.36  481.36   82.55  501.52   86.23  525.09   80.44  546.14   79.36
  573.36    59.3   604.8   60.03  617.57   58.14  633.49   53.31  650.27   57.64
  690.55   64.75  705.43   71.15  728.66   73.84  736.51   77.15     801    76.7
  820.62   80.95  834.29   81.91  847.01   80.83  886.12   83.84   991.5   85.52
 1006.31   85.19 1039.17   79.31 1062.44   80.37 1096.51    78.9  1211.5   84.31
#Mann= 4 ,-1 , 0
       0    .085       0  298.39    .085       0  617.57     .05       0
  650.27     .09       0
Bank Sta=617.57,650.27
XS Rating Curve= 0 ,0
Exp/Cntr=0.3,0.1

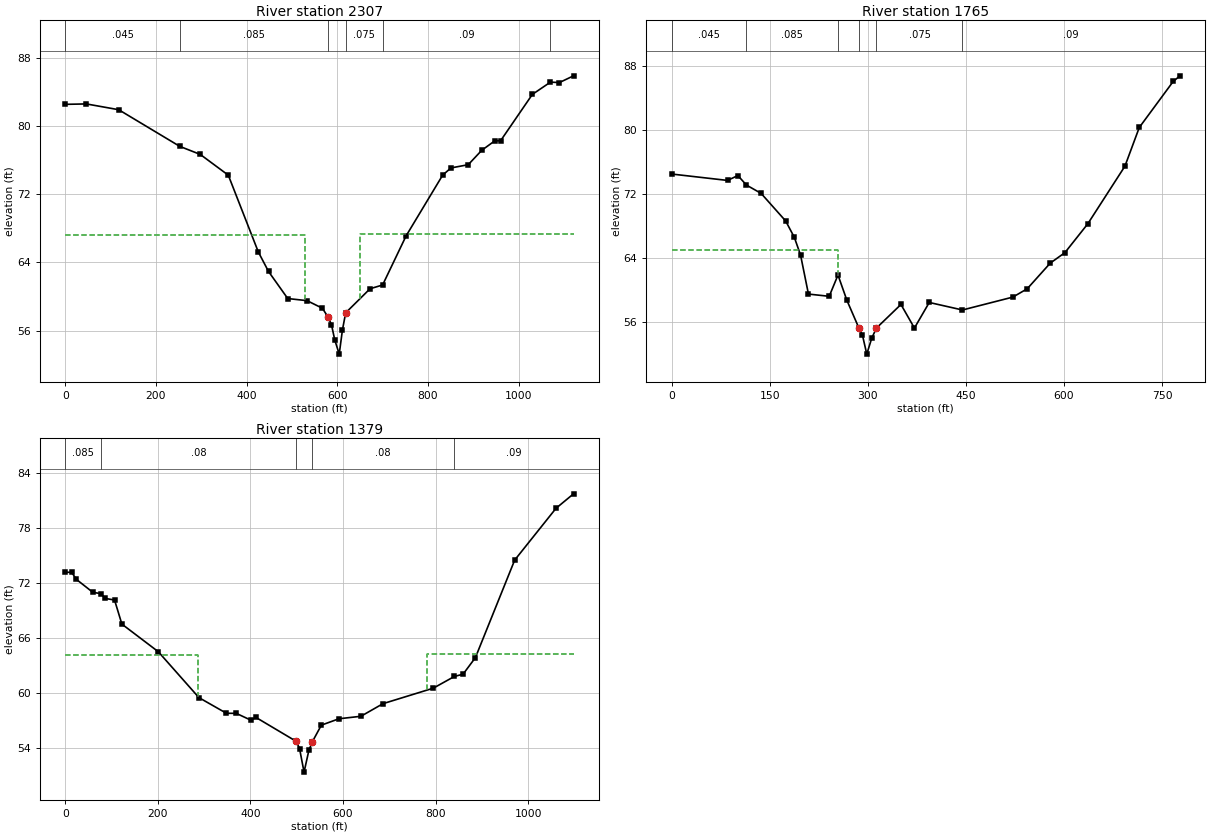
Type RM Length L Ch R = 1 ,2307    ,435.79,541.53,464.66
XS GIS Cut Line= 3
2358762.65684752635179.8432415872359718.06609133635009.550390258
2359866.24298793635036.089535937
#Sta/Elev= 30
       0   82.57   46.56   82.62  117.96   81.94  252.79   77.63  297.78   76.69
  359.66   74.25  425.87   65.23  448.34   62.94  490.75   59.76  533.35   59.51
  567.22   58.62  580.05   57.54  587.17   56.69  594.44    54.9  604.28   53.23
   611.4   56.08  618.53   58.08  672.24   60.91  699.95   61.35  751.78   67.12
  832.46   74.26  850.66    75.1  888.78   75.48  918.56   77.17  947.47   78.29
  960.09   78.29 1030.22   83.74 1070.11   85.18 1089.88   85.13    1121   85.92
#Mann= 6 ,-1 , 0
       0    .045       0  252.79    .085       0  580.05     .05       0
  618.53    .075       0  699.95     .09       0 1070.11    .045       0
#XS Ineff= 2 , 0
       0  529.41   67.25     650       0   67.31
Permanent Ineff=
       F       F
Bank Sta=580.05,618.53
XS Rating Curve= 0 ,0
Exp/Cntr=0.3,0.1

Type RM Length L Ch R = 1 ,1765    ,345.48,385.78,363.26
XS GIS Cut Line= 2
2359007.69876947635517.6573344172359784.87123457635504.062480807
#Sta/Elev= 30
       0   74.52   85.38   73.72  101.22   74.33  114.34   73.14  136.76    72.1
  174.31   68.65  187.58    66.6  197.13   64.37  209.14   59.51  240.89   59.23
  254.32   61.89  267.93   58.73  286.15   55.29  291.69   54.38  298.34      52
  305.94      54  313.13   55.26  350.59   58.21  371.18   55.26  393.86   58.46
  444.64   57.52  521.65   59.13  543.66   60.17  578.89   63.38  601.32   64.69
  636.33    68.3  693.07    75.5  715.02   80.34  766.92    86.1  777.29    86.8
#Mann= 6 ,-1 , 0
       0    .045       0  114.34    .085       0  254.32     .08       0
  286.15     .05       0  313.13    .075       0  444.64     .09       0
#XS Ineff= 2 , 0
       0     254      65               0
Permanent Ineff=
       F       F
Bank Sta=286.15,313.13
XS Rating Curve= 0 ,0
Exp/Cntr=0.3,0.1

Type RM Length L Ch R = 1 ,1379    ,1324.63,1379.39,1269.66
XS GIS Cut Line= 4
2358829.05389617 635618.698251652359137.06229843635841.738818809
2359455.69168004 635873.60175696 2359834.5066116 635753.23065725
#Sta/Elev= 30
       0   73.17   13.83   73.19   24.03   72.41   59.66   70.99   76.86   70.85
   86.93   70.32  106.59   70.15  122.39   67.52  201.14    64.5  288.84   59.49
   348.2   57.78  369.54   57.77  400.84   57.03  411.86   57.33  499.04   54.71
  506.17   53.93  515.91   51.35  526.37   53.74  533.54   54.64  553.25   56.48
  591.32   57.18  638.69   57.45  686.49   58.83  795.04   60.52  840.62    61.8
  859.42   62.05  886.03   63.86  970.85   74.51 1060.16   80.17 1097.98   81.75
#Mann= 5 ,-1 , 0
       0    .085       0   76.86     .08       0  499.04     .05       0
  533.54     .08       0  840.62     .09       0
#XS Ineff= 2 , 0
       0  286.76   64.15  780.88       0   64.24
Permanent Ineff=
       F       F
Bank Sta=499.04,533.54
XS Rating Curve= 0 ,0
Exp/Cntr=0.3,0.1

Chan Stop Cuts=-1
Use User Specified Reach Order=0