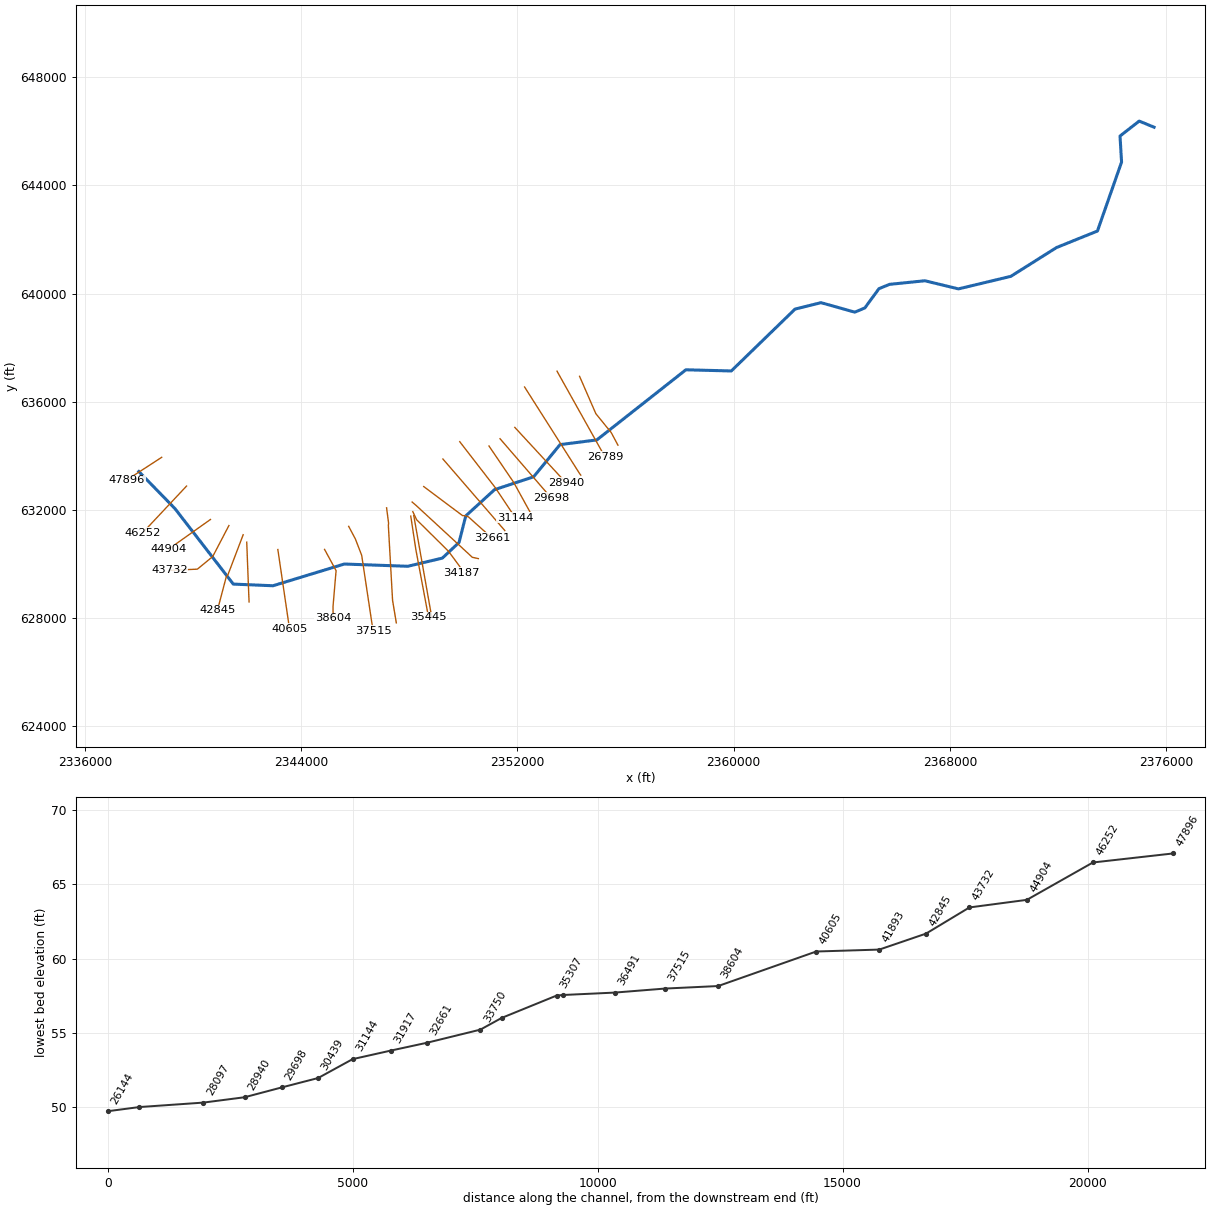
--- DTL_Nahunta_Swamp.prj (project) ---

Proj Title=DTL_Nahunta_Swamp
Current Plan=p01
Default Exp/Contr=0.3,0.1
English Units
Geom File=g01
Geom File=g02
Flow File=f01
Flow File=f02
Plan File=p01
Plan File=p02
Y Axis Title=Elevation
X Axis Title(PF)=Main Channel Distance
X Axis Title(XS)=Station
BEGIN DESCRIPTION:
END DESCRIPTION:
DSS Export Rating Curves= 0
DSS Export Rating Curve Sorted= 0
DSS Export Volume Flow Curves= 0
DXF OffsetX= 0
DXF OffsetY= 0
DXF ScaleX= 1
DXF ScaleY= 10

--- DTL_Nahunta_Swamp.p01 (plan) ---

Plan Title=DTL_Nahunta_Swamp
Program Version=4.00
Short Identifier=Multi_Profile
Geom File=g01
Flow File=f01
Subcritical Flow
K Sum by GR= 0
Std Step Tol= 0.01
Critical Tol= 0.01
Num of Std Step Trials= 20
Max Error Tol= 0.3
Flow Tol Ratio= 0.001
Split Flow NTrial= 30
Split Flow Tol= 0.02
Split Flow Ratio= 0.02
Log Output Level= 0
Friction Slope Method= 1
Unsteady Friction Slope Method= 2
Unsteady Bridges Friction Slope Method= 1
Parabolic Critical Depth
Global Vel Dist= 0 , 0 , 0
Global Log Level= 0
CheckData=True
Encroach Param=-1 ,10,10, 2
Encroach River=Nahunta Swamp
Encroach Reach=Main
Encroach Node=47896
       1     500    1150
Encroach Node=46252
       1     700    1570
Encroach Node=44904
       1     490    1350
Encroach Node=43732
       1    1000    1900
Encroach Node=42845
       4       1
Encroach Node=41893
       4       1
Encroach Node=40605
       1    1120    2100
Encroach Node=38604
       4       1
Encroach Node=37515
       1    1310    2500
Encroach Node=36491
       4       1
Encroach Node=35445
       1  1644.5    2480
Encroach Node=35307
       1  1625.5    2460
Encroach Node=34187
       1    1655    2355
Encroach Node=33750
       1    1715    2450
Encroach Node=32661
       1    1495    2470
Encroach Node=31917
       1    1620    2595
Encroach Node=31144
       1    1720    2645
Encroach Node=30439
       1    1395    2260
Encroach Node=29698
       1    1450    2295
Encroach Node=28940
       1    1390    2275
Encroach Node=28097
       1    2220    3320
Encroach Node=26789
       1    2125    3155
Encroach Node=26144
       1  1768.5  2293.5
Encroach Node=26051
       1  1743.5  2268.5
Encroach Node=25627
       1    1515    2120
Encroach Node=25108
       1    1560    2220
Encroach Node=24118
       1    1350    2040
Encroach Node=23343
       1     710    1400
Encroach Node=22515
       1     670    1460
Encroach Node=21673
       1     830    1620
Encroach Node=20826
       1    1580    2220
Encroach Node=19627
       1    2576    3000
Encroach Node=18434
       1    1520    2400
Encroach Node=17532
       1     840    1720
Encroach Node=16798
       1     900    1590
Encroach Node=16211
       1    1060  1691.8
Encroach Node=15406
       1    1640    2265
Encroach Node=14935
       1 1859.56    2458
Encroach Node=14495
       1    2400    2825
Encroach Node=14426
       1    2250    2705
Encroach Node=14122
       1    1525    2210
Encroach Node=13524
       1    1000    1770
Encroach Node=12851
       1    1190    1985
Encroach Node=12189
       1    1470    2260
Encroach Node=11461
       1    1470    2260
Encroach Node=10640
       1    1580    2340
Encroach Node=9747
       1    1695    2320
Encroach Node=9309
       1    1360    1960
Encroach Node=8783
       1    1315    1890
Encroach Node=7912
       1    1645    2195
Encroach Node=6997
       1    1875    2425
Encroach Node=6001
       1    2160    2620
Encroach Node=5443
       1    1367    1534
Encroach Node=5336
       1    1342  1494.9
Encroach Node=4855
       1     965    1460
Encroach Node=3709
       1     340    1445
Computation Interval=1HOUR
Output Interval=1HOUR
Run HTab= 0
Run UNet= 0
Run PostProcess= 0
Run WQNet= 0
UNET Theta= 1
UNET Theta Warmup= 1
UNET ZTol= 0.02
UNET ZSATol= 0.05
UNET MxIter= 20
UNET MaxInSteps= 0
UNET DtIC= 0
UNET DtMin= 0
UNET MaxCRTS= 20
UNET WFStab= 2
UNET SFStab= 1
UNET WFX= 1
UNET SFX= 1
UNET DSS MLevel= 4
UNET DZMax Abort= 100
UNET Convert EG Bridges= 0
UNET Use Existing IB Tables=-1
UNET Froude Reduction=False
UNET Froude Limit= 1
UNET Froude Power= 10
UNET Time Slicing=0,0, 5
Instantaneous Interval=1HOUR
Write IC File= 0
Echo Input=False
Echo Output=False
Write Detailed= 0
Detailed Automatic Start=False, 10
WQ ULTIMATE=-1
WQ Max Comp Step=1HOUR
WQ Output Interval=15MIN
WQ Output Selected Increments= 0
WQ Output face flow=0
WQ Output face velocity=0
WQ Output face area=0
WQ Output face dispersion=0
WQ Output cell volume=0
WQ Output cell surface area=0
WQ Output cell continuity=0
WQ Output face conc=0
WQ Output face dconc_dx=0
WQ Output face courant=0
WQ Output face peclet=0
WQ Output face adv mass=0
WQ Output face disp mass=0
WQ Output cell mass=0
WQ Output cell source sink temp=0
WQ Output cell source sink nsm=0
WQ Output MaxMinRange=-1
WQ Daily Max Min Mean=-1
WQ Daily Range=0
WQ Daily Time=0
WQ Create Restart=0
WQ Fixed Restart=0
WQ System Summary=False
Sorting and Armoring Iterations= 10
XS Update Threshold= 0.02
Hydraulics Update Threshold= 0.02
Energy Slope Method= 1
Volume Change Method= 0
XS Weighting Method= 0
Number of US Weighted Cross Sections= 1
Number of DS Weighted Cross Sections= 1
Upstream XS Weight=0.25
Main XS Weight=0.5
Downstream XS Weight=0.25
Number of DS XS's Weighted with US Boundary= 1
Upstream Boundary Weight= 1
Weight of XSs Associated with US Boundary= 0
Number of US XS's Weighted with DS Boundary= 1
Downstream Boundary Weight= 0.5
Weight of XSs Associated with DS Boundary= 0.5
Sediment Output Level= 4
Mass or Volume Output= 0
Output Increment Type= 1
Profile and TS Output Increment= 10
XS Output Flag= 0
XS Output Increment= 10
Disregard all LS=0
Disregard all Conn=0
Disregard all Breaches=0
Disregard all Pumps=0

--- DTL_Nahunta_Swamp.p02 (plan) ---

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Plan Title=DTL_Nahunta_Swamp_Future
Short Identifier=Future
Geom File=g01
Flow File=f02
Encroach Param=-1 ,0,0, 0

--- DTL_Nahunta_Swamp.f01 (steady flow) ---

Flow Title=DTL_Nahunta_Swamp
Program Version=4.00
Number of Profiles= 6
Profile Names=100-yr,FW,10-yr,25-yr,50-yr,500-yr
River Rch & RM=Nahunta Swamp,Main            ,47896
    3880    3880    1860    2570    3190    5820
River Rch & RM=Nahunta Swamp,Main            ,41893
    5480    5480    2500    3530    4440    8520
River Rch & RM=Nahunta Swamp,Main            ,38604
    5750    5750    2600    3680    4640    8990
River Rch & RM=Nahunta Swamp,Main            ,34187
    6140    6140    2740    3900    4940    9670
River Rch & RM=Nahunta Swamp,Main            ,33750
    6330    6330    2810    4010    5090   10000
River Rch & RM=Nahunta Swamp,Main            ,28097
    6380    6380    2830    4040    5120   10080
River Rch & RM=Nahunta Swamp,Main            ,26789
    6420    6420    2840    4060    5160   10160
River Rch & RM=Nahunta Swamp,Main            ,25627
    6480    6480    2850    4080    5190   10280
River Rch & RM=Nahunta Swamp,Main            ,20826
    6600    6600    2960    4200    5310   10360
River Rch & RM=Nahunta Swamp,Main            ,13524
    6780    6780    3150    4410    5520   10430
River Rch & RM=Nahunta Swamp,Main            ,9747
    6800    6800    3170    4420    5530   10430
River Rch & RM=Nahunta Swamp,Main            ,6001
    6810    6810    3180    4440    5550   10430
Boundary for River Rch & Prof#=Nahunta Swamp,Main            , 1
Up Type= 0
Dn Type= 3
Dn Slope=0.000244
Boundary for River Rch & Prof#=Nahunta Swamp,Main            , 2
Up Type= 0
Dn Type= 3
Dn Slope=0.000244
Boundary for River Rch & Prof#=Nahunta Swamp,Main            , 3
Up Type= 0
Dn Type= 3
Dn Slope=0.000244
Boundary for River Rch & Prof#=Nahunta Swamp,Main            , 4
Up Type= 0
Dn Type= 3
Dn Slope=0.000244
Boundary for River Rch & Prof#=Nahunta Swamp,Main            , 5
Up Type= 0
Dn Type= 3
Dn Slope=0.000244
Boundary for River Rch & Prof#=Nahunta Swamp,Main            , 6
Up Type= 0
Dn Type= 3
Dn Slope=0.000244
DSS Import GetInterval= 0
DSS Import GetPeak= 0
DSS Import FillOption= 0

--- DTL_Nahunta_Swamp.f02 (steady flow) ---

Flow Title=DTL_Nahunta_Swamp_Future
Program Version=4.00
Number of Profiles= 3
Profile Names=100-yr-10%,100-yr-20%,100-yr-35%
River Rch & RM=Nahunta Swamp,Main            ,47896
    6360    8150    9960
River Rch & RM=Nahunta Swamp,Main            ,41893
    8080   10400   12700
River Rch & RM=Nahunta Swamp,Main            ,38604
    8340   10700   13100
River Rch & RM=Nahunta Swamp,Main            ,34187
    8700   11200   13600
River Rch & RM=Nahunta Swamp,Main            ,33750
    8870   11400   13900
River Rch & RM=Nahunta Swamp,Main            ,28097
    8910   11400   14000
River Rch & RM=Nahunta Swamp,Main            ,26789
    8950   11500   14000
River Rch & RM=Nahunta Swamp,Main            ,25627
    9150   11700   14300
River Rch & RM=Nahunta Swamp,Main            ,20826
    9480   12100   14800
River Rch & RM=Nahunta Swamp,Main            ,13524
   10100   12900   15800
River Rch & RM=Nahunta Swamp,Main            ,9747
   10100   13000   15800
River Rch & RM=Nahunta Swamp,Main            ,6001
   10200   13000   15900
Boundary for River Rch & Prof#=Nahunta Swamp,Main            , 1
Up Type= 0
Dn Type= 3
Dn Slope=0.000244
Boundary for River Rch & Prof#=Nahunta Swamp,Main            , 2
Up Type= 0
Dn Type= 3
Dn Slope=0.000244
Boundary for River Rch & Prof#=Nahunta Swamp,Main            , 3
Up Type= 0
Dn Type= 3
Dn Slope=0.000244
DSS Import GetInterval= 0
DSS Import GetPeak= 0
DSS Import FillOption= 0

--- DTL_Nahunta_Swamp.g01 (geometry) ---

Geom Title=DTL_Nahunta_Swamp
Program Version=4.00

River Reach=Nahunta Swamp   ,Main
Reach XY= 30
2337997.62857755633409.4731753172339331.88169034 632039.85999772
2341492.38165119629242.878869981 2342960.1984383629181.795862079
2345599.13709091629985.8510311692347947.57637547629902.309712783
2349225.16785114630204.4086217282349843.59959269630784.172942281
 2350091.7370382631766.2613993292351157.19013806632739.425228834
2352602.44240867633214.6181218622353580.06855181634407.140414223
2354940.57304522 634579.662674772358235.14288075637176.576702222
2359916.02517094637133.3747197542362274.28247242639423.906149134
2363235.26173086639661.5025956482364483.77809022639310.404661879
2364857.57632142 639467.793390872365378.16980943640179.069377407
2365768.61492544640339.4848126022367076.15205817 640472.65989092
2368320.12835816640171.5026115182370257.22040655640636.102032587
2371949.14924257641703.0160123412373460.98905233 642312.89733696
2374353.86741841644865.9241227212374296.35999821645829.930087462
2375006.12263158646383.817345068 2375556.0787821646157.163930967

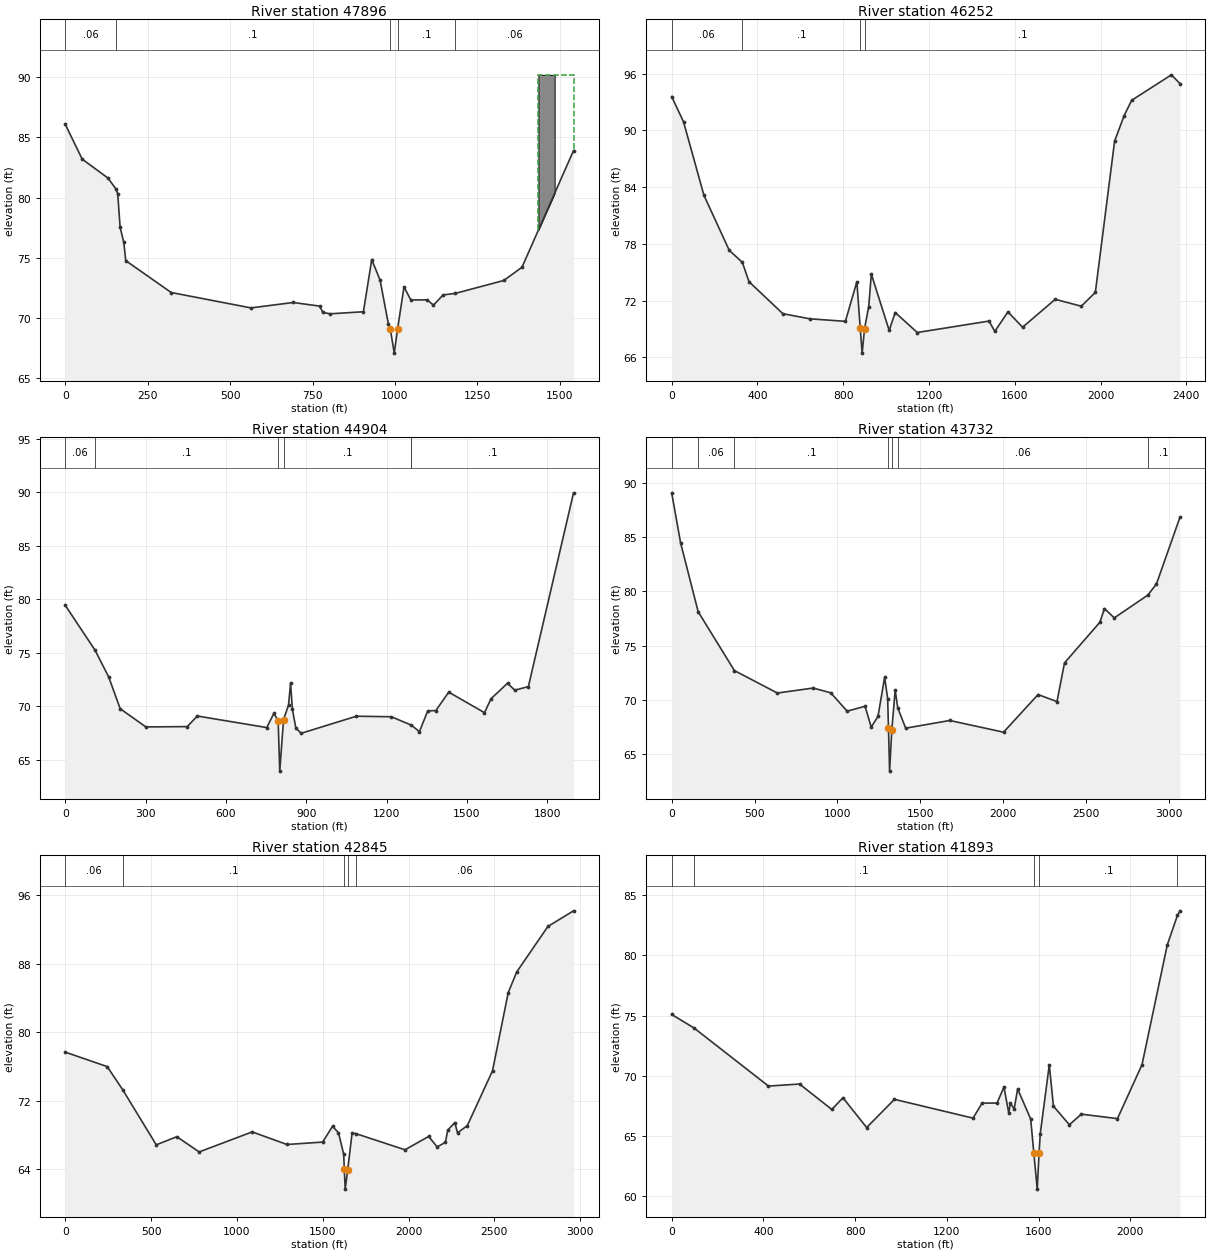
Type RM Length L Ch R = 1 ,47896   ,1534.36,1643.86,1727.95
XS GIS Cut Line= 3
2338843.65104169633936.7343750152337800.03645833633258.385416672
2337560.40104169633083.135416672
#Sta/Elev= 30
       0   86.09   51.45   83.19  129.62   81.62  153.23   80.73  159.27   80.32
  166.51   77.52  177.78   76.26  183.57   74.75  321.51    72.1  563.41   70.82
  691.25   71.27  771.62   70.97  781.66   70.44   803.7   70.33  904.34    70.5
  929.62   74.83  954.82   73.14  979.98    69.5  986.13   69.03  997.91   67.06
 1007.74   69.03 1027.46   72.56 1048.14   71.48 1097.54   71.49 1116.82   71.05
    1146    71.9 1183.47   72.03    1330    73.1 1385.22    74.2 1541.58    83.9
#Mann= 5 ,-1 , 0
       0     .06       0  153.23      .1       0  986.13     .05       0
 1007.74      .1       0 1183.47     .06       0
#XS Ineff= 2 , 0
       0                 1435.09       0    90.2
Permanent Ineff=
       F       F
#Block Obstruct= 1 ,-1
 1435.09  1484.3  90.197
Bank Sta=986.13,1007.74
XS Rating Curve= 0 ,0
Exp/Cntr=0.3,0.1

Type RM Length L Ch R = 1 ,46252   ,1411.14,1348.07,1245.98
XS GIS Cut Line= 2
2339763.42906073632873.1981812272338141.16532159631145.298663706
#Sta/Elev= 30
       0   93.57   55.28    90.9  150.48   83.13  268.65   77.31  329.44   76.05
  360.66      74  518.41   70.62  643.57   70.08  810.02   69.81  863.47      74
  879.05    69.1   888.2   66.45  899.19   69.02  918.66   71.36  930.92    74.8
 1014.08   68.86 1042.32   70.74 1145.16   68.63 1479.65   69.84 1506.58   68.75
 1567.81   70.81 1636.14   69.19 1788.43   72.14  1909.9   71.41 1975.35   72.87
 2065.22   88.86 2109.87   91.57 2144.97   93.18 2329.97   95.87  2370.1   94.94
#Mann= 4 ,-1 , 0
       0     .06       0  329.44      .1       0  879.05     .05       0
  899.19      .1       0
Bank Sta=879.05,899.19
XS Rating Curve= 0 ,0
Exp/Cntr=0.3,0.1

Type RM Length L Ch R = 1 ,44904   ,984.08,1171.92,1210.7
XS GIS Cut Line= 3
2340647.21875001631635.2552083282340000.00000001631176.182291687
2339098.92187501630537.041666687
#Sta/Elev= 30
       0   79.44  111.62   75.23  162.51   72.73   205.3   69.77  301.24   68.07
   455.9    68.1  493.21   69.09  752.66   68.01  779.37   69.34  795.17   68.64
  801.17   63.94  815.27   68.74  834.05   70.13  841.57   72.17   848.4   69.72
  861.44   67.95  881.74   67.48 1087.26   69.07 1217.98   69.02 1293.08   68.23
  1322.8   67.62 1353.74   69.57 1384.09    69.6  1432.2   71.32 1565.74    69.4
 1590.28   70.71 1651.77   72.15 1678.81    71.5 1729.65   71.84 1898.24   89.94
#Mann= 6 ,-1 , 0
       0     .06       0  111.62      .1       0  795.17     .05       0
  815.27      .1       0 1293.08     .05       0 1293.08      .1       0
Bank Sta=795.17,815.27
XS Rating Curve= 0 ,0
Exp/Cntr=0.3,0.1

Type RM Length L Ch R = 1 ,43732   ,760.13,887.18,1140.5
XS GIS Cut Line= 4
2341329.59975713631410.5281335412340730.69931428630262.561193377
2340162.00556245629795.9057941442339126.33923699629750.537330702
#Sta/Elev= 30
       0   89.09   53.83   84.48   159.8   78.13  378.48    72.7  637.91   70.63
   853.8   71.09  959.93   70.65 1058.69   68.96 1166.96   69.41 1203.84   67.49
 1244.87   68.47 1284.88   72.08  1303.2   70.12  1308.1   67.37 1314.96   63.43
  1328.2   67.24 1348.57   70.89 1364.25   69.25    1412   67.39 1678.04    68.1
  2002.4   67.02 2210.72   70.49 2324.77   69.84 2370.31   73.41 2583.81   77.16
 2611.34   78.42 2670.59   77.56 2872.35   79.65 2924.78   80.68 3067.11   86.85
#Mann= 7 ,-1 , 0
       0      .1       0   159.8     .06       0  378.48      .1       0
  1308.1     .05       0  1328.2      .1       0 1364.25     .06       0
 2872.35      .1       0
Bank Sta=1308.1,1328.2
XS Rating Curve= 0 ,0
Exp/Cntr=0.3,0.1

Type RM Length L Ch R = 1 ,42845   ,568.87,951.82,964
XS GIS Cut Line= 4
2341857.77864893631070.9845602662341290.01290861629579.118306071
2341234.75073077629522.7933940892340907.05664368 628279.18184638
#Sta/Elev= 30
       0   77.66  244.67   75.97   335.8   73.24  530.47   66.84  650.19   67.79
   780.3   66.01 1089.31   68.35 1291.57   66.88 1499.68   67.16 1557.14      69
 1591.84   68.26 1622.46   65.72 1625.58   64.07 1631.05   61.67 1645.42   63.88
 1671.01   68.18 1691.4568.16017  1979.5   66.26 2117.34   67.82 2166.63    66.6
 2214.85   67.13 2228.43   68.55 2269.72   69.44 2285.28   68.24 2342.35   69.08
 2489.31   75.48 2580.68    84.6 2630.04   87.01 2812.16   92.33 2961.22   94.15
#Mann= 5 ,-1 , 0
       0     .06       0   335.8      .1       0 1625.58     .05       0
 1645.42      .1       0 1691.45     .06       0
Bank Sta=1625.58,1645.42
XS Rating Curve= 0 ,0
Exp/Cntr=0.3,0.1

Type RM Length L Ch R = 1 ,41893   ,1224.8,1287.83,1339.02
XS GIS Cut Line= 3
2341988.80208333630795.8750000152342019.92708334630000.000000015
2342075.44270833628580.395833343
#Sta/Elev= 30
       0   75.09   96.89   73.98  422.15   69.15  557.68   69.32  698.42   67.21
  747.16   68.18  850.37   65.71  971.77   68.05 1314.38   66.49 1354.19   67.74
 1419.17   67.74 1449.35   69.07 1470.34    66.9 1477.03   67.75 1493.89   67.24
 1508.97   68.91 1565.92   66.42  1579.7   63.59  1594.4    60.6 1602.41   63.59
  1607.6   65.18    1647   70.91 1665.16   67.48 1734.68   65.94 1786.79   66.82
 1944.39   66.45 2051.56   70.93 2161.54   80.85 2206.09   83.32 2217.17   83.69
#Mann= 5 ,-1 , 0
       0     .06       0   96.89      .1       0  1579.7     .05       0
 1602.41      .1       0 2206.09     .06       0
Bank Sta=1579.7,1602.41
XS Rating Curve= 0 ,0
Exp/Cntr=0.3,0.1

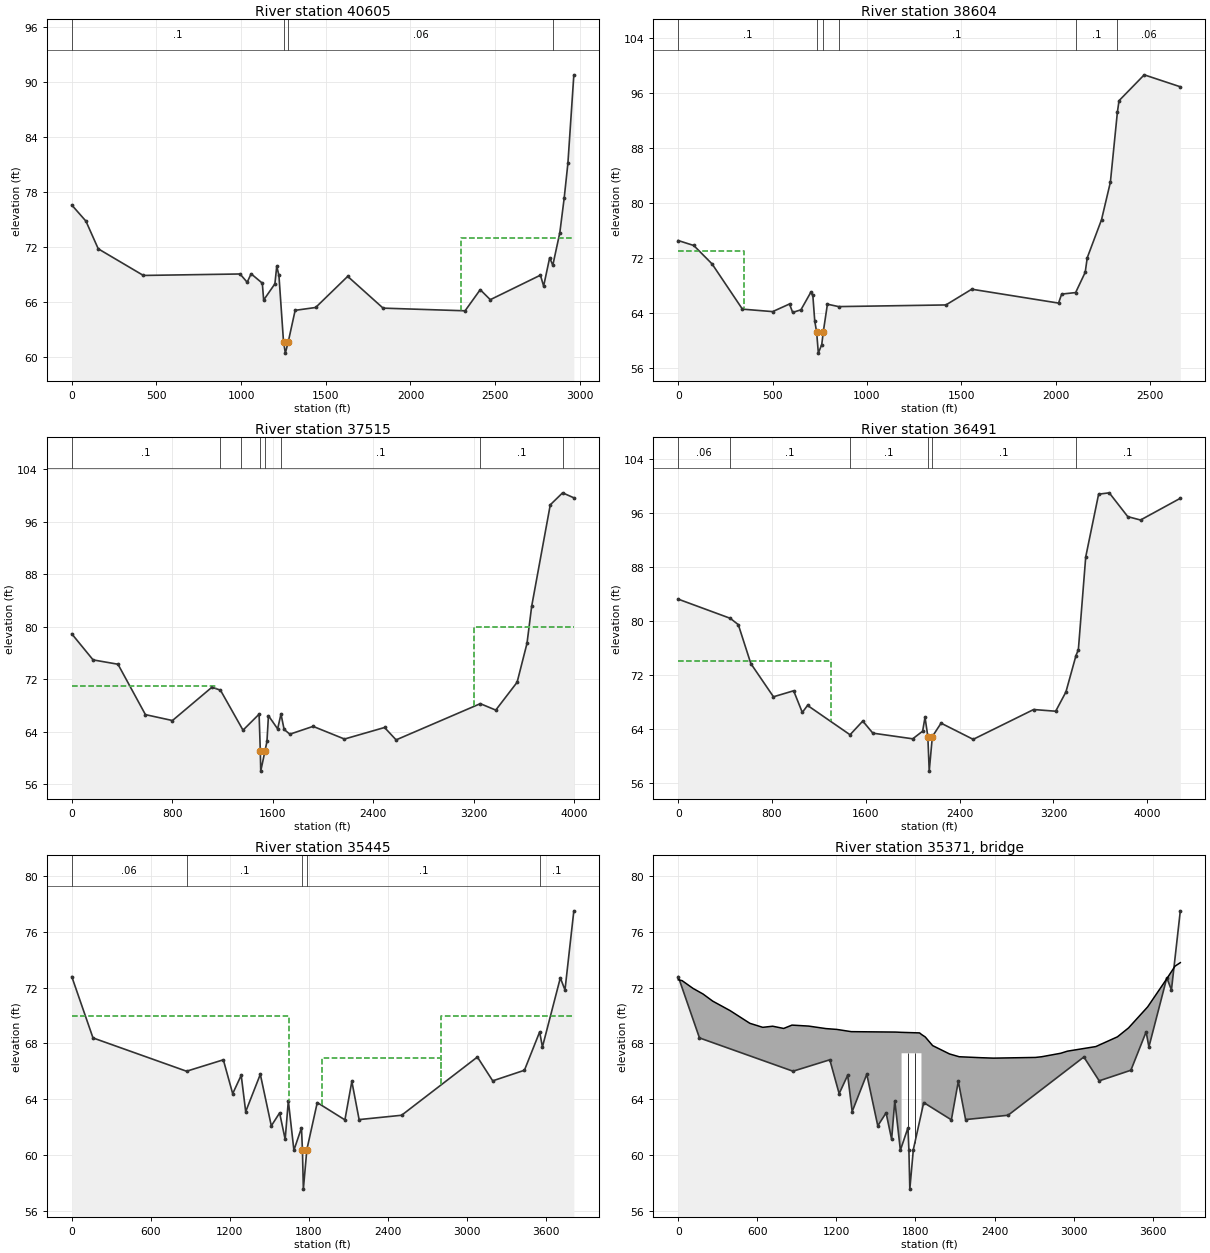
Type RM Length L Ch R = 1 ,40605   ,1913.93,2001.63,1895
XS GIS Cut Line= 3
2343140.48958334630522.0104166872343217.18229167630000.000000015
   2343571.40625627588.989583343
#Sta/Elev= 30
       0    76.6   83.47   74.85  156.36   71.83  422.73   68.93   993.5   69.09
 1035.72   68.19 1058.89   69.11 1125.04   68.09 1133.03   66.25 1199.37   68.02
 1210.32   69.94 1223.18   68.94 1250.33   61.69 1261.09   60.47 1278.08   61.69
 1318.93   65.13 1439.89   65.44 1629.23   68.83 1838.23   65.37 2322.31   65.08
 2411.68   67.38  2471.1   66.29 2767.16   68.96 2786.09   67.77 2821.71   70.86
 2840.29   70.04 2881.69   73.59  2907.6   77.37 2929.39   81.14  2964.5   90.78
#Mann= 4 ,-1 , 0
       0      .1       0 1250.33     .05       0 1278.08     .06       0
 2840.29      .1       0
#XS Ineff= 2 , 0
       0                    2300       0      73
Permanent Ineff=
       F       F
Bank Sta=1250.33,1278.08
XS Rating Curve= 0 ,0
Exp/Cntr=0.3,0.1

Type RM Length L Ch R = 1 ,38604   ,1135.28,1088.48,1161.6
XS GIS Cut Line= 5
  2344869.546875630526.3489583282345154.65104167 630000.00000003
  2345294.859375629741.1614583282345180.42708334628406.119791672
 2345187.3837453627978.705024347
#Sta/Elev= 30
       0   74.53    82.3   73.81  179.24   71.13  340.08   64.55  500.15   64.19
  589.64    65.3  606.24   64.07   650.1   64.45  701.97   66.98  713.28   66.54
  723.43   62.79  733.32   61.24  742.38   58.15   760.5    59.4  768.63   61.25
  790.47   65.27  849.73   64.92 1418.43   65.16 1555.23   67.45 2015.23   65.43
 2031.75   66.74  2105.7   66.96 2156.43   69.91 2167.31   72.03  2242.9   77.56
 2289.87   83.02 2327.04   93.22 2335.69   94.88 2469.16   98.64 2660.39    96.9
#Mann= 6 ,-1 , 0
       0      .1       0  733.32     .05       0  768.63      .1       0
  849.73      .1       0  2105.7      .1       0 2327.04     .06       0
#XS Ineff= 2 , 0
       0     350      73               0
Permanent Ineff=
       F       F
Bank Sta=733.32,768.63
XS Rating Curve= 0 ,0
Exp/Cntr=0.3,0.1

Type RM Length L Ch R = 1 ,37515   ,1048,1023.91,945.52
XS GIS Cut Line= 4
2345761.57042955631379.656923249  2346010.016591  630910.3697294
  2346241.899675630308.5779161162346661.49763656 627520.45988211
#Sta/Elev= 30
       0    78.9   169.7   74.93  367.61   74.27   586.2   66.59  801.18   65.69
 1115.06   70.76 1183.05   70.32 1362.77   64.22 1490.75   66.66 1500.23   61.11
 1503.79   57.98 1538.37   61.12 1553.24    62.5 1565.13   66.43 1638.26   64.42
  1664.966.67546 1689.93   64.33 1735.69   63.61 1920.42    64.8 2170.11   62.87
 2489.23   64.63 2580.94   62.74 3251.08   68.26 3374.05   67.28 3543.89   71.52
 3622.64   77.45 3659.85    83.1 3807.84   98.56 3905.93  100.39 3995.43   99.63
#Mann= 8 ,-1 , 0
       0      .1       0 1183.05      .1       0 1344.46      .1       0
 1500.23     .05       0 1538.37      .1       0  1664.9      .1       0
 3251.08      .1       0 3905.93     .06       0
#XS Ineff= 2 , 0
       0    1150      71    3200       0      80
Permanent Ineff=
       T       F
Bank Sta=1500.23,1538.37
XS Rating Curve= 0 ,0
Exp/Cntr=0.3,0.1

Type RM Length L Ch R = 1 ,36491   ,973.55,1046.9,1107.47
XS GIS Cut Line= 6
2347163.33903968632067.8913092322347237.78645833   631495.515625
2347228.73958333631414.1197916722347308.10416669 630000.00000003
2347384.19791669628644.1770833282347522.77766292627807.553224221
#Sta/Elev= 30
       0    83.2  443.55   80.36  512.29   79.42  619.13   73.65  812.08   68.73
   984.1   69.62 1057.96   66.41 1102.59   67.45  1465.1    63.1 1573.51   65.13
 1659.55   63.34  1999.6    62.5 2084.14   63.63 2104.37   65.69 2128.48   62.84
  2140.3   57.71 2167.02   62.84 2241.31   64.82 2515.14   62.42 3030.67   66.84
 3218.61   66.59 3305.91   69.44 3391.74   74.84 3412.04   75.71 3474.91   89.47
 3584.77   98.76 3675.38   98.96 3833.47   95.43 3942.25   94.93 4281.42   98.15
#Mann= 6 ,-1 , 0
       0     .06       0  443.55      .1       0  1465.1      .1       0
 2128.48     .05       0 2167.02      .1       0 3391.74      .1       0
#XS Ineff= 2 , 0
       0    1300      74               0
Permanent Ineff=
       F       F
Bank Sta=2128.48,2167.02
XS Rating Curve= 0 ,0
Exp/Cntr=0.5,0.3

Type RM Length L Ch R = 1 ,35445   ,142.13,137.99,133.16
XS GIS Cut Line= 3
2348057.94615354631760.8064610722348243.38195162630535.121063981
2348716.01709551628009.123668136
#Sta/Elev= 30
       0    72.8  161.04    68.4  870.84   66.01 1149.98   66.83 1220.92    64.4
 1285.65   65.72 1319.61   63.11 1430.59   65.79 1514.04   62.09 1577.05   63.02
 1619.15   61.12 1643.17   63.89 1685.49   60.34 1742.87   61.95 1750.03   60.39
 1757.16   57.55  1783.8   60.39 1862.65   63.76 2072.44   62.52 2125.05   65.28
 2180.27   62.54 2502.53   62.85 3077.55   67.03 3193.92   65.32 3434.53   66.08
 3550.04   68.83 3571.09   67.75 3707.01   72.71 3742.22   71.84 3809.47   77.52
#Mann= 5 ,-1 , 0
       0     .06       0  870.84      .1       0 1750.03     .05       0
  1783.8      .1       0 3550.04      .1       0
#XS Ineff= 3 ,-1
       0  1644.5      70  1895.5    2800   66.95    2800    3810      70
Permanent Ineff=
       F       F       F
Bank Sta=1750.03,1783.8
XS Rating Curve= 0 ,0
Exp/Cntr=0.5,0.3

Type RM Length L Ch R = 3 ,35371   ,,,
Bridge Culvert--1,0,-1,-1, 0
Deck Dist Width WeirC Skew NumUp NumDn MinLoCord MaxHiCord MaxSubmerge Is_Ogee
62,27,2.6,0, 38, 38, , , 0.98, 0, 1,1,,
       0   29.52  111.22  188.33  261.65   393.4  543.29  641.08  716.59  800.02
  862.97  989.01 1120.24 1203.55 1312.87  1649.5  1694.5  1694.5 1831.16  1845.5
  1845.5 1874.01 1930.07 2058.35 2131.73  2298.1 2392.17 2710.45 2757.79 2902.08
 2952.84 3168.31 3332.63 3416.74  3561.9  3702.1 3769.33 3809.47
   72.57   72.51   71.96   71.55   71.04   70.36   69.45   69.16   69.24   69.08
   69.32   69.25   69.07   69.01   68.85   68.82    68.8    68.8   68.76   68.65
   68.65   68.47   67.85   67.25   67.05   66.98   66.95      67   67.05    67.3
   67.45   67.78   68.48   69.12   70.63   72.58   73.55    73.8
                                                                                
                                                       0    67.3    67.3    67.3
       0
                                                                
       0   29.52  111.22  188.33  261.65   393.4  543.29  641.08  716.59  800.02
  862.97  989.01 1120.24 1203.55 1312.87  1649.5  1675.5  1675.5  1826.5  1826.5
 1831.16 1874.01 1930.07 2058.35 2131.73  2298.1 2392.17 2710.45 2757.79 2902.08
 2952.84 3168.31 3332.63 3416.74  3561.9  3702.1 3769.33 3809.47
   72.57   72.51   71.96   71.55   71.04   70.36   69.45   69.16   69.24   69.08
   69.32   69.25   69.07   69.01   68.85   68.82    68.8    68.8   68.76   68.76
   68.76   68.47   67.85   67.25   67.05   66.98   66.95      67   67.05    67.3
   67.45   67.78   68.48   69.12   70.63   72.58   73.55    73.8
                                                                                
                                                       0    67.3    67.3       0
                                                                                
                                                                
Pier Skew, UpSta & Num, DnSta & Num=  ,1744.83, 2 ,1725.83, 2 , 0 , 0 , 0 ,,
       2       2
      55    67.3
       2       2
      55    67.3
Pier Skew, UpSta & Num, DnSta & Num=  ,1795.17, 2 ,1776.17, 2 , 0 , 0 , 0 ,,
       2       2
      55    67.3
       2       2
      55    67.3
Abutment Skew #Up #Dn= , 2 , 2
  1694.5 1742.87
    67.3   61.95
  1675.5 1729.82
    67.3    62.1
Abutment Skew #Up #Dn= , 2 , 2
 1801.44  1845.5
   62.31    67.3
 1771.22  1826.5
   61.74    67.3
BR Coef=-1 , 0 , 0 ,, 0 ,,,0.8,-1,,0,
WSPro=,,,, 1 ,,,, 0 ,,,, 0 ,,,,-1 ,-1 ,-1 , 0 , 0 , 0 , 0 , 0
BC Design=,, 0 ,, 0 ,,,,,,
BC Use User HTab Curves=0
BC User HTab FreeFlow(D)= 0

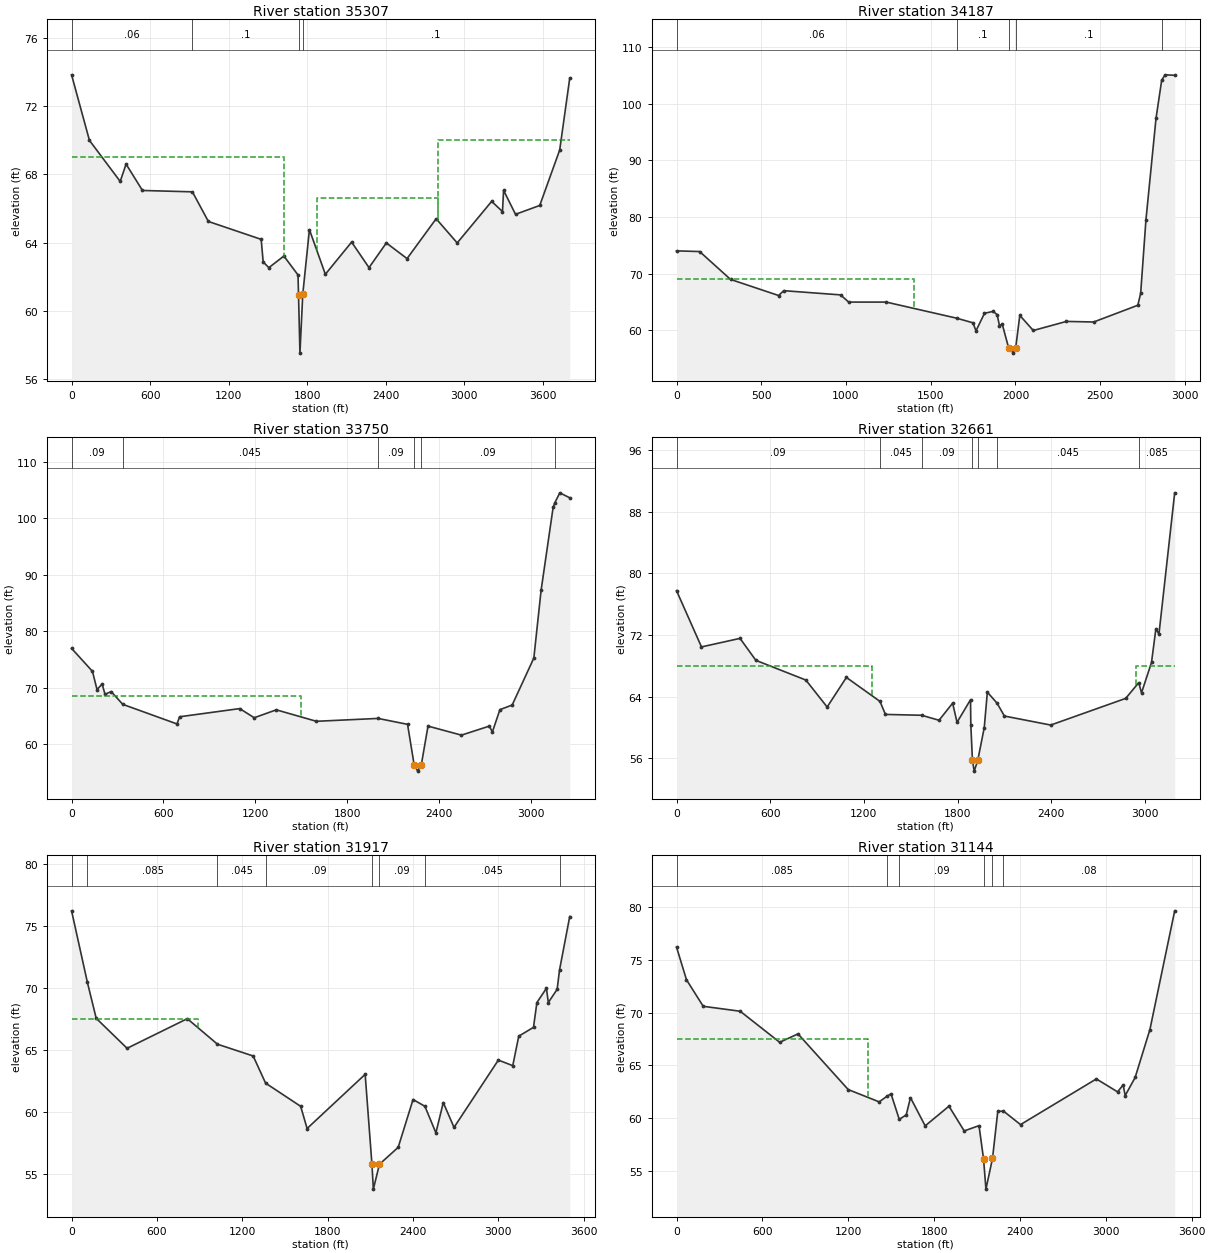
Type RM Length L Ch R = 1 ,35307   ,653.45,1119.19,1264.4
XS GIS Cut Line= 2
2348168.75534996631778.897758439 2348831.1420856628031.427967727
#Sta/Elev= 30
       0   73.85  136.49      70   371.6   67.59  416.35   68.61  541.47   67.06
  923.08   66.98 1045.11   65.24  1448.5   64.19 1463.82   62.86 1507.31   62.53
 1621.87   63.21 1729.82    62.1 1733.76   60.94 1744.59   57.51 1766.19   60.97
 1816.97   64.76 1938.74   62.14 2139.43   64.03 2272.14   62.53 2404.69   63.98
 2562.89   63.06  2785.2    65.4    2946   63.98 3209.25   66.42 3291.93   65.82
 3300.25   67.07 3391.51   65.66 3576.62   66.18 3729.11   69.44 3805.56   73.65
#Mann= 4 ,-1 , 0
       0     .06       0  923.08      .1       0 1733.76     .05       0
 1766.19      .1       0
#XS Ineff= 3 ,-1
       0  1625.5      69  1876.5    2800    66.6    2800    3810      70
Permanent Ineff=
       F       F       F
Bank Sta=1733.76,1766.19
XS Rating Curve= 0 ,0
Exp/Cntr=0.5,0.3

Type RM Length L Ch R = 1 ,34187   ,418.51,437.81,493.24
XS GIS Cut Line= 5
 2348132.5727552631925.8895495982348275.06518134631625.168185115
2349451.64112349630460.3153654342349874.98375389629888.219969347
2349941.28556225629658.157939285
#Sta/Elev= 30
       0   74.04  136.43   73.92  318.58   69.01  602.08   66.17  632.84   67.02
  967.61   66.28 1015.87   65.01 1237.28   65.01 1653.21   62.17 1748.48   61.36
 1767.18   59.95 1817.16   63.03 1867.48   63.37 1891.67   62.81 1905.47   60.88
 1922.35   61.07 1959.66   56.93 1987.89   56.01 2001.07    56.9 2025.61   62.66
 2105.11      60 2300.81    61.6 2461.57    61.5 2721.89   64.45 2738.74   66.55
 2769.89   79.51 2829.37   97.41 2862.83  104.13 2882.62  105.08  2939.5     105
#Mann= 5 ,-1 , 0
       0     .06       0 1653.21      .1       0 1959.66     .05       0
 2001.07      .1       0 2862.83     .06       0
#XS Ineff= 2 , 0
       0    1400      69               0
Permanent Ineff=
       T       F
Bank Sta=1959.66,2001.07
XS Rating Curve= 0 ,0
Exp/Cntr=0.3,0.1

Type RM Length L Ch R = 1 ,33750   ,861.13,1088.84,1021.79
XS GIS Cut Line= 6
2348108.92440599632279.7589911672348240.92708333632168.322916701
2349484.50000004631020.500000015        2350000.      630544.625
2350336.00000003 630234.500000032350558.40878652630186.159099951
#Sta/Elev= 30
       0   76.95  136.39   72.88  166.02   69.66   199.3   70.64  218.29   68.82
  258.42    69.3  334.25   67.04  688.16   63.57  704.92   64.84 1097.47   66.29
 1192.11   64.67 1336.33   66.07 1597.87   64.04 2000.64   64.55 2193.01    63.5
 2235.74   56.38 2259.66   55.22 2282.8756.35627 2326.49   63.19 2544.66   61.59
 2726.81   63.19 2746.59   62.15 2795.91    66.1 2875.79   66.92 3017.24   75.23
  3064.8   87.25 3143.28  101.92 3154.92  102.75 3186.62  104.48 3251.49   103.6
#Mann= 6 ,-1 , 0
       0     .09       0  334.25    .045       0 2000.64     .09       0
 2235.74     .05       0 2282.87     .09       0 3154.92    .045       0
#XS Ineff= 2 , 0
       0    1500    68.5               0
Permanent Ineff=
       F       F
Bank Sta=2235.74,2282.87
XS Rating Curve= 0 ,0
Exp/Cntr=0.3,0.1

Type RM Length L Ch R = 1 ,32661   ,920.22,743.26,626.71
BEGIN DESCRIPTION:
Surveyed Section
END DESCRIPTION:
XS GIS Cut Line= 6
2348536.65931447632854.441537529    2349974.7677631777.559599996
2350007.84340002631778.7351000162350071.26729999631771.769999996
    2350190.9804631730.5752999932351061.67506441630949.641404837
#Sta/Elev= 30
       0   77.76  159.74   70.46  406.58   71.57  508.02   68.72   828.3   66.16
  964.53   62.66 1087.91    66.5 1302.91   63.39 1337.83    61.7 1569.94   61.59
 1681.06   60.94 1768.21   63.161796.454   60.671882.793   63.611884.678   60.36
1895.053   55.72 1906.31   54.341929.517   55.771970.811      601990.496   64.59
 2052.95   63.16 2099.61   61.49 2396.39   60.32 2876.48   63.78 2959.95   65.82
 2977.84    64.5 3041.81   68.44 3069.92   72.82 3089.51   72.13 3190.29   90.46
#Mann= 7 ,-1 , 0
       0     .09       0 1302.91    .045       0 1569.94     .09       0
1895.053     .05       01929.517     .09       0 2052.95    .045       0
 2959.95    .085       0
#XS Ineff= 2 , 0
       0    1250      68    2945       0      68
Permanent Ineff=
       F       F
Bank Sta=1895.053,1929.517
XS Rating Curve= 0 ,0
Exp/Cntr=0.3,0.1

Type RM Length L Ch R = 1 ,31917   ,814.08,773.63,686.13
XS GIS Cut Line= 2
2349245.87138848633874.7962626962351536.32283381631225.599410281
#Sta/Elev= 30
       0   76.26  111.37   70.48  173.16   67.59  390.26   65.17  813.55   67.56
 1025.75    65.5 1276.52   64.55 1364.05   62.36 1610.54   60.49 1655.77    58.7
 2063.98   63.07 2111.68    55.8 2121.62   53.81 2164.2755.81558 2296.09   57.18
 2400.72   61.04 2484.01   60.49 2561.23   58.35 2613.06   60.79 2688.76   58.79
 3000.33   64.22 3101.59   63.77 3143.75   66.15  3247.4   66.86 3271.27   68.86
 3338.32   70.01 3351.63   68.86 3413.69   69.93 3430.27   71.48 3502.06    75.8
#Mann= 8 ,-1 , 0
       0     .09       0  111.37    .085       0 1025.75    .045       0
 1364.05     .09       0 2111.68     .05       0 2164.27     .09       0
 2484.01    .045       0 3430.27    .085       0
#XS Ineff= 2 , 0
       0     890    67.5               0
Permanent Ineff=
       F       F
Bank Sta=2111.68,2164.27
XS Rating Curve= 0 ,0
Exp/Cntr=0.3,0.1

Type RM Length L Ch R = 1 ,31144   ,701.37,704.58,633.79
XS GIS Cut Line= 3
2349869.53648084634515.0188353812351183.09658682632815.117521748
2351922.66404146631705.766339779
#Sta/Elev= 30
       0   76.23   69.52   73.13  186.53   70.61  444.95   70.14  720.98   67.19
  848.82   67.99 1199.73    62.7 1416.25   61.53    1472   62.08 1499.09   62.29
  1556.6   59.87 1605.25   60.29 1635.02   61.93  1737.7   59.25 1903.91   61.12
 2010.42   58.77 2113.88   59.27 2145.62   56.13 2162.35   53.24 2208.21   56.15
 2245.15   60.62  2284.660.65749 2404.07   59.37 2934.22   63.71 3082.38   62.48
  3121.4   63.14 3135.73   62.13 3205.21   63.85 3308.37    68.4 3481.55   79.68
#Mann= 6 ,-1 , 0
       0    .085       0    1472    .075       0  1556.6     .09       0
 2145.62     .05       0 2208.21     .09       0  2284.6     .08       0
#XS Ineff= 2 , 0
       0    1335    67.5               0
Permanent Ineff=
       F       F
Bank Sta=2145.62,2208.21
XS Rating Curve= 0 ,0
Exp/Cntr=0.3,0.1

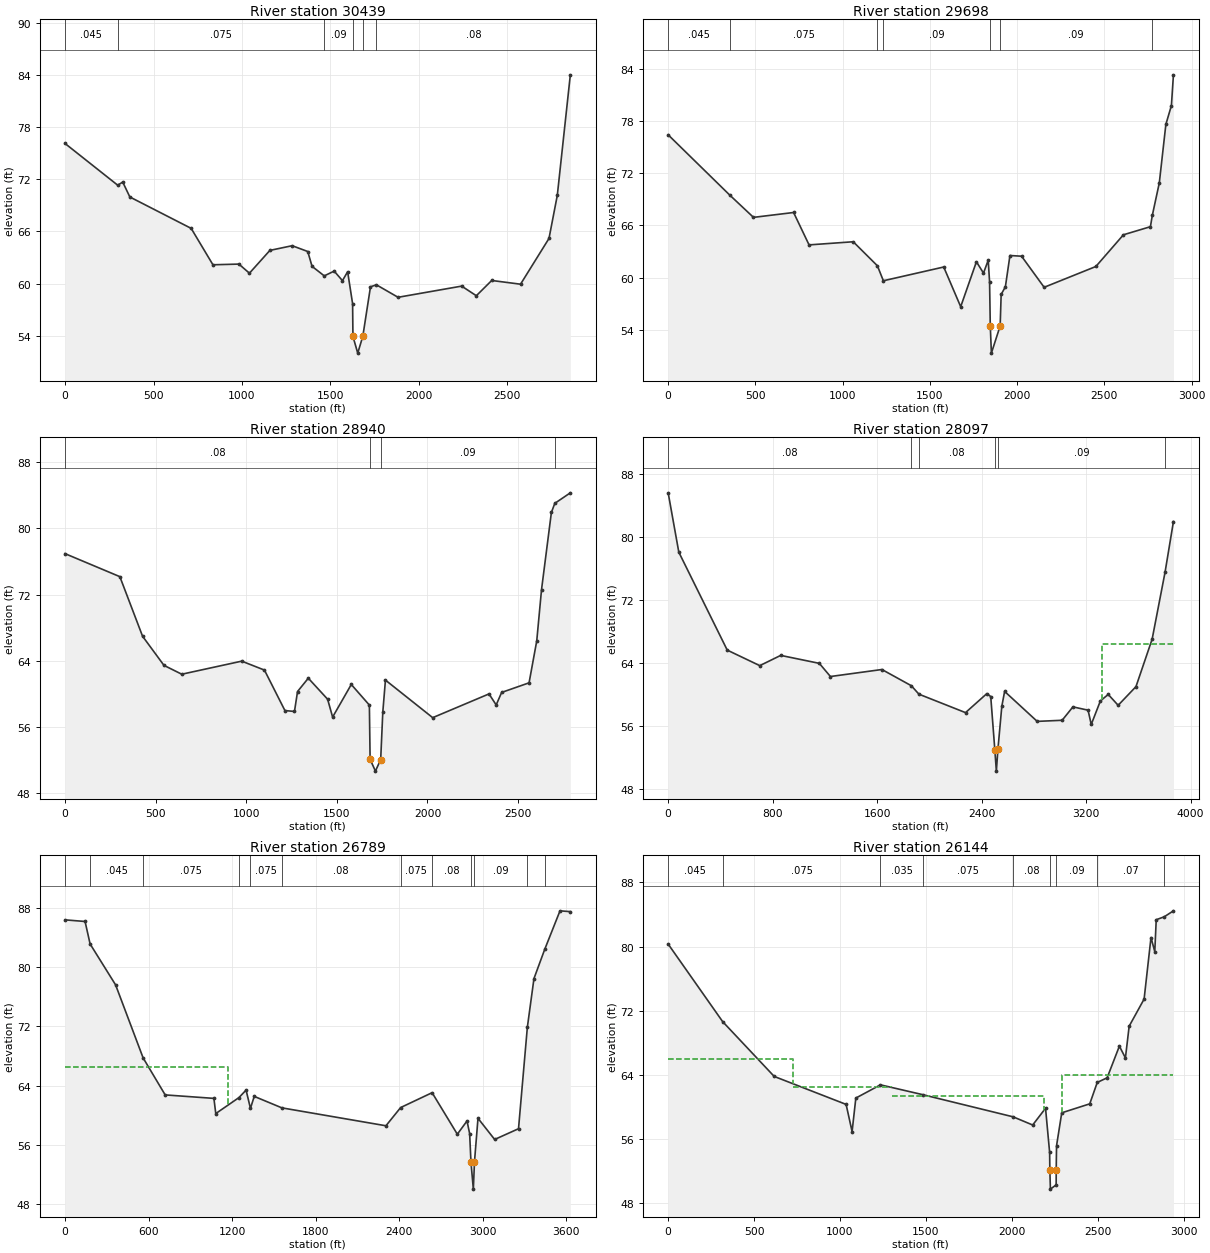
Type RM Length L Ch R = 1 ,30439   ,642.52,741.68,813.34
XS GIS Cut Line= 3
2350951.29186223634354.9631921952351866.00207751633007.290141732
2352458.02257204631932.051904276
#Sta/Elev= 30
       0   76.15  297.62   71.34  326.07    71.7  366.31   69.98  712.85   66.36
  835.97   62.16  982.62   62.24 1042.26   61.19 1157.95   63.82 1283.89   64.36
    1372   63.69 1396.22   61.98 1465.24   60.88 1521.17   61.43 1568.08   60.33
 1597.43   61.36 1625.45   57.67 1627.36    53.9 1654.46   51.97 1683.18   53.91
 1726.54   59.62 1760.01   59.85 1882.43   58.41 2241.96    59.7 2324.89   58.59
 2411.83   60.35 2574.77   59.92 2735.64    65.2  2782.6   70.17 2856.22   84.07
#Mann= 6 ,-1 , 0
       0    .045       0  297.62    .075       0 1465.24     .09       0
 1627.36     .05       0 1683.18     .09       0 1760.01     .08       0
Bank Sta=1627.36,1683.18
XS Rating Curve= 0 ,0
Exp/Cntr=0.3,0.1

Type RM Length L Ch R = 1 ,29698   ,734.11,757.87,766.73
XS GIS Cut Line= 2
2351359.70971031634625.4020375452353252.78162779632434.295474208
#Sta/Elev= 30
       0   76.41   352.4    69.5  488.92   66.93  718.85   67.49  807.41   63.77
 1060.54   64.13 1199.08   61.37 1233.25   59.65 1579.16   61.23  1676.4   56.67
 1766.51   61.83 1807.09   60.53 1834.15   62.01  1841.9   59.53 1846.01   54.47
 1852.33   51.34 1902.64   54.47 1908.27   58.08 1932.55   58.96 1958.65   62.55
 2025.25   62.47 2154.63    58.9 2451.12   61.29 2609.01   64.93  2763.7   65.86
 2774.59   67.16 2814.61   70.89 2852.26   77.61 2883.94   79.77 2895.63    83.3
#Mann= 7 ,-1 , 0
       0    .045       0   352.4    .075       0 1199.08     .08       0
 1233.25     .09       0 1846.01     .05       0 1902.64     .09       0
 2774.59     .08       0
Bank Sta=1846.01,1902.64
XS Rating Curve= 0 ,0
Exp/Cntr=0.3,0.1

Type RM Length L Ch R = 1 ,28940   ,945.12,842.68,746.78
XS GIS Cut Line= 2
2351906.10656114 635044.858205872353799.17847858632997.249805331
#Sta/Elev= 30
       0   76.96  302.42   74.18  427.77   66.98  545.89   63.46  644.23   62.39
  975.08   63.97 1100.44   62.89 1213.42      58 1266.12   57.89 1283.12    60.3
 1342.48   61.91 1449.05   59.37 1476.72   57.21  1579.7   61.15 1679.54   58.66
 1683.54   52.11 1712.95   50.68 1741.97   52.08 1753.64   57.81 1768.21   61.68
 2029.04   57.14 2339.72   60.01 2379.38   58.68 2409.52   60.19 2560.88   61.35
 2603.29   66.42 2629.64   72.61 2684.08   81.94 2703.01   83.04 2788.62   84.31
#Mann= 4 ,-1 , 0
       0     .08       0 1683.54     .05       0 1741.97     .09       0
 2703.01    .045       0
Bank Sta=1683.54,1741.97
XS Rating Curve= 0 ,0
Exp/Cntr=0.3,0.1

Type RM Length L Ch R = 1 ,28097   ,1227.49,1308,1197.58
XS GIS Cut Line= 4
2352269.10093805636538.9736038742352412.25000003636313.250000015
2354298.25000001 633343.125000032354348.17445751633276.121381938
#Sta/Elev= 30
       0   85.62   81.52   78.09  452.36   65.67  701.51    63.7  861.82      65
 1157.51   63.99 1242.51   62.32 1636.75   63.21 1861.8561.15503 1920.27   60.08
 2277.01   57.74 2440.07   60.15 2470.09   59.78 2501.33   53.05 2513.16   50.32
 2525.0253.07098 2554.99   58.55 2576.51   60.43 2825.94   56.63 3016.88   56.77
 3099.52   58.47 3215.45   58.05 3239.76   56.24 3309.68   59.22 3369.73   60.05
 3445.74   58.67 3582.32   61.04 3706.04   67.06 3804.95   75.55 3869.18   81.98
#Mann= 6 ,-1 , 0
       0     .08       0 1861.85    .075       0 1920.27     .08       0
 2501.33     .05       0 2525.02     .09       0 3804.95     .08       0
#XS Ineff= 2 , 0
       0                    3320       0    66.5
Permanent Ineff=
       F       F
Bank Sta=2501.33,2525.02
XS Rating Curve= 0 ,0
Exp/Cntr=0.3,0.1

Type RM Length L Ch R = 1 ,26789   ,507.52,644.98,651.81
XS GIS Cut Line= 2
2353468.02887204637125.5815670192355239.67926708633957.583664358
#Sta/Elev= 30
       0    86.4  143.75   86.18  180.03   83.14  362.94   77.62  560.7967.74866
  719.16   62.75 1069.21   62.28 1082.67   60.23 1248.63   62.38 1300.34    63.4
 1331.75   60.93 1358.99   62.55 1557.52      61 2305.08   58.58 2410.51   61.04
 2636.64   63.05  2817.8   57.44 2887.46   59.23 2906.24   57.53 2915.78   53.67
 2932.81   50.02 2941.16   53.74 2966.24   59.59 3085.91   56.73 3257.33   58.18
 3320.84   71.89 3368.39   78.47  3445.7   82.42 3555.36   87.62 3629.57   87.51
#Mann= 12 ,-1 , 0
       0    .085       0  180.03    .045       0  560.79    .075       0
 1248.63    .035       0 1331.75    .075       0 1557.52     .08       0
 2410.51    .075       0 2636.64     .08       0 2915.78     .05       0
 2941.16     .09       0 3320.84     .07       0  3445.7    .045       0
#XS Ineff= 2 , 0
       0    1170    66.5               0
Permanent Ineff=
       F       F
Bank Sta=2915.78,2941.16
XS Rating Curve= 0 ,0
Exp/Cntr=0.5,0.3

Type RM Length L Ch R = 1 ,26144   ,102.86,92.51,89.94
BEGIN DESCRIPTION:
Surveyed Section
END DESCRIPTION:
XS GIS Cut Line= 6
2354303.00475803636934.6000574232354904.51180325635552.902991727
2355321.77223252635038.5973526392355404.85102324634948.926331341
 2355488.7707064634824.0356653032355721.94510618634385.789317802
#Sta/Elev= 30
       0   80.31  316.99   70.64  617.14    63.8 1035.61   60.31 1070.39   56.92
 1092.17    61.1 1235.33   62.75 1480.58   61.53 2007.53   58.76 2121.39   57.74
2196.209   59.832220.056   54.312221.307    52.12224.555   49.742258.023   50.27
 2258.37   52.152260.247   55.152290.524   59.26 2453.54   60.38 2497.13   63.05
 2554.66   63.63 2625.97   67.58 2661.09   66.11 2682.88   70.07 2769.85   73.45
 2809.92   81.13 2831.99   79.37 2840.34   83.35 2887.34   83.72 2940.57   84.46
#Mann= 9 ,-1 , 0
       0    .045       0  316.99    .075       0 1235.33    .035       0
 1480.58    .075       0 2007.53     .08       02221.307     .05       0
 2258.37     .09       0 2497.13     .07       0 2887.34    .045       0
#XS Ineff= 4 ,-1
       0     725      66     725    1300    62.5    1300  2184.5    61.3
  2293.5    2950   63.93
Permanent Ineff=
       F       T       F       F
Bank Sta=2221.307,2258.37
XS Rating Curve= 0 ,0
Exp/Cntr=0.5,0.3