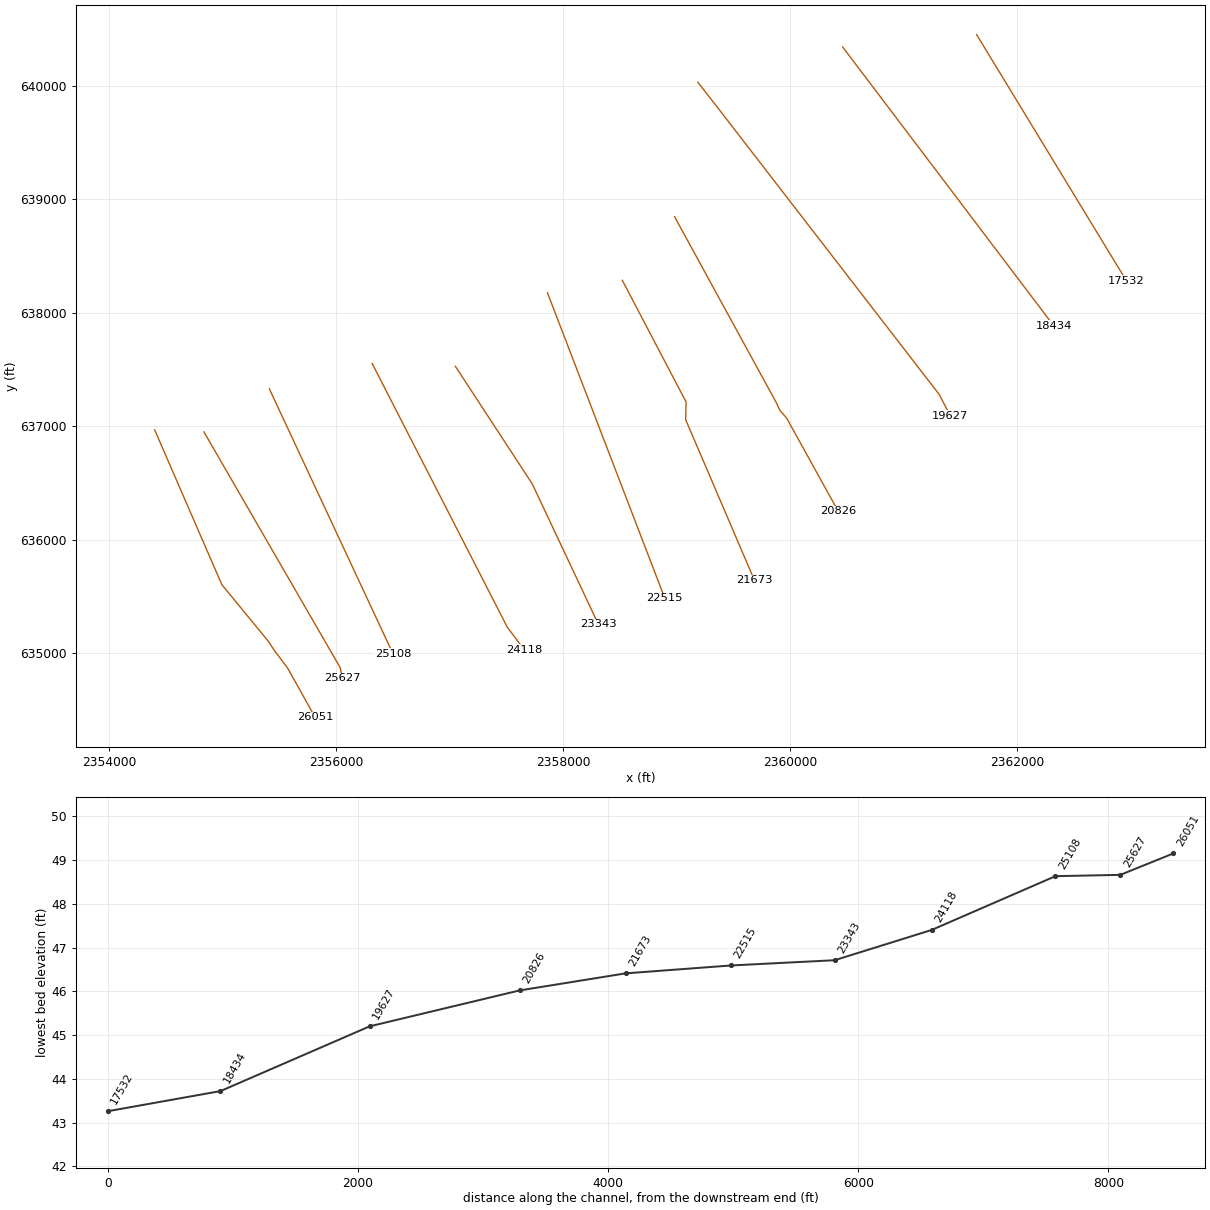
HEC-RAS study DTL_Nahunta_Swamp.prj: DTL_Nahunta_Swamp

--- DTL_Nahunta_Swamp.g01 (geometry) --- (continued)

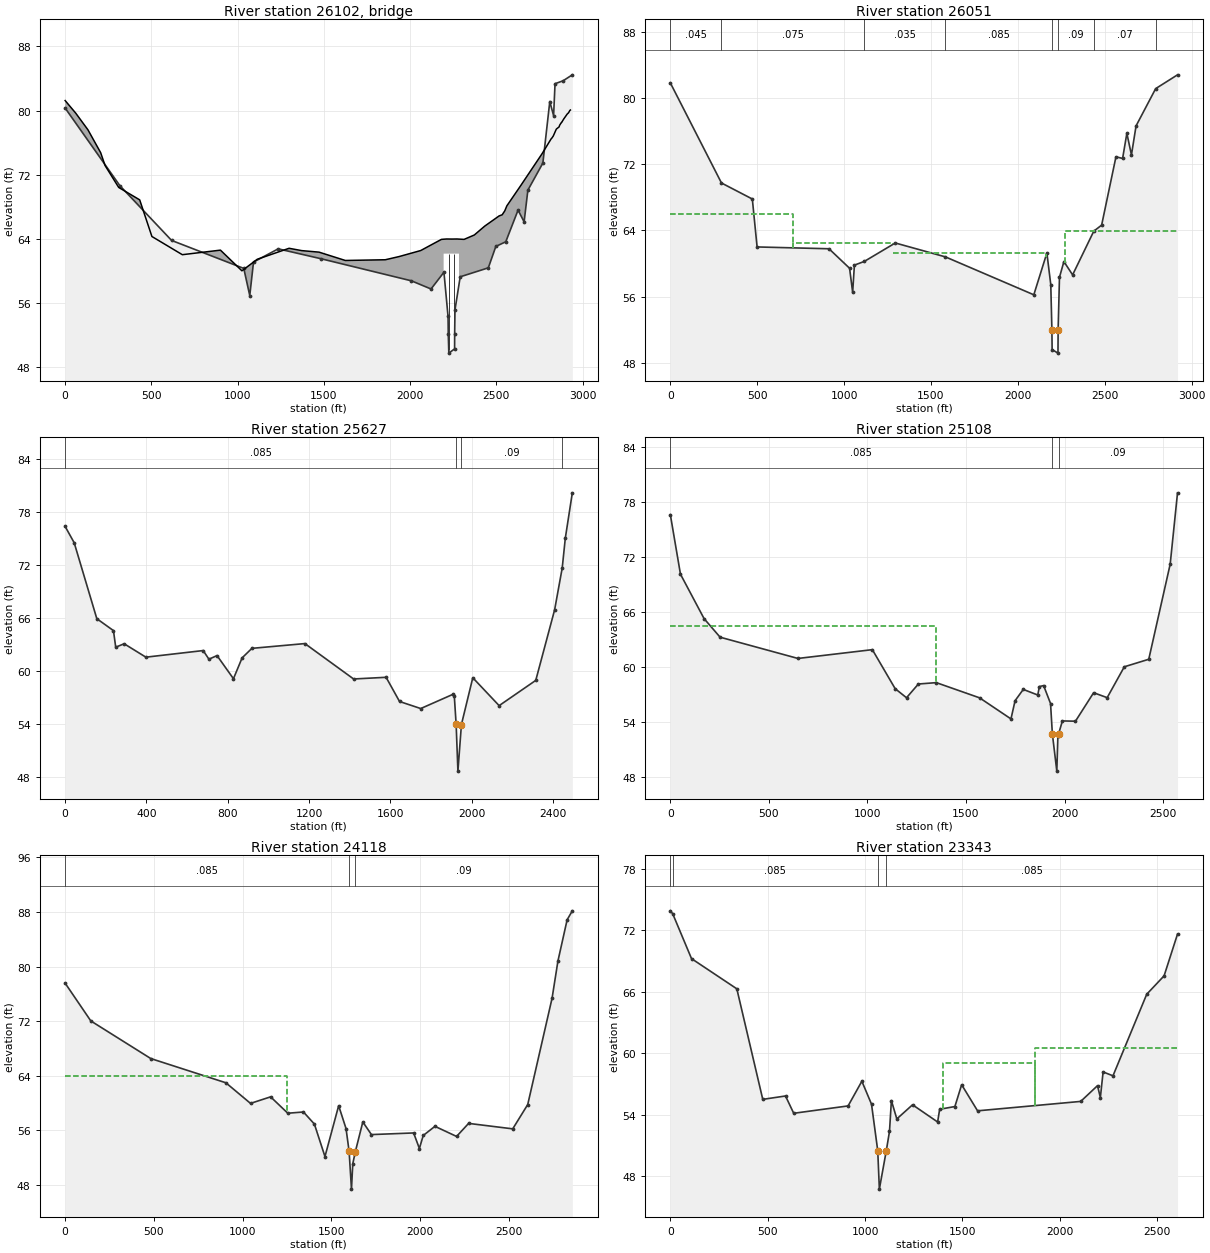
Type RM Length L Ch R = 3 ,26102   ,,,
BEGIN DESCRIPTION:
Bullhead (SR 1058)
END DESCRIPTION:
Bridge Culvert--1,0,-1,-1, 0
Deck Dist Width WeirC Skew NumUp NumDn MinLoCord MaxHiCord MaxSubmerge Is_Ogee
15.78,30,2.6,0, 55, 55, , , 0.98, 0, 1,1,,
       0    61.3  132.19  205.86  231.35  310.55  432.24  503.02  679.44  900.36
 1024.91 1113.83 1298.33  1371.4 1471.75 1624.46 1856.27  1936.62061.6372122.699
2181.584  2194.5  2194.52211.0752241.365 2271.43  2283.5  2283.52312.9742372.398
 2432.87 2516.21 2533.83 2548.85 2560.83 2641.31 2765.18 2817.65  2821.7 2830.16
 2846.82 2847.53 2848.22 2849.63 2863.69 2867.49 2877.16 2878.42 2886.16 2890.09
 2890.72 2911.34 2918.52 2926.37 2929.39
   81.25   79.68    77.6   74.75   73.15   70.41   68.86   64.29   62.02   62.59
   60.01   61.45   62.82   62.53   62.34    61.3   61.39   61.79   62.54   63.25
   63.93  63.952  63.952   63.98   63.97   63.98  63.965  63.965   63.93   64.48
   65.59   66.86      67   67.49   68.11   70.64   74.62   76.47   76.56   76.83
   77.64   77.67   77.69   77.72   77.96   78.19   78.51   78.51   78.79   78.92
   78.95   79.58   79.72   80.02   80.07
                                                                                
                                                                                
               0  62.152  62.152  62.152  62.152  62.152       0
                                                                                
                                                                                
                                        
       0    61.3  132.19  205.86  231.35  310.55  432.24  503.02  679.44  900.36
 1024.91 1113.83 1298.33  1371.4 1471.75 1624.46 1856.27  1936.62061.6372122.699
  2169.5  2169.52181.5842211.0752241.365  2258.5  2258.5 2271.432312.9742372.398
 2432.87 2516.21 2533.83 2548.85 2560.83 2641.31 2765.18 2817.65  2821.7 2830.16
 2846.82 2847.53 2848.22 2849.63 2863.69 2867.49 2877.16 2878.42 2886.16 2890.09
 2890.72 2911.34 2918.52 2926.37 2929.39
   81.25   79.68    77.6   74.75   73.15   70.41   68.86   64.29   62.02   62.59
   60.01   61.45   62.82   62.53   62.34    61.3   61.39   61.79   62.54   63.25
   63.79   63.79   63.93   63.98   63.97  63.976  63.976   63.98   63.93   64.48
   65.59   66.86      67   67.49   68.11   70.64   74.62   76.47   76.56   76.83
   77.64   77.67   77.69   77.72   77.96   78.19   78.51   78.51   78.79   78.92
   78.95   79.58   79.72   80.02   80.07
                                                                                
                                                                                
       0   61.99   61.99   61.99   61.99   61.99       0
                                                                                
                                                                                
                                        
Pier Skew, UpSta & Num, DnSta & Num=  ,2224, 4 ,2199, 4 , 3 , 3 , 0 ,,
       1       1     1.5     1.5
      49   61.15   61.15   62.15
       1       1     1.5     1.5
      49   60.99   60.99   61.99
Pier Skew, UpSta & Num, DnSta & Num=  ,2254, 4 ,2229, 4 , 3 , 3 , 0 ,,
       1       1     1.5     1.5
      49   61.15   61.15   62.15
       1       1     1.5     1.5
      49   60.99   60.99   61.99
BR Coef=-1 , 1 , 0 ,1.25, 0 ,,,0.8,0,2,0,
WSPro=,,,, 1 ,,,, 0 ,,,, 0 ,,,,-1 ,-1 ,-1 , 0 , 0 , 0 , 0 , 0
BC Design=,, 0 ,, 0 ,,,,,,
BC Use User HTab Curves=0
BC User HTab FreeFlow(D)= 0

Type RM Length L Ch R = 1 ,26051   ,518.71,424.76,413.32
BEGIN DESCRIPTION:
Surveyed Section
END DESCRIPTION:
XS GIS Cut Line= 6
2354399.11805664636967.3176503932354990.68486227635604.065190792
2355396.86758436635109.7101124082355453.96950285635023.734833926
2355570.44333656 634868.742143842355811.72305769 634437.17873092
#Sta/Elev= 30
       0   81.85  294.23   69.74  471.82    67.8  499.22      62   913.1   61.78
 1031.51   59.42 1049.21   56.51 1059.26    59.8 1116.48   60.25 1294.56   62.48
 1583.2160.79625 2091.81   56.212167.007   61.272189.452   57.442195.964   51.91
2197.144   49.58 2230.85   49.152231.739   51.982239.514   58.33 2264.94   60.23
2315.115   58.62 2436.99   63.91  2482.1   64.64 2564.62   72.91 2602.83   72.71
  2627.3   75.75 2653.72   73.14 2680.28   76.65  2793.1   81.16  2918.9   82.83
#Mann= 8 ,-1 , 0
       0    .045       0  294.23    .075       0 1116.48    .035       0
 1583.21    .085       02195.964     .05       02231.739     .09       0
 2436.99     .07       0  2793.1    .045       0
#XS Ineff= 4 ,-1
       0     705      66     705    1280    62.5    1280  2159.5    61.3
  2268.5    2950   63.93
Permanent Ineff=
       T       T       F       F
Bank Sta=2195.964,2231.739
XS Rating Curve= 0 ,0
Exp/Cntr=0.5,0.3

Type RM Length L Ch R = 1 ,25627   ,560.68,518.55,498.84
XS GIS Cut Line= 3
2354832.97383702636949.8308122852356034.28276467634871.375683482
2356051.07474227634777.872946998
#Sta/Elev= 30
       0   76.38   44.55   74.53  155.85   65.93  237.69   64.58  248.83    62.7
  290.32   63.09  397.26   61.57  679.25   62.32  707.47   61.34  747.34   61.75
  828.15   59.13  870.74   61.49  918.91   62.57 1179.68   63.11 1419.41    59.1
 1579.32   59.29 1645.42   56.55 1749.72   55.75 1910.13   57.38 1915.02   57.13
  1923.9   53.98  1932.7   48.66 1949.99   53.94 2005.87   59.24  2135.5   56.08
 2315.69   58.94 2408.51   66.93 2445.98   71.68 2461.14   75.05 2495.65   80.19
#Mann= 4 ,-1 , 0
       0    .085       0  1923.9     .05       0 1949.99     .09       0
 2445.98     .07       0
#XS Ineff= 2 , 0
       0     915      62               0
Permanent Ineff=
       T       F
Bank Sta=1923.9,1949.99
XS Rating Curve= 0 ,0
Exp/Cntr=0.3,0.1

Type RM Length L Ch R = 1 ,25108   ,962.37,990.23,989.53
XS GIS Cut Line= 2
2355409.26023069637329.1852911562356497.55440249 634997.12635158
#Sta/Elev= 30
       0   76.62   51.31   70.13  171.07   65.28  252.46   63.25   647.4   60.93
    1025   61.89 1140.77   57.63 1198.37   56.64 1258.54   58.14 1349.48   58.29
 1569.24   56.63 1728.36   54.33 1749.27   56.32 1790.82   57.55 1864.29   56.94
 1872.59   57.86 1894.01   57.97 1929.18   56.01 1938.34   52.71 1961.01   48.63
 1966.42   52.44 1970.08   52.69 1989.22   54.11 2055.61   54.08 2147.77   57.19
 2216.57   56.65 2303.46   60.02 2427.54   60.84 2536.24   71.22  2573.5   79.01
#Mann= 3 , 0 , 0
       0    .085       0 1938.34     .05       0 1970.08     .09       0
#XS Ineff= 2 , 0
       0    1350    64.5               0
Permanent Ineff=
       F       F
Bank Sta=1938.34,1970.08
XS Rating Curve= 0 ,0
Exp/Cntr=0.3,0.1

Type RM Length L Ch R = 1 ,24118   ,739.16,774.64,760.98
XS GIS Cut Line= 3
 2356314.8155155637552.9406483022357506.12006356635228.339032754
2357653.61780845 635033.00418143
#Sta/Elev= 30
       0   77.57   144.6   72.04  482.29   66.53  905.33   62.98  1044.2   59.96
  1157.3   60.92 1254.08   58.52 1342.39    58.7 1403.97   56.93 1463.49   52.17
 1540.62   59.62 1582.23   56.27 1599.55   52.93 1612.86    47.4 1620.18   51.12
 1634.82   52.91 1676.72   57.24 1725.27   55.39 1962.98   55.63 1995.41   53.35
 2016.96   55.26 2083.03    56.6 2204.86   55.12 2272.61   57.03 2521.14   56.23
 2605.65   59.79 2742.82   75.37 2775.74   80.81 2827.62   86.86 2856.85   88.17
#Mann= 3 , 0 , 0
       0    .085       0 1599.55     .05       0 1634.82     .09       0
#XS Ineff= 2 , 0
       0    1250      64               0
Permanent Ineff=
       F       F
Bank Sta=1599.55,1634.82
XS Rating Curve= 0 ,0
Exp/Cntr=0.3,0.1

Type RM Length L Ch R = 1 ,23343   ,880.73,828.01,706.65
XS GIS Cut Line= 3
 2357047.6811267 637528.506568032357725.37346813636492.035928234
2358307.39159665635256.244011521
#Sta/Elev= 30
       0    73.9   11.98   73.62  108.68   69.23  341.36   66.28  474.56   55.48
  591.36   55.81  633.44   54.12  912.77   54.84  983.38   57.25 1032.97   55.01
 1065.01   50.46 1073.28   46.71 1108.85   50.46 1125.29   52.35 1135.08   55.36
 1162.94   53.57 1243.68   54.95 1372.53   53.27 1382.82   54.51 1461.12   54.78
  1495.8   56.91 1577.56   54.36  2107.2   55.28 2193.55   56.82 2208.08   55.65
 2222.24   58.16 2272.91   57.78 2446.21   65.75  2535.4   67.55 2604.35   71.63
#Mann= 4 ,-1 , 0
       0    .045       0   11.98    .085       0 1065.01     .05       0
 1108.85    .085       0
#XS Ineff= 2 ,-1
    1400    1875      59    1875    2700    60.5
Permanent Ineff=
       T       T
Bank Sta=1065.01,1108.85
XS Rating Curve= 0 ,0
Exp/Cntr=0.3,0.1

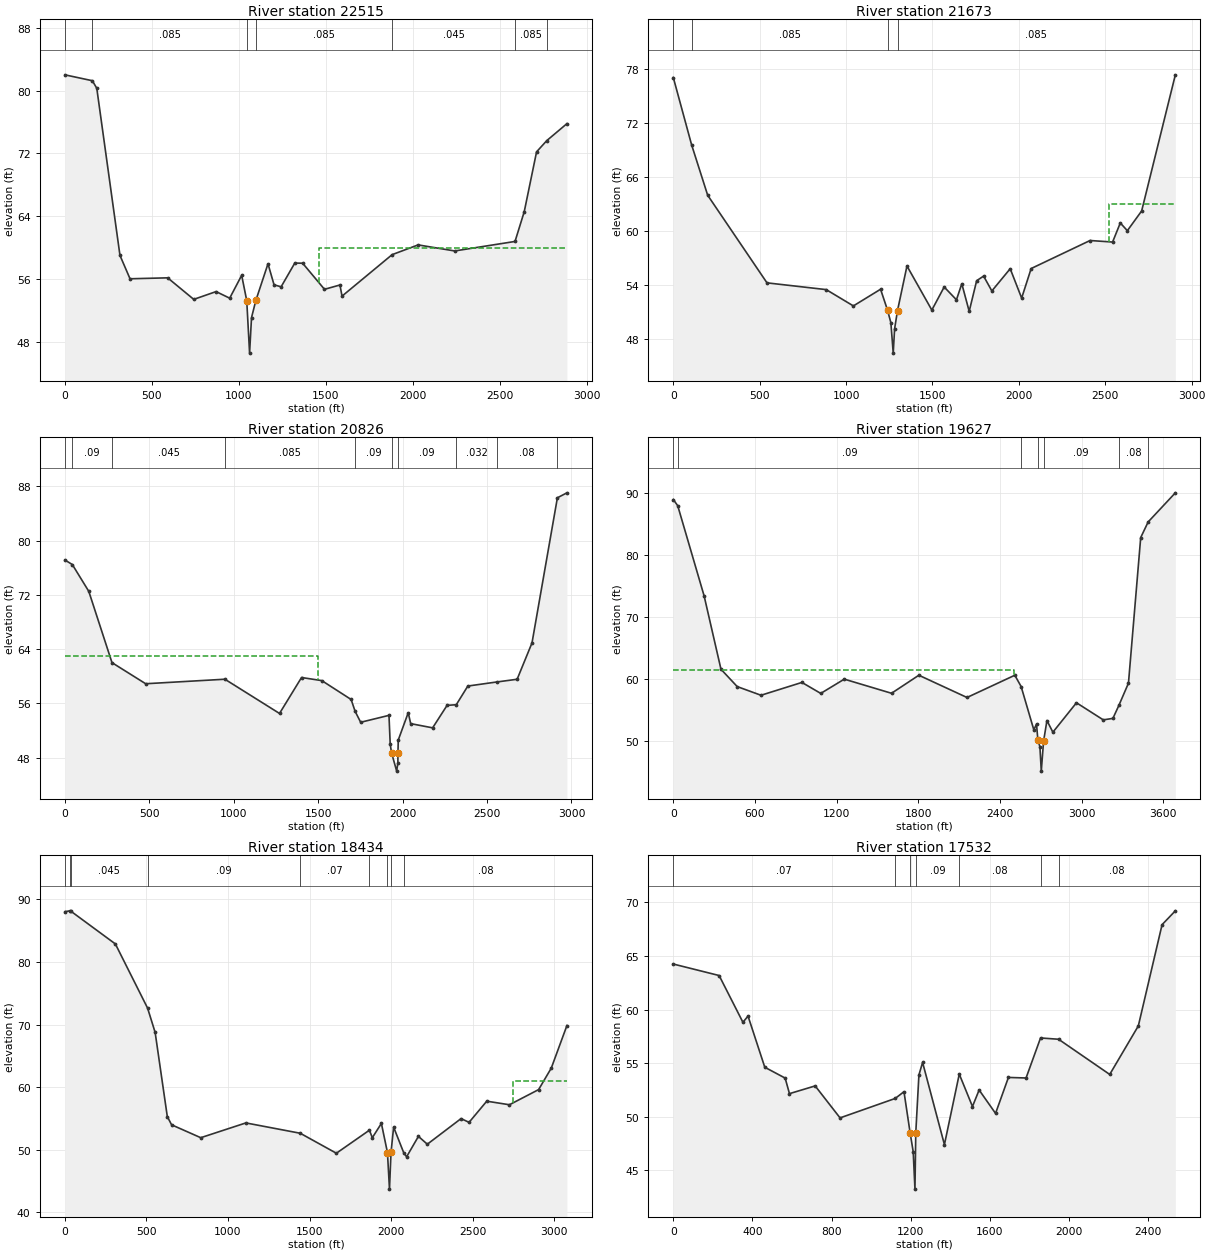
Type RM Length L Ch R = 1 ,22515   ,773.74,842.1,762.43
XS GIS Cut Line= 2
 2357859.3855716  638175.69294252358893.39615069635483.470267162
#Sta/Elev= 30
       0      82  157.75   81.25  183.17   80.29  316.42   59.02  374.15   56.05
  590.38   56.17  740.28   53.43  868.54   54.42  946.67   53.58 1015.51   56.49
 1044.58   53.28 1060.97   46.59 1072.07   51.11 1096.92   53.29  1166.7   57.96
 1201.52   55.28 1242.12   55.03 1320.65   58.05 1365.74   58.03 1491.25   54.71
 1580.05   55.26 1591.97   53.84 1879.77   59.12 2029.18   60.36  2239.2   59.59
 2585.76    60.8 2638.64   64.58 2709.55    72.2 2768.3273.63204 2883.96   75.79
#Mann= 7 ,-1 , 0
       0    .045       0  157.75    .085       0 1044.58     .05       0
 1096.92    .085       0 1879.77    .045       0 2585.76    .085       0
 2768.32    .045       0
#XS Ineff= 2 , 0
       0                    1460       0      60
Permanent Ineff=
       F       T
Bank Sta=1044.58,1096.92
XS Rating Curve= 0 ,0
Exp/Cntr=0.3,0.1

Type RM Length L Ch R = 1 ,21673   ,754.56,847.65,863.81
XS GIS Cut Line= 4
2358518.67215015638285.9274202142359080.75815095637213.578950554
2359076.77172542637058.1083545832359682.70840716635642.927288696
#Sta/Elev= 30
       0      77  106.06   69.52  199.03   63.93  542.19   54.21  884.94   53.46
 1042.23   51.65 1199.58    53.5 1240.06   51.17 1259.17   49.79 1272.84   46.41
 1280.76    49.1 1297.69   51.14 1352.38   56.08 1496.36   51.19 1567.71   53.75
 1638.79   52.33 1669.81   54.11 1712.51   51.05 1755.75   54.45 1795.97   54.96
 1843.66   53.31 1949.88   55.78  2016.1   52.52 2071.21    55.8 2412.17   58.91
 2542.47   58.74 2587.08   60.86 2627.87      60 2710.67   62.19  2905.7    77.3
#Mann= 4 ,-1 , 0
       0    .045       0  106.06    .085       0 1240.06     .05       0
 1297.69    .085       0
#XS Ineff= 2 , 0
       0                    2520       0      63
Permanent Ineff=
       F       F
Bank Sta=1240.06,1297.69
XS Rating Curve= 0 ,0
Exp/Cntr=0.3,0.1

Type RM Length L Ch R = 1 ,20826   ,1114.63,1198.39,1243.2
BEGIN DESCRIPTION:
Surveyed Section
END DESCRIPTION:
XS GIS Cut Line= 6
2358979.12994145638846.054370016    2359878.1603 637202.92490001
2359896.68870001637160.5364000052359912.47730002637133.100100011
2359966.50579999637071.7011000222360421.66893277636249.484185636
#Sta/Elev= 30
       0   77.14      44   76.47  141.48   72.52  278.87   62.01  478.37    58.9
  947.5159.56608 1270.99   54.52 1401.42   59.82 1521.47   59.36 1695.05   56.58
 1718.72   54.83 1751.56   53.221919.233   54.241926.481   49.991934.552   48.71
1964.808   46.021971.843   47.241972.464   48.761974.129    50.62033.219   54.63
 2047.81   53.02 2177.66    52.4 2263.17   55.71 2317.79   55.81 2386.18   58.56
 2557.41   59.16 2678.11   59.56 2766.21   64.92 2916.56   86.31 2973.04   87.04
#Mann= 10 ,-1 , 0
       0    .045       0      44     .09       0  278.87    .045       0
  947.51    .085       0 1718.72     .09       01934.552     .05       0
1972.464     .09       0 2317.79    .032       0 2557.41     .08       0
 2916.56    .045       0
#XS Ineff= 2 , 0
       0    1500      63               0
Permanent Ineff=
       F       F
Bank Sta=1934.552,1972.464
XS Rating Curve= 0 ,0
Exp/Cntr=0.3,0.1

Type RM Length L Ch R = 1 ,19627   ,1192.83,1193.37,1184.45
XS GIS Cut Line= 5
2359184.12232442640030.4548050022359333.00000003639840.125000045
2360000.00000004 638976.62500003      2361309.25637282.000000015
2361408.66929528637092.230649009
#Sta/Elev= 30
       0   89.02   32.46   88.02  226.38   73.47  350.18   61.64  469.47   58.84
  644.27   57.44  944.87   59.51 1083.22   57.74 1256.19   60.04 1603.19   57.76
 1803.95   60.67  2157.8   57.08    2509   60.67 2555.36   58.85 2648.72   51.86
 2668.47   52.79 2678.63   50.17 2693.31   49.15 2703.49    45.2 2720.34   50.03
 2745.05   53.36 2788.69   51.48 2962.04   56.23  3158.9   53.47 3229.77   53.71
  3273.5    55.8 3343.99   59.39 3433.96   82.88 3488.54    85.4 3688.45    90.1
#Mann= 7 ,-1 , 0
       0     .07       0   32.46     .09       0 2555.36     .09       0
 2678.63     .05       0 2720.34     .09       0  3273.5     .08       0
 3488.54    .045       0
#XS Ineff= 2 , 0
       0    2500    61.5               0
Permanent Ineff=
       F       F
Bank Sta=2678.63,2720.34
XS Rating Curve= 0 ,0
Exp/Cntr=0.3,0.1

Type RM Length L Ch R = 1 ,18434   ,919.07,901.53,833.1
XS GIS Cut Line= 2
2360459.63048518640341.7395347062362317.73568763637887.284866452
#Sta/Elev= 30
       0   88.01   30.17   88.15   37.25   88.08  309.62   82.86  507.02   72.62
  553.39   68.74  628.01    55.3  654.25   53.99  833.05   51.93 1109.74   54.29
 1443.18   52.64 1664.67   49.45 1867.39   53.13 1885.06   51.93 1940.79   54.21
 1977.93   49.56 1990.35   43.72 1999.71   49.57 2015.74   53.62 2077.96   49.51
  2095.3   48.88 2167.77   52.14 2222.41   50.89 2429.21   54.98 2478.39   54.38
 2586.81   57.76 2725.83   57.19  2904.8   59.61 2982.45   63.04 3078.46   69.84
#Mann= 9 ,-1 , 0
       0    .045       0   30.17     .09       0   37.25    .045       0
  507.02     .09       0 1443.18     .07       0 1867.39     .09       0
 1977.93     .05       0 1999.71     .09       0 2077.96     .08       0
#XS Ineff= 2 , 0
       0                    2750       0      61
Permanent Ineff=
       F       F
Bank Sta=1977.93,1999.71
XS Rating Curve= 0 ,0
Exp/Cntr=0.3,0.1

Type RM Length L Ch R = 1 ,17532   ,817.68,734.01,608.45
XS GIS Cut Line= 2
2361640.04334622640450.556487225 2362959.5501992638281.940994671
#Sta/Elev= 30
       0   64.24  231.68   63.17  352.04   58.81  377.83   59.39  462.56   54.62
   565.5   53.61  587.34   52.16  717.32   52.88  843.12    49.9 1121.76   51.71
  1166.4   52.34 1197.41   48.51    1213   46.75 1221.87   43.26 1226.05   48.52
 1241.91    53.9 1260.51   55.07 1370.86   47.41 1445.93   53.98 1512.71   50.96
 1546.31    52.5  1629.4   50.32 1694.46   53.67 1783.66   53.62 1856.91   57.35
 1948.05   57.23 2206.66   53.95 2351.25   58.47 2471.39   67.91  2538.5    69.2
#Mann= 7 ,-1 , 0
       0     .07       0 1121.76     .09       0 1197.41     .05       0
 1226.05     .09       0 1445.93     .08       0 1856.91    .045       0
 1948.05     .08       0
#XS Ineff= 2 , 0
       0                    1916       0      57
Permanent Ineff=
       F       F
Bank Sta=1197.41,1226.05
XS Rating Curve= 0 ,0
Exp/Cntr=0.3,0.1