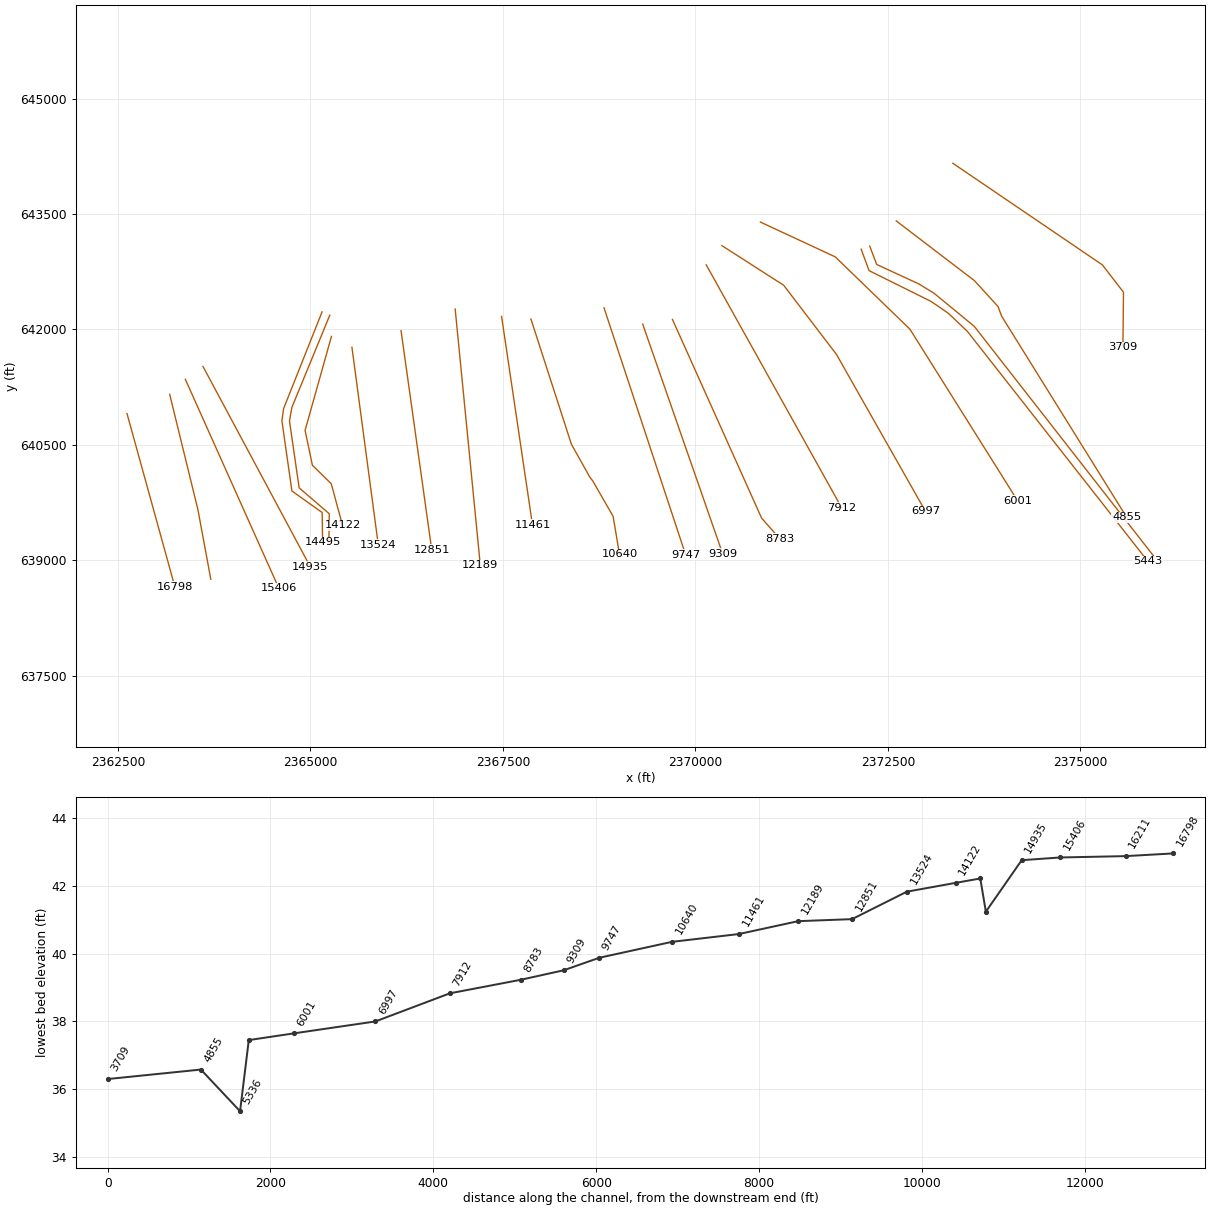
HEC-RAS study DTL_Nahunta_Swamp.prj: DTL_Nahunta_Swamp

--- DTL_Nahunta_Swamp.g01 (geometry) --- (continued)

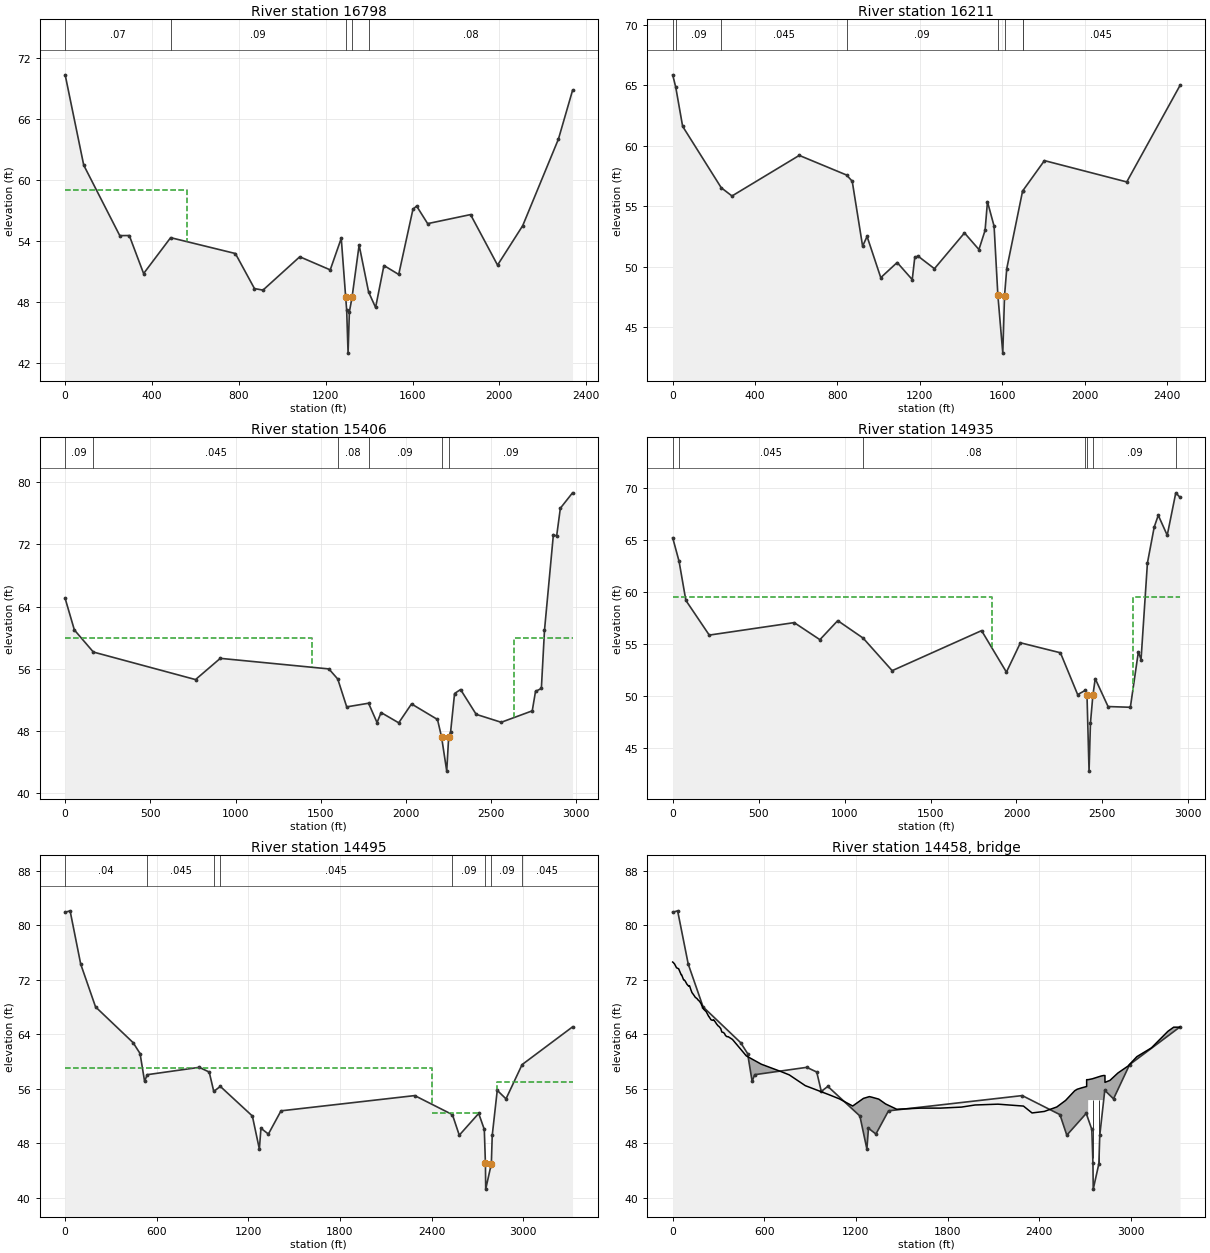
Type RM Length L Ch R = 1 ,16798   ,603.04,586.8,535.26
XS GIS Cut Line= 2
2362616.71760297640905.0089985132363238.59998685638652.678569704
#Sta/Elev= 30
       0   70.34   85.56   61.45  251.52   54.52  295.33   54.53   361.3   50.79
  485.78   54.32  783.93   52.76  871.86   49.31  911.14   49.16 1080.48   52.44
 1220.76   51.15 1271.56   54.26  1291.9   48.47 1296.58   47.16 1302.91   42.96
 1308.99   47.03 1321.38   48.47 1353.83   53.59 1397.52   48.97 1429.69   47.45
 1468.05   51.58 1536.14    50.7 1601.78   57.12 1618.56   57.43 1669.42    55.7
 1867.01   56.59 1991.35   51.62 2107.21    55.5 2271.76   64.02 2336.61    68.8
#Mann= 5 ,-1 , 0
       0     .07       0  485.78     .09       0  1291.9     .05       0
 1321.38     .09       0 1397.52     .08       0
#XS Ineff= 2 , 0
       0     560      59 1618.56       0   57.43
Permanent Ineff=
       F       F
Bank Sta=1291.9,1321.38
XS Rating Curve= 0 ,0
Exp/Cntr=0.3,0.1

Type RM Length L Ch R = 1 ,16211   ,581.95,805.1,758.61
XS GIS Cut Line= 3
 2363170.8307527641156.1538074172363537.58190218639657.257805213
2363705.01177476638752.339208126
#Sta/Elev= 30
       0   65.85   15.03   64.81    48.3    61.6  235.75   56.53     288   55.85
   614.6    59.2   844.2   57.58  871.68   57.07  922.07   51.71  943.81   52.51
 1010.28   49.11 1089.92   50.36 1163.14   48.95 1175.54    50.8 1191.73   50.88
 1270.89   49.85  1416.8    52.8 1486.95   51.43 1516.85   53.02 1528.32   55.38
 1560.48   53.36 1578.85   47.66 1602.76   42.88 1611.26   47.63 1621.98   49.85
    1699   56.27 1699.4956.27334 1804.96   58.77 2204.62   57.01 2463.39   64.98
#Mann= 8 ,-1 , 0
       0    .045       0   15.03     .09       0  235.75    .045       0
   844.2     .09       0 1578.85     .05       0 1611.26     .09       0
    1699     .08       0 1699.49    .045       0
#XS Ineff= 2 , 0
       0   614.6    59.2 1804.96       0   58.77
Permanent Ineff=
       F       F
Bank Sta=1578.85,1611.26
XS Rating Curve= 0 ,0
Exp/Cntr=0.3,0.1

Type RM Length L Ch R = 1 ,15406   ,470.74,471.55,489.03
XS GIS Cut Line= 2
2363374.13845512641351.4886587562364589.99824414638632.746442005
#Sta/Elev= 30
       0   65.04   54.09   60.99  165.59   58.15  765.25   54.61  910.63   57.34
 1548.05   55.98  1600.2   54.68 1652.74    51.1 1780.98   51.57 1830.78   49.08
 1854.54   50.37 1958.02   49.05 2033.06   51.48 2185.62   49.48 2209.57   47.22
 2239.86   42.84 2251.25   47.25 2262.47   47.86 2285.88   52.82 2321.05   53.33
 2412.77   50.14 2559.76   49.12 2741.81   50.59 2761.01   53.09 2795.35   53.47
 2813.68   60.94 2865.91   73.25 2884.99   73.06 2906.83   76.64 2978.23   78.62
#Mann= 6 ,-1 , 0
       0     .09       0  165.59    .045       0  1600.2     .08       0
 1780.98     .09       0 2209.57     .05       0 2251.25     .09       0
#XS Ineff= 2 , 0
       0    1450      60    2635       0      60
Permanent Ineff=
       F       F
Bank Sta=2209.57,2251.25
XS Rating Curve= 0 ,0
Exp/Cntr=0.3,0.1

Type RM Length L Ch R = 1 ,14935   ,261.84,440.14,504.23
XS GIS Cut Line= 2
2363603.65715441641517.892236725  2364996.613649638915.782655194
#Sta/Elev= 30
       0    65.2   37.19   62.93   76.58   59.18  212.76   55.84  706.92   57.04
  856.39    55.4  960.07   57.23 1107.99   55.55 1276.89   52.42 1796.91   56.27
 1941.42   52.28 2022.96    55.1 2255.59   54.14  2355.9   50.12 2399.56   50.52
 2410.19   50.06 2422.14   42.76 2430.26   47.38 2444.41   50.05 2458.08   51.65
 2532.71   48.97 2662.45    48.9 2709.02   54.23 2724.62   53.49 2761.73   62.77
  2801.2   66.23 2824.77   67.36 2876.96   65.44  2926.7   69.52 2951.49   69.08
#Mann= 7 ,-1 , 0
       0    .035       0   37.19    .045       0 1107.99     .08       0
 2399.56    .045       0 2410.19     .05       0 2444.41     .09       0
  2926.7    .045       0
#XS Ineff= 2 , 0
       0 1859.56    59.5    2675       0    59.5
Permanent Ineff=
       F       F
Bank Sta=2410.19,2444.41
XS Rating Curve= 0 ,0
Exp/Cntr=0.5,0.3

Type RM Length L Ch R = 1 ,14495   ,152.93,68.72,76.07
BEGIN DESCRIPTION:
Surveyed Section
END DESCRIPTION:
XS GIS Cut Line= 6
2365150.24779607642227.4987820832364650.77034748640970.032999367
2364628.57852148640812.3778854612364758.61753343639899.370385662
2365151.86711466639619.4475887422365157.00769043639231.906807557
#Sta/Elev= 30
       0   81.91   32.37   82.12  101.86   74.29  199.01   68.01  444.91   62.76
  490.49   61.16   520.2   57.07  537.28   58.05  878.05   59.13   943.4   58.44
  973.21   55.59 1016.07   56.33 1225.98   51.98 1271.89   47.12 1282.19   50.18
 1330.97   49.33 1413.52   52.74 2289.23   54.98  2536.2   52.18 2581.05   49.16
2708.173   52.362744.906   50.012752.262   45.032754.164   41.242791.049   44.97
2796.849   49.122829.703   55.75 2887.03    54.5  2992.4   59.53 3322.68   65.07
#Mann= 8 ,-1 , 0
       0     .04       0  537.28    .045       0  973.21    .035       0
 1016.07    .045       0  2536.2     .09       02752.262     .05       0
2791.049     .09       0  2992.4    .045       0
#XS Ineff= 3 ,-1
       0    2400      59    2400    2711   52.48    2831    3400   56.93
Permanent Ineff=
       F       F       F
Bank Sta=2752.262,2791.049
XS Rating Curve= 0 ,0
Exp/Cntr=0.5,0.3

Type RM Length L Ch R = 3 ,14458   ,,,
BEGIN DESCRIPTION:
Nahunta Road (SR 1218)
END DESCRIPTION:
Bridge Culvert--1,0,-1,-1, 0
Deck Dist Width WeirC Skew NumUp NumDn MinLoCord MaxHiCord MaxSubmerge Is_Ogee
9.85,30,2.6,0, 96, 95, , , 0.98, 0, 0.75,0.75,,
       0    6.38    7.12   11.55   23.23   24.84    38.7   39.27   39.34   55.97
   58.02   71.81   75.94   81.61   92.91  105.03  110.08  119.33  126.45  134.42
  143.37  147.45  159.89  168.79  175.03  186.75  190.07  201.95  204.06  204.56
  219.71  219.89  235.98  237.26   249.8  252.54  265.26   268.1  281.42  286.04
  297.42  303.02  314.65  321.92  331.11  339.02  346.05  355.61  363.58  391.34
  482.22  580.53  713.61  763.55   868.4 1020.27 1091.77  1178.81249.2731288.083
1305.0831349.7161394.496 1467.61 1622.93 1753.55 1891.03 1980.49 2130.44 2297.07
 2353.33 2433.612515.6592573.1392632.2992648.8242678.922    2711    27112718.826
    2721    27212748.8272805.208    2821    2821    2831    28312863.4892915.812
 2982.06 3039.87 3135.21 3243.44  3281.1 3319.82
    74.6   74.47   74.43   74.34   73.84   73.76   73.61   73.59   73.59   72.71
   72.75   71.96   71.96   71.82   71.35   71.04   71.13   70.52    70.1   69.87
   69.58   69.43   69.21   68.96   68.86   68.45   68.23   67.76   67.64   67.63
    67.3   67.29    66.6    66.6   66.16   66.09   66.03   66.12   65.72   65.54
   65.22   65.14   64.83   64.31   64.26   64.11    63.8   63.63   63.63   63.23
   60.81   59.59   58.47   58.02   56.44   55.14    54.5   53.45   54.57   54.83
   54.74   54.46   53.75   52.97   53.14   53.14   53.29    53.6   53.72   53.44
   52.43   52.65   53.31   54.27   55.68   55.91   56.12  56.319  57.319   57.32
  57.319  57.319   57.45   57.85  57.928  57.928  57.928  56.928   57.21    58.3
   59.32    60.7   61.99   64.43   65.03   65.03
                                                                                
                                                                                
                                                                                
                                                                                
                                                                                
                                                                                
                                                                                
                                                                                
       0  54.319  54.319  54.319  54.319       0
                                                
       0    6.38    7.12   11.55   23.23   24.84    38.7   39.27   39.34   55.97
   58.02   71.81   75.94   81.61   92.91  105.03  110.08  119.33  126.45  134.42
  143.37  147.45  159.89  168.79  175.03  186.75  190.07  201.95  204.06  204.56
  219.71  219.89  235.98  237.26   249.8  252.54  265.26   268.1  281.42  286.04
  297.42  303.02  314.65  321.92  331.11  339.02  346.05  355.61  363.58  391.34
  482.22  580.53  713.61  763.55   868.4 1020.27 1091.77  1178.81249.2731288.083
1305.0831349.7161394.496 1467.61 1622.93 1753.55 1891.03 1980.49 2130.44 2297.07
 2353.33 2433.612515.6592573.139    2595    2595    2605    26052632.2992648.824
2678.922    2705    2705    2715    27152718.8262748.8272805.2082863.4892915.812
 2982.06 3039.87 3135.21 3243.44  3281.1
    74.6   74.47   74.43   74.34   73.84   73.76   73.61   73.59   73.59   72.71
   72.75   71.96   71.96   71.82   71.35   71.04   71.13   70.52    70.1   69.87
   69.58   69.43   69.21   68.96   68.86   68.45   68.23   67.76   67.64   67.63
    67.3   67.29    66.6    66.6   66.16   66.09   66.03   66.12   65.72   65.54
   65.22   65.14   64.83   64.31   64.26   64.11    63.8   63.63   63.63   63.23
   60.81   59.59   58.47   58.02   56.44   55.14    54.5   53.45   54.57   54.83
   54.74   54.46   53.75   52.97   53.14   53.14   53.29    53.6   53.72   53.44
   52.43   52.65   53.31   54.27  55.125  56.125  56.125  56.125   56.68   56.91
   57.12  57.239  57.239  57.239    56.3   56.32   56.45   56.85   57.21    58.3
   59.32    60.7   61.99   64.43   65.03
                                                                                
                                                                                
                                                                                
                                                                                
                                                                                
                                                                                
                                                                                
                                                       0  53.125  53.125  53.125
  53.125  53.125       0
                                        
Pier Skew, UpSta & Num, DnSta & Num=  ,2751, 4 ,2635, 4 , 3 , 3 , 0 ,,
    1.15    1.15       2       2
      41   52.97   52.97   54.32
    1.15    1.15       2       2
      41   51.78   51.78   53.13
Pier Skew, UpSta & Num, DnSta & Num=  ,2791, 4 ,2675, 4 , 3 , 3 , 0 ,,
    1.15    1.15       2       2
      41   52.97   52.97   54.32
    1.15    1.15       2       2
      41   51.78   51.78   53.13
Abutment Skew #Up #Dn= , 3 , 3
    27212745.945    2751
   52.29   48.98   45.25
    2605 2622.82    2635
   52.35   49.37   45.88
Abutment Skew #Up #Dn= , 3 , 3
    2791    2799    2821
   45.33   48.87   53.12
    2675 2691.03    2705
   47.22   49.96   53.03
BR Coef= 1 , 1 , 0 ,1.25, 0 ,,,0.8,0,2,0,
WSPro=,,,, 1 ,,,, 0 ,,,, 0 ,,,,-1 ,-1 ,-1 , 0 , 0 , 0 , 0 , 0
BC Design=,, 0 ,, 0 ,,,,,,
BC Use User HTab Curves=0
BC User HTab FreeFlow(D)= 0

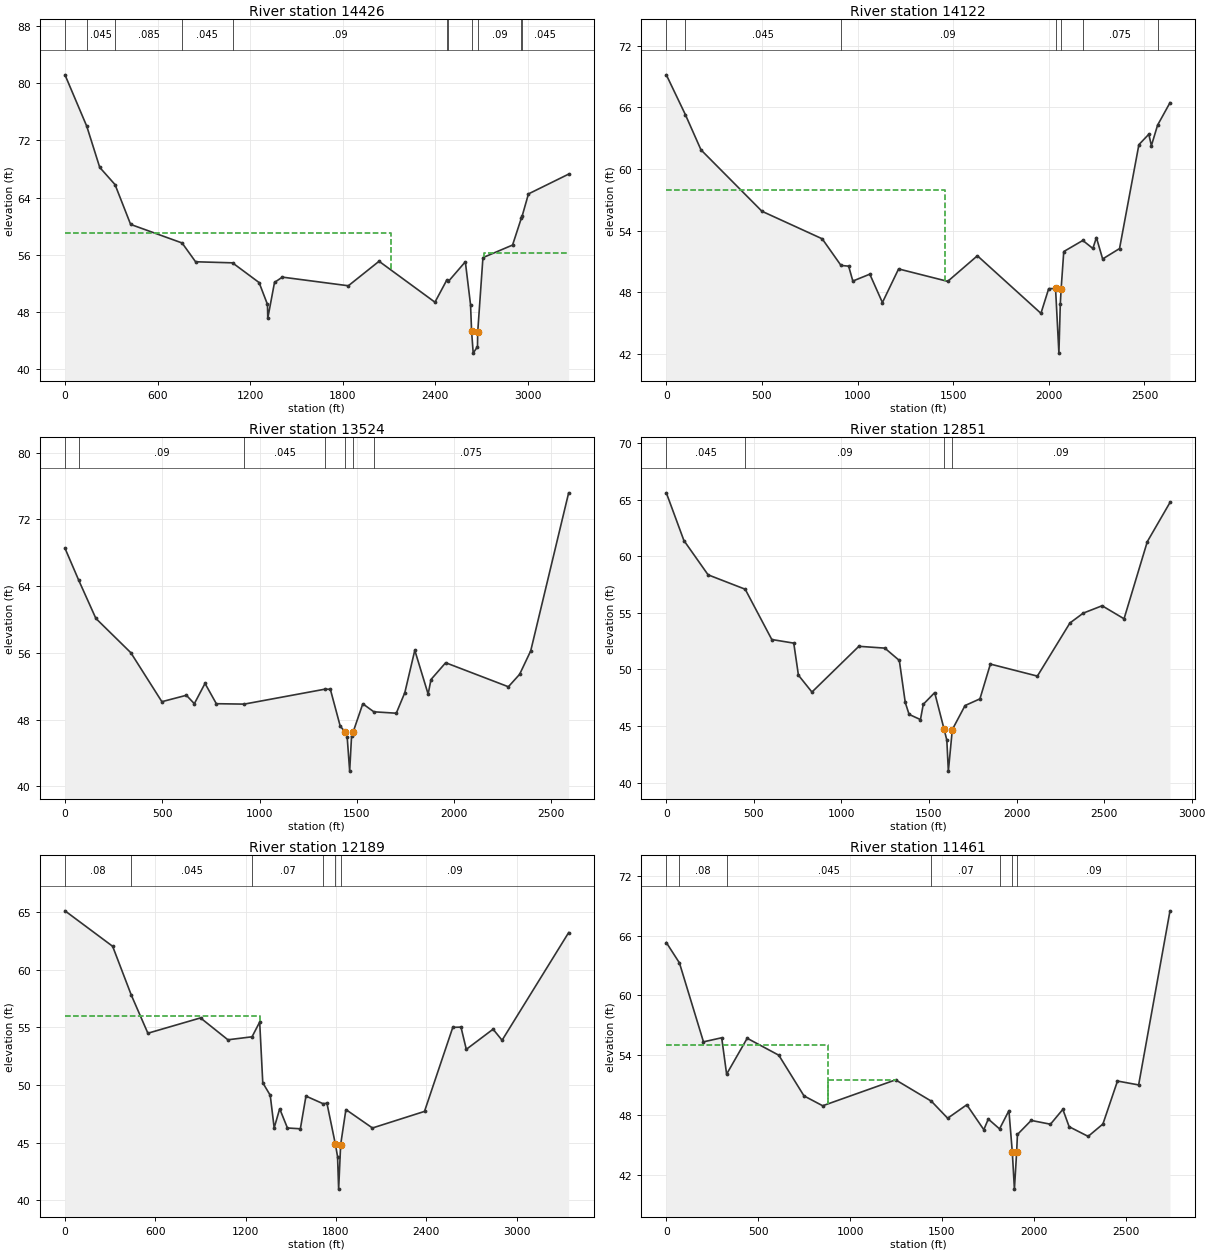
Type RM Length L Ch R = 1 ,14426   ,351.65,303.89,212.33
BEGIN DESCRIPTION:
Surveyed Section
END DESCRIPTION:
XS GIS Cut Line= 6
2365250.69764917642184.5486476422364758.52975313640986.651346326
2364726.89845946640811.1272265462364852.63688223639940.148985311
2365244.17649069639603.2413795892365238.72400551639223.348659948
#Sta/Elev= 30
       0   81.18  141.07   73.99  225.37   68.22  324.58   65.81  425.64   60.24
  759.21   57.64  846.65   55.01 1086.08   54.86  1258.4    52.1 1312.85   49.03
  1314.6   47.09 1358.36   52.12 1409.11   52.86 1837.05   51.65 2036.04   55.08
 2398.44   49.35  2474.2   52.41 2485.96   52.272595.426   55.01 2629.13   48.99
2635.855   45.35 2646.25   42.222674.144   43.122675.568   45.152709.461   55.59
 2901.52   57.35 2958.14    61.1 2963.36   61.38 3004.53   64.51  3265.1   67.28
#Mann= 11 ,-1 , 0
       0     .05       0  141.07    .045       0  324.58    .085       0
  759.21    .045       0 1086.08     .09       0  2474.2    .035       0
 2485.96     .09       02635.855     .05       02675.568     .09       0
 2958.14    .075       0 2963.36    .045       0
#XS Ineff= 3 ,-1
       0    2115      59    2115    2595   52.43    2715    3300    56.3
Permanent Ineff=
       F       F       F
Bank Sta=2635.855,2675.568
XS Rating Curve= 0 ,0
Exp/Cntr=0.5,0.3

Type RM Length L Ch R = 1 ,14122   ,801.88,598.17,494.41
XS GIS Cut Line= 5
2365272.21759024641908.0674726672364929.68958123640687.120859876
2365024.88258766640234.0895430152365269.73767477639993.121044621
2365415.85836823639453.618235007
#Sta/Elev= 30
       0   69.16   99.81   65.28  181.31   61.86  499.88   55.89  815.08   53.21
  913.29   50.62  953.29   50.55   975.2    49.1 1063.89   49.77 1129.85   47.01
 1214.44   50.28 1471.31   49.07 1626.43   51.56  1958.7   45.96 1999.23   48.36
 2035.09   48.38 2052.65   42.09 2059.89   46.86 2064.45   48.37 2078.04   51.97
 2177.63   53.05 2230.17   52.27 2248.73   53.33 2281.38   51.25 2369.67   52.26
 2470.92   62.37 2522.67   63.38 2536.21   62.27  2568.7   64.27 2633.49   66.45
#Mann= 7 ,-1 , 0
       0    .045       0   99.81    .045       0  913.29     .09       0
 2035.09     .05       0 2064.45     .09       0 2177.63    .075       0
  2568.7    .045       0
#XS Ineff= 2 , 0
       0    1455      58               0
Permanent Ineff=
       T       F
Bank Sta=2035.09,2064.45
XS Rating Curve= 0 ,0
Exp/Cntr=0.3,0.1

Type RM Length L Ch R = 1 ,13524   ,671.5,672.46,673.44
XS GIS Cut Line= 2
2365538.40504594 641767.440137582365880.20355672639201.034623072
#Sta/Elev= 30
       0   68.54   70.94   64.69  158.82   60.13  338.51   56.02  498.15   50.15
  624.12   50.92  664.97   49.91  719.84   52.34  778.04   49.91  921.19   49.86
 1338.55   51.66  1364.2   51.63 1414.74   47.23 1440.04   46.52 1450.53   45.95
 1463.45   41.83 1473.07   45.99 1481.32   46.52 1530.91    49.9 1587.62   48.94
 1703.06   48.77 1747.01   51.24 1798.23   56.31 1866.81   51.06 1881.54   52.81
 1956.91   54.82 2279.29   51.94 2337.01   53.43 2394.05   56.24 2589.07   75.18
#Mann= 7 ,-1 , 0
       0    .045       0   70.94     .09       0  921.19    .045       0
 1338.55     .09       0 1440.04     .05       0 1481.32     .09       0
 1587.62    .075       0
#XS Ineff= 2 , 0
       0                    1800       0    54.5
Permanent Ineff=
       F       T
Bank Sta=1440.04,1481.32
XS Rating Curve= 0 ,0
Exp/Cntr=0.3,0.1

Type RM Length L Ch R = 1 ,12851   ,676.84,662.5,656.32
XS GIS Cut Line= 2
2366176.25045864641983.4035450382366574.78985648639134.883546913
#Sta/Elev= 30
       0   65.59  100.38   61.38  238.54   58.35  450.42   57.08  602.27   52.64
  727.76   52.32  754.39   49.49  831.59      48 1099.51   52.04 1247.73   51.88
 1330.59   50.79  1364.5   47.08  1386.3   46.03 1451.18   45.57 1467.35   46.92
 1532.49   47.95 1586.07   44.73 1601.79   43.76 1610.55   41.02 1633.21   44.69
 1705.91   46.81  1790.9    47.4 1850.55   50.47 2118.91   49.41 2304.86    54.1
 2381.02   54.97 2488.67   55.62 2613.89   54.47  2746.7   61.28 2876.27   64.74
#Mann= 4 ,-1 , 0
       0    .045       0  450.42     .09       0 1586.07     .05       0
 1633.21     .09       0
#XS Ineff= 2 , 0
       0    1050    50.5               0
Permanent Ineff=
       T       F
Bank Sta=1586.07,1633.21
XS Rating Curve= 0 ,0
Exp/Cntr=0.3,0.1

Type RM Length L Ch R = 1 ,12189   ,664.32,727.41,715.43
XS GIS Cut Line= 2
2366879.38713406 642264.658215212367205.84344763638934.803816646
#Sta/Elev= 30
       0   65.13   316.6   62.05  440.31   57.82  550.78    54.5  900.36   55.83
 1082.35   53.93 1242.64   54.19 1293.42   55.47 1313.91    50.2 1363.49   49.11
 1389.68   46.28 1426.33   47.94 1477.77   46.27 1563.62    46.2 1600.86   49.04
  1714.4   48.38 1740.22   48.42 1796.68   44.84 1810.76   43.77 1817.91   40.96
 1831.36   44.83 1866.16   47.87  2042.5   46.27 2388.27   47.71 2576.26   55.01
 2630.65   55.03 2665.95    53.1 2843.81   54.85  2903.6   53.89 3345.82   63.24
#Mann= 6 ,-1 , 0
       0     .08       0  440.31    .045       0 1242.64     .07       0
  1714.4     .08       0 1796.68     .05       0 1831.36     .09       0
#XS Ineff= 2 , 0
       0    1293      56               0
Permanent Ineff=
       T       F
Bank Sta=1796.68,1831.36
XS Rating Curve= 0 ,0
Exp/Cntr=0.3,0.1

Type RM Length L Ch R = 1 ,11461   ,618.6,821.19,883.51
XS GIS Cut Line= 2
2367482.07571298642169.2325235312367883.86809893 639457.13391836
#Sta/Elev= 30
       0   65.31   71.28   63.27  202.16   55.35  301.48   55.76  328.18   52.11
  440.16   55.71  612.32   54.01  749.45   49.93  851.18   48.94 1248.05   51.54
 1442.68    49.4 1531.51   47.69 1635.59   49.04 1728.23   46.54 1752.59   47.61
 1813.91   46.62 1864.87   48.45 1883.14   44.35 1894.83   40.58 1907.12   44.35
 1911.19   46.06 1986.16   47.47 2091.07   47.09 2158.43   48.58 2192.67   46.84
  2296.2   45.87 2376.55   47.11 2455.89   51.42    2571   51.03  2741.7   68.49
#Mann= 7 ,-1 , 0
       0    .045       0   71.28     .08       0  328.18    .045       0
 1442.68     .07       0 1813.91     .08       0 1883.14     .05       0
 1907.12     .09       0
#XS Ineff= 2 ,-1
       0     880      55     880    1248    51.5
Permanent Ineff=
       T       T
Bank Sta=1883.14,1907.12
XS Rating Curve= 0 ,0
Exp/Cntr=0.3,0.1

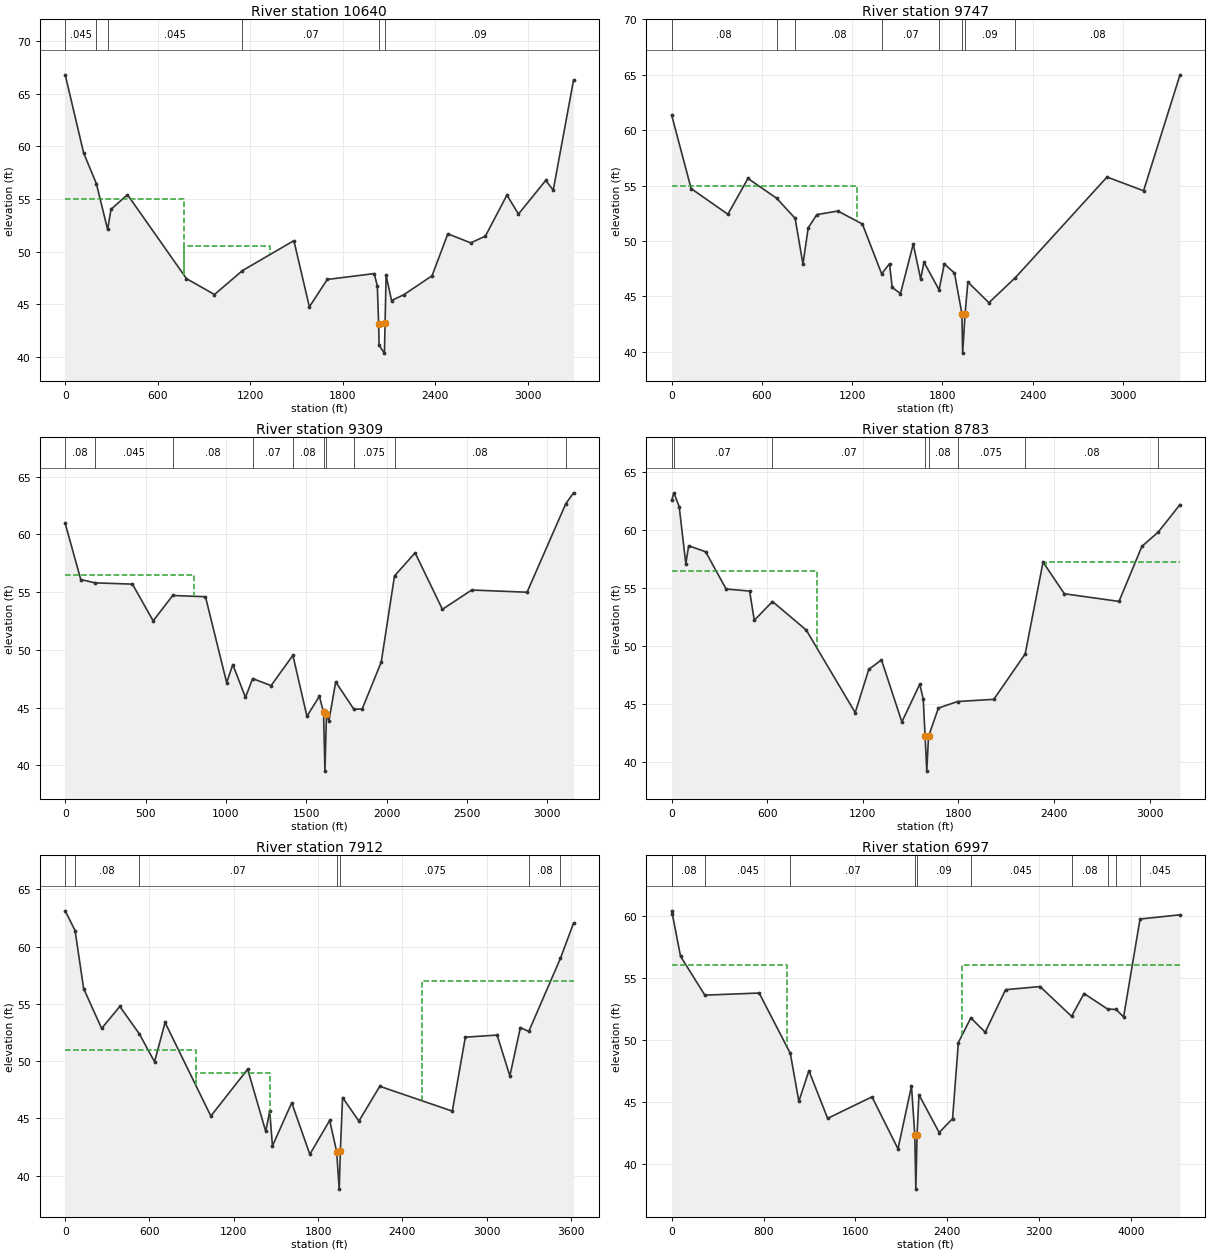
Type RM Length L Ch R = 1 ,10640   ,1004.45,892.85,842.33
BEGIN DESCRIPTION:
Surveyed Section
END DESCRIPTION:
XS GIS Cut Line= 6
2367863.77847962642134.0756897782368388.81320001640507.798600003
2368625.73420002640084.0143000042368669.54830001640025.748400018
     2368931.266639569.294400021 2369013.9091844639075.431151718
#Sta/Elev= 30
       0    66.8  119.62   59.37  202.34   56.45  274.84    52.1  296.94   54.02
  403.66   55.41  786.28   47.43  967.49   45.92 1148.81   48.19 1482.48   51.04
 1583.03   44.75 1698.68   47.352003.232   47.912023.405   46.742032.025   43.16
 2035.19   41.082069.528   40.352073.684   43.172080.374   47.742115.642   45.35
2195.176    45.92378.105    47.72480.771   51.692628.719   50.832724.072   51.47
 2863.49   55.37 2938.56   53.57 3115.01   56.76 3164.01   55.85  3295.5   66.29
#Mann= 6 ,-1 , 0
       0    .045       0  202.34     .08       0  274.84    .045       0
 1148.81     .07       02032.025     .05       02073.684     .09       0
#XS Ineff= 3 ,-1
       0     770      55     770    1330    50.5    1330    1700      47
Permanent Ineff=
       T       T       T
Bank Sta=2032.025,2073.684
XS Rating Curve= 0 ,0
Exp/Cntr=0.3,0.1

Type RM Length L Ch R = 1 ,9747    ,439.7,438,439.89
XS GIS Cut Line= 2
2368813.01299143642279.7254296992369872.74040939639070.408746883
#Sta/Elev= 30
       0   61.35  129.33   54.73   373.6   52.41  507.03   55.64  698.59   53.85
  820.94   52.04  872.83   47.91  907.76   51.18  965.16   52.38 1104.77    52.7
 1267.85   51.53 1396.18   47.03  1448.4   47.95 1465.99   45.81 1521.31   45.25
 1606.19   49.72 1655.48   46.56 1677.33   48.09 1777.75   45.59 1812.76   47.93
 1880.29   47.11 1929.79   43.43 1934.59   39.88 1950.71   43.41 1969.39    46.3
  2109.1   44.43 2285.73    46.7 2894.58   55.77 3137.54   54.53 3379.75   64.99
#Mann= 8 ,-1 , 0
       0     .08       0  698.59    .045       0  820.94     .08       0
 1396.18     .07       0 1777.75     .08       0 1929.79     .05       0
 1950.71     .09       0 2285.73     .08       0
#XS Ineff= 2 , 0
       0    1234      55               0
Permanent Ineff=
       T       F
Bank Sta=1929.79,1950.71
XS Rating Curve= 0 ,0
Exp/Cntr=0.3,0.1

Type RM Length L Ch R = 1 ,9309    ,489.4,526.81,545.39
XS GIS Cut Line= 2
2369315.25347389642068.7844270472370354.89127252639080.453556553
#Sta/Elev= 30
       0   60.94   96.82   56.09  185.73    55.8  418.48   55.69  547.49   52.51
  669.19   54.71  873.04    54.6 1004.89   47.17 1043.22   48.73 1121.99   45.89
 1166.57   47.52 1281.31   46.91 1417.16   49.53 1504.54   44.26 1582.17   45.99
 1607.93   44.59 1616.73   39.51 1626.11   44.42 1641.29   43.87 1683.62   47.23
 1796.53   44.87 1848.16   44.88  1967.2   48.95 2049.65    56.4 2177.95    58.4
 2347.79   53.51 2530.07   55.18 2874.72   54.99 3115.92   62.65 3164.01   63.59
#Mann= 10 ,-1 , 0
       0     .08       0  185.73    .045       0  669.19     .08       0
 1166.57     .07       0 1417.16     .08       0 1607.93     .05       0
 1626.11     .08       0 1796.53    .075       0 2049.65     .08       0
 3115.92    .045       0
#XS Ineff= 2 , 0
       0     800    56.5               0
Permanent Ineff=
       F       F
Bank Sta=1607.93,1626.11
XS Rating Curve= 0 ,0
Exp/Cntr=0.3,0.1

Type RM Length L Ch R = 1 ,8783    ,847.79,870.97,909.48
XS GIS Cut Line= 3
2369701.97864535642129.053284943 2370860.0849801639546.609274119
2371098.20718654639276.327344701
#Sta/Elev= 30
       0   62.57   13.72   63.22   47.17   62.04   88.77    57.1  106.52   58.66
  213.22   58.14  341.66   54.93   489.4   54.75  518.42   52.23  632.67   53.85
  844.73   51.39 1151.94   44.27 1237.18      48 1316.78   48.82 1444.83   43.47
 1557.26   46.73  1579.1   45.43 1590.56   42.24 1601.23   39.23 1611.96   42.22
 1674.24   44.67 1794.63   45.23    2022   45.42 2218.64   49.33 2330.93   57.25
 2464.44   54.52 2807.56   53.86  2951.6   58.61 3053.58   59.83 3190.45   62.21
#Mann= 8 ,-1 , 0
       0     .08       0   13.72     .07       0  632.67     .07       0
 1590.56     .05       0 1611.96     .08       0 1794.63    .075       0
 2218.64     .08       0 3053.58    .045       0
#XS Ineff= 2 , 0
       0     910    56.5    2351       0   57.27
Permanent Ineff=
       T       F
Bank Sta=1590.56,1611.96
XS Rating Curve= 0 ,0
Exp/Cntr=0.3,0.1

Type RM Length L Ch R = 1 ,7912    ,856.52,914.89,923.74
XS GIS Cut Line= 2
2370140.33286183642839.0130568442371901.79195844639678.119730636
#Sta/Elev= 30
       0   63.13    70.2   61.41  131.31   56.34  259.16   52.86  388.84   54.78
  527.59   52.39  635.91   49.95  710.87   53.38  1036.7   45.21 1298.67    49.3
 1427.49   43.87 1455.75   45.65 1475.26    42.6 1612.46   46.37 1741.36   41.87
 1882.66   44.83 1932.31    42.1 1950.48   38.83 1958.47   42.12 1974.32   46.83
 2090.61   44.77  2239.2   47.81 2755.55   45.64 2848.31    52.1 3074.49   52.28
 3165.36   48.71 3240.14   52.94 3299.77    52.6 3524.84   58.97 3618.49   62.05
#Mann= 7 ,-1 , 0
       0    .045       0    70.2     .08       0  527.59     .07       0
 1932.31     .05       0 1958.47    .075       0 3299.77     .08       0
 3524.84    .045       0
#XS Ineff= 3 ,-1
       0     930      51     930    1460      49    2540    3650      57
Permanent Ineff=
       T       T       F
Bank Sta=1932.31,1958.47
XS Rating Curve= 0 ,0
Exp/Cntr=0.3,0.1

Type RM Length L Ch R = 1 ,6997    ,958.41,995.78,1021.27
XS GIS Cut Line= 4
2370344.84646288 643088.33260639 2371146.7217661642573.551922321
2371832.40696384641674.6125680952372986.63140051639637.940492049
#Sta/Elev= 30
       0   60.38    5.31   60.15   76.98   56.73  288.48    53.6  761.32   53.77
 1032.68   48.92 1106.86   45.06 1194.59   47.52 1357.52   43.69 1743.47   45.42
 1969.91   41.24 2087.31   46.29 2115.99   42.38 2125.24      38  2135.7   42.33
  2152.4   45.59  2328.2   42.55 2444.98   43.67 2495.34   49.79 2603.81   51.77
 2728.88   50.62  2906.4   54.04 3206.15   54.29 3480.75    51.9 3589.22   53.73
    3794   52.48 3868.33   52.45 3933.58   51.85 4076.72   59.72 4424.49   60.06
#Mann= 11 ,-1 , 0
       0    .045       0    5.31     .08       0  288.48    .045       0
 1032.68     .07       0 2115.99     .05       0  2135.7     .09       0
 2603.81    .045       0 3480.75     .08       0    3794     .07       0
 3868.33     .08       0 4076.72    .045       0
#XS Ineff= 2 , 0
       0    1000      56    2525       0      56
Permanent Ineff=
       F       F
Bank Sta=2115.99,2135.7
XS Rating Curve= 0 ,0
Exp/Cntr=0.3,0.1

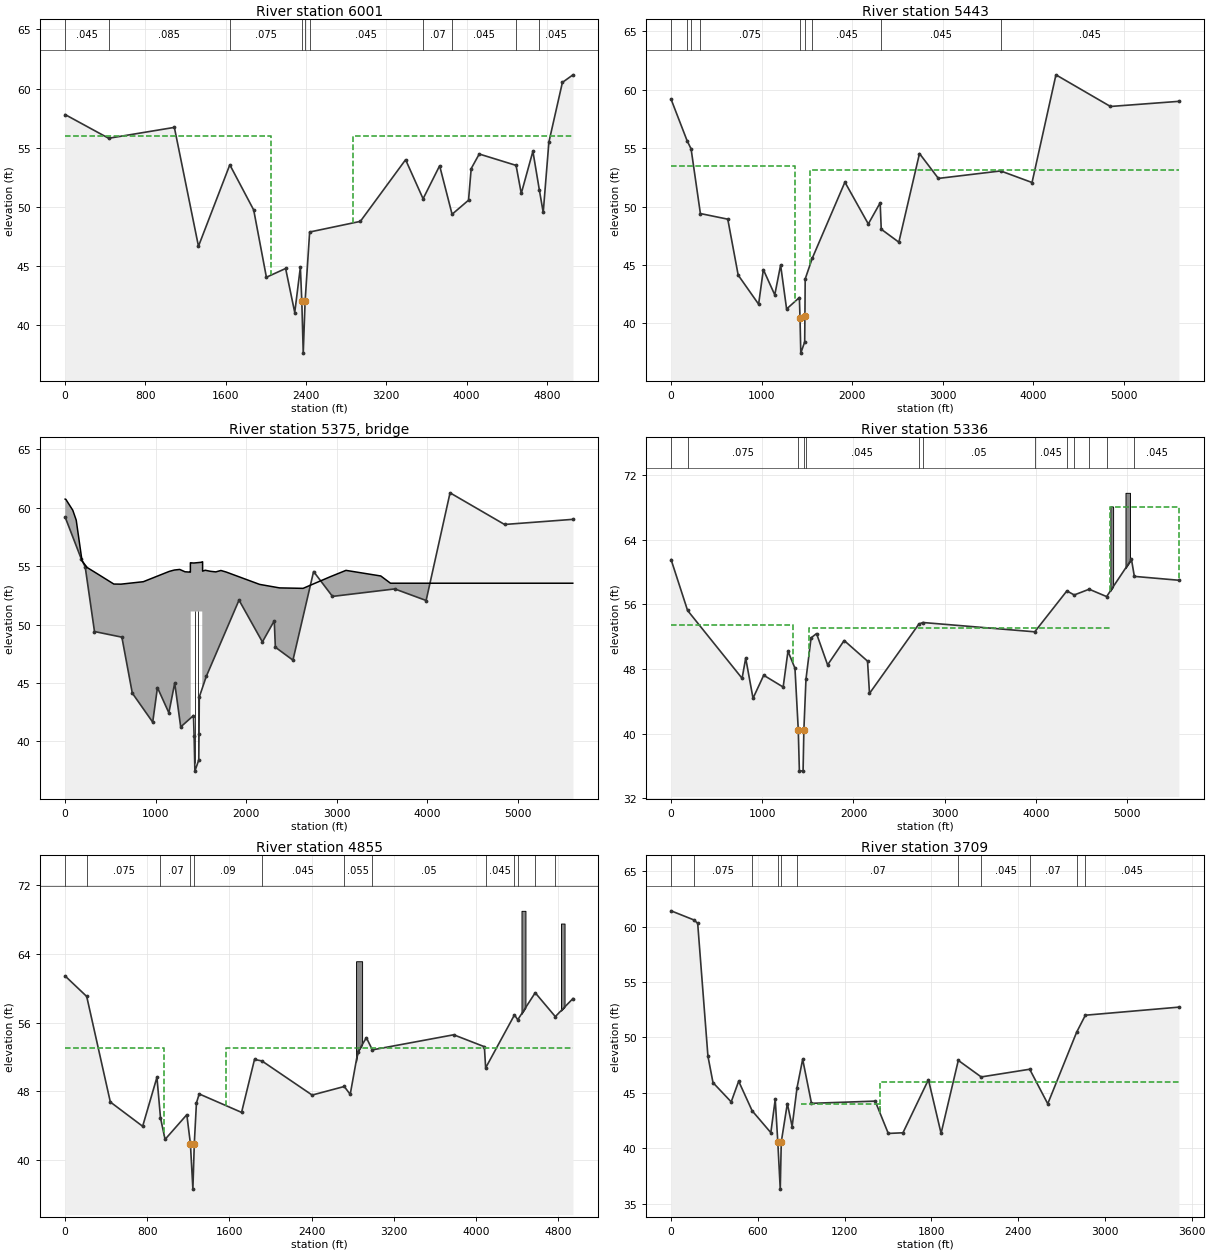
Type RM Length L Ch R = 1 ,6001    ,526.76,558.19,569.72
XS GIS Cut Line= 4
2370844.19731614643394.9842044712371816.41107641642942.682866484
2372786.37590846642002.8634541032374187.92785443639768.679967627
#Sta/Elev= 30
       0    57.8  433.16    55.8 1087.99   56.72 1328.22   46.68 1640.54   53.56
  1878.6   49.74 2005.18   44.06  2196.6    44.8 2287.63   41.08 2343.52   44.91
 2358.04   42.03 2372.24   37.65 2390.98   42.05 2436.02   47.88 2941.33   48.78
 3392.23   53.99 3566.48   50.69 3731.36   53.48 3855.42   49.38 4019.37   50.57
 4045.88   53.24 4125.99   54.47 4493.02   53.51  4544.9   51.14 4660.73    54.7
 4724.78   51.45 4763.62   49.53 4820.13   55.48 4954.82   60.52 5060.28   61.16
#Mann= 10 ,-1 , 0
       0    .045       0  433.16    .085       0 1640.54    .075       0
 2358.04     .05       0 2390.98     .09       0 2436.02    .045       0
 3566.48     .07       0 3855.42    .045       0 4493.02     .07       0
 4724.78    .045       0
#XS Ineff= 2 , 0
       0    2050      56    2870       0      56
Permanent Ineff=
       F       F
Bank Sta=2358.04,2390.98
XS Rating Curve= 0 ,0
Exp/Cntr=0.5,0.3

Type RM Length L Ch R = 1 ,5443    ,158.34,107.27,92.74
BEGIN DESCRIPTION:
Surveyed Section
END DESCRIPTION:
XS GIS Cut Line= 6
2372152.98824665643042.3040743022372256.24723226642763.596923128
2373062.65231407642362.9702854162373284.97188956642209.766112998
 2373533.4039088641973.7623746842375876.46942766638986.483719766
#Sta/Elev= 30
       0   59.19  177.28   55.63  221.04   54.94  323.7149.40142  626.22   48.92
  741.25   44.13  966.93   41.64 1019.17    44.6 1145.36   42.44 1209.89   44.99
 1276.01   41.231417.211   42.211424.343   40.42 1432.78   37.451475.742   38.41
1478.502   40.671481.418    43.8 1559.24  45.569 1920.14   52.09 2178.47   48.51
 2309.46   50.32  2321.5   48.06  2515.9   46.95 2743.96   54.54 2952.62   52.41
 3640.46   53.05 3987.11   52.06 4251.24   61.28  4853.3   58.57 5609.27   59.01
#Mann= 9 ,-1 , 0
       0    .045       0  177.28    .035       0  221.04    .085       0
  323.71    .075       01424.343     .05       01478.502     .09       0
 1559.24    .045       0  2321.5    .045       0 3640.46    .045       0
#XS Ineff= 2 , 0
       0    1367   53.46    1534       0    53.1
Permanent Ineff=
       T       T
Bank Sta=1424.343,1478.502
XS Rating Curve= 0 ,0
Exp/Cntr=0.5,0.3

Type RM Length L Ch R = 3 ,5375    ,,,
BEGIN DESCRIPTION:
RT 58
END DESCRIPTION:
Bridge Culvert--1,0,-1,-1, 0
Deck Dist Width WeirC Skew NumUp NumDn MinLoCord MaxHiCord MaxSubmerge Is_Ogee
21.16,41,2.6,0, 38, 38, , , 0.98, 0, 1,1,,
       0    6.71   83.95  121.93  186.03  241.52  344.45  537.16   615.8  863.06
1148.6651205.9131264.725 1323.461380.885    1383    1383    1387    13871420.433
1500.639    1514    1514    1518    15181547.0531605.2141663.1291720.109 1777.64
 2147.81 2367.63 2627.72 2929.37 3101.35 3486.27 3593.34 5606.75
   60.74   60.73   59.79   58.94   55.46   54.89    54.4   53.47   53.46   53.67
   54.55   54.67   54.72   54.52   54.49  54.489  55.289  55.287  55.287   55.27
   55.33  55.365  55.365  55.375  54.575   54.65   54.56   54.51   54.63    54.5
   53.44   53.14    53.1    54.1   54.64   54.16   53.54   53.54
                                                                                
                                                               0   51.12   51.12
   51.12   51.12       0
                                                                
       0    6.71   83.95  121.93  186.03  241.52  344.45  537.16   615.8  863.06
1148.6651205.9131264.725 1323.46    1358    1358    1362    13621380.8851420.433
    1489    1489    1493    14931500.6391547.0531605.2141663.1291720.109 1777.64
 2147.81 2367.63 2627.72 2929.37 3101.35 3486.27 3593.34  5571.8
   60.74   60.73   59.79   58.94   55.46   54.89    54.4   53.47   53.46   53.67
   54.55   54.67   54.72   54.52  54.502  55.302    55.3    55.3   55.29   55.27
  55.321  55.321  55.324  54.524   54.53   54.65   54.56   54.51   54.63    54.5
   53.44   53.14    53.1    54.1   54.64   54.16   53.54   53.54
                                                                                
                                                       0   51.12   51.12   51.12
   51.12       0
                                                                
Pier Skew, UpSta & Num, DnSta & Num=  ,1430.9, 4 ,1405.9, 4 , 3 , 3 , 0 ,,
       1       1     2.2     2.2
      34   48.12   48.12   51.12
       1       1     2.2     2.2
      34   48.12   48.12   51.12
Pier Skew, UpSta & Num, DnSta & Num=  ,1470.1, 4 ,1445.1, 4 , 3 , 3 , 0 ,,
       1       1     2.2     2.2
      34   48.12   48.12   51.12
       1       1     2.2     2.2
      34   48.12   48.12   51.12
Abutment Skew #Up #Dn= , 3 , 3
    1387 1408.95  1430.9
   51.12   44.13   41.96
    13621381.755  1405.9
   51.12   43.39   41.21
Abutment Skew #Up #Dn= , 3 , 3
  1470.11504.781    1514
   41.71   44.68   48.12
  1445.11459.148    1489
   42.02   44.29   51.12
BR Coef=-1 , 1 , 0 ,1.25, 0 ,,,0.8,0,2,0,
WSPro=,,,, 1 ,,,, 0 ,,,, 0 ,,,,-1 ,-1 ,-1 , 0 , 0 , 0 , 0 , 0
BC Design=,, 0 ,, 0 ,,,,,,
BC Use User HTab Curves=0
BC User HTab FreeFlow(D)= 0

Type RM Length L Ch R = 1 ,5336    ,455.79,480.99,431.08
BEGIN DESCRIPTION:
Surveyed Section
END DESCRIPTION:
XS GIS Cut Line= 6
2372264.42519017643082.2123714832372354.46903518642844.185307533
2372902.98189235642590.6444122642373101.33059296642468.583673462
2373622.61576836642039.4765362742375957.94194844639046.927647591
#Sta/Elev= 30
       0   61.54  180.99   55.24  778.67   46.84  818.34   49.34  898.63   44.37
 1015.91   47.22 1229.16   45.76 1281.86    50.21358.631   48.081394.701   40.49
1406.918   35.41 1447.54   35.351456.215   40.43 1479.31  46.734 1535.43   51.85
1595.094   52.38 1716.53    48.5 1898.15   51.52  2154.4   48.97 2175.96   44.97
 2717.11   53.55 2761.11   53.75 3987.9652.59666 4340.48   57.66 4421.23   57.16
 4584.96   57.87 4776.53   56.96 5048.73   61.57  5080.6   59.46    5569   58.98
#Mann= 13 ,-1 , 0
       0    .045       0  180.99    .075       01394.701     .05       0
1456.215    .035       0 1479.31    .045       0 2717.11    .055       0
 2761.11     .05       0 3987.96    .045       0 4340.48    .035       0
 4421.23    .055       0 4584.96     .09       0 4776.53    .055       0
  5080.6    .045       0
#XS Ineff= 3 ,-1
       0    1342   53.46    1509 4817.47    53.1 4817.47    5600  68.111
Permanent Ineff=
       F       F       F
#Block Obstruct= 2 ,-1
 4817.47 4847.74  68.111 4983.23 5032.64  69.804
Bank Sta=1394.701,1456.215
XS Rating Curve= 0 ,0
Exp/Cntr=0.5,0.3

Type RM Length L Ch R = 1 ,4855    ,1107.14,1145.15,1161.38
XS GIS Cut Line= 5
2372608.70326877643410.2501373142373625.48644374 642632.71006234
2373932.01666561642296.2744529842373976.87474684642172.914729565
 2375601.7657101639557.919678986
#Sta/Elev= 30
       0   61.43  209.67   59.05   439.7   46.74  754.44   43.91  893.55   49.62
   928.2   44.89  972.82   42.38 1184.52   45.26 1219.37    41.9 1243.66   36.58
 1257.41    41.9 1278.27   46.64 1305.21   47.68 1717.68   45.53 1843.61    51.7
 1915.7451.52988 2404.87   47.55 2717.84   48.55 2775.68   47.63 2850.06   52.58
 2933.18   54.24  2991.3   52.82 3783.37   54.58 4082.16   53.19 4094.56   50.72
 4375.44    56.9 4407.09   56.33  4577.2   59.48 4772.96    56.7 4945.12   58.81
#Mann= 13 ,-1 , 0
       0    .045       0  209.67    .075       0   928.2     .07       0
 1219.37     .05       0 1257.41     .09       0 1915.74    .045       0
 2717.84    .055       0  2991.3     .05       0 4094.56    .045       0
 4375.44    .035       0 4407.09    .055       0  4577.2     .09       0
 4772.96    .055       0
#XS Ineff= 2 , 0
       0     965      53    1570       0      53
Permanent Ineff=
       F       F
#Block Obstruct= 3 ,-1
 2832.77 2891.45  63.156  4443.6 4482.16  69.036 4828.32  4862.9  67.554
Bank Sta=1219.37,1257.41
XS Rating Curve= 0 ,0
Exp/Cntr=0.3,0.1

Type RM Length L Ch R = 1 ,3709    ,3850.61,3709.38,1897.24
XS GIS Cut Line= 4
2373343.95525674644159.1698219052375286.54181433642838.639428775
2375560.73603127642482.7710902652375553.14372079641769.093905088
#Sta/Elev= 30
       0   61.44  159.09   60.61  183.96   60.31  254.87   48.31   289.9   45.92
  415.78   44.18   467.4   46.05   560.5   43.38  689.91    41.4  720.25   44.41
  738.06   40.55  754.99    36.3  762.09   40.56  804.04   44.03  837.16   41.95
  870.95   45.45  910.04   48.03  971.07   44.05 1411.45   44.25 1502.16   41.33
 1603.66   41.39 1779.86   46.19 1867.25   41.34 1986.32   47.93 2144.7146.43449
  2480.1   47.13 2604.97   44.01  2804.6   50.47    2865   52.01 3511.89   52.74
#Mann= 11 ,-1 , 0
       0    .045       0  159.09    .075       0   560.5     .07       0
  738.06     .05       0  762.09     .09       0  870.95     .07       0
 1986.32     .08       0 2144.71    .045       0  2480.1     .07       0
  2804.6     .08       0    2865    .045       0
#XS Ineff= 2 ,-1
     900    1445      44    1445    3550      46
Permanent Ineff=
       T       T
Bank Sta=738.06,762.09
XS Rating Curve= 0 ,0
Exp/Cntr=0.3,0.1

Chan Stop Cuts=-1
Use User Specified Reach Order=0

--- DTL_Nahunta_Swamp.g02 (geometry) ---

Geom Title=before_change_N_vals
Program Version=4.00

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
River Reach=Nahunta Swamp   ,Main