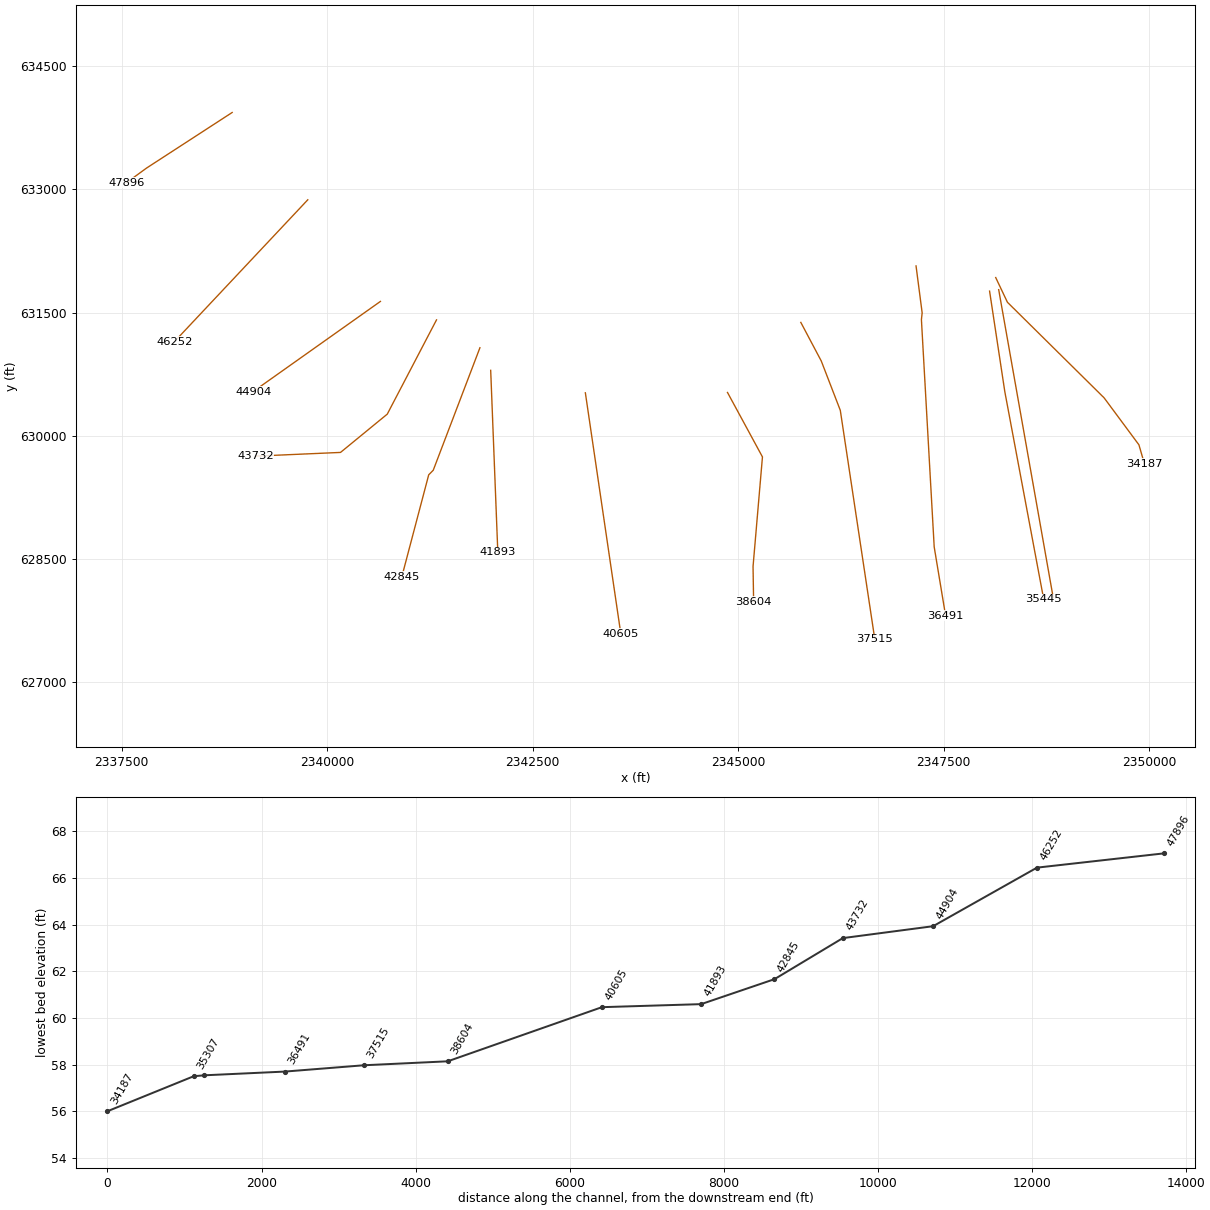
HEC-RAS study DTL_Nahunta_Swamp.prj: DTL_Nahunta_Swamp

--- DTL_Nahunta_Swamp.g02 (geometry) --- (continued)

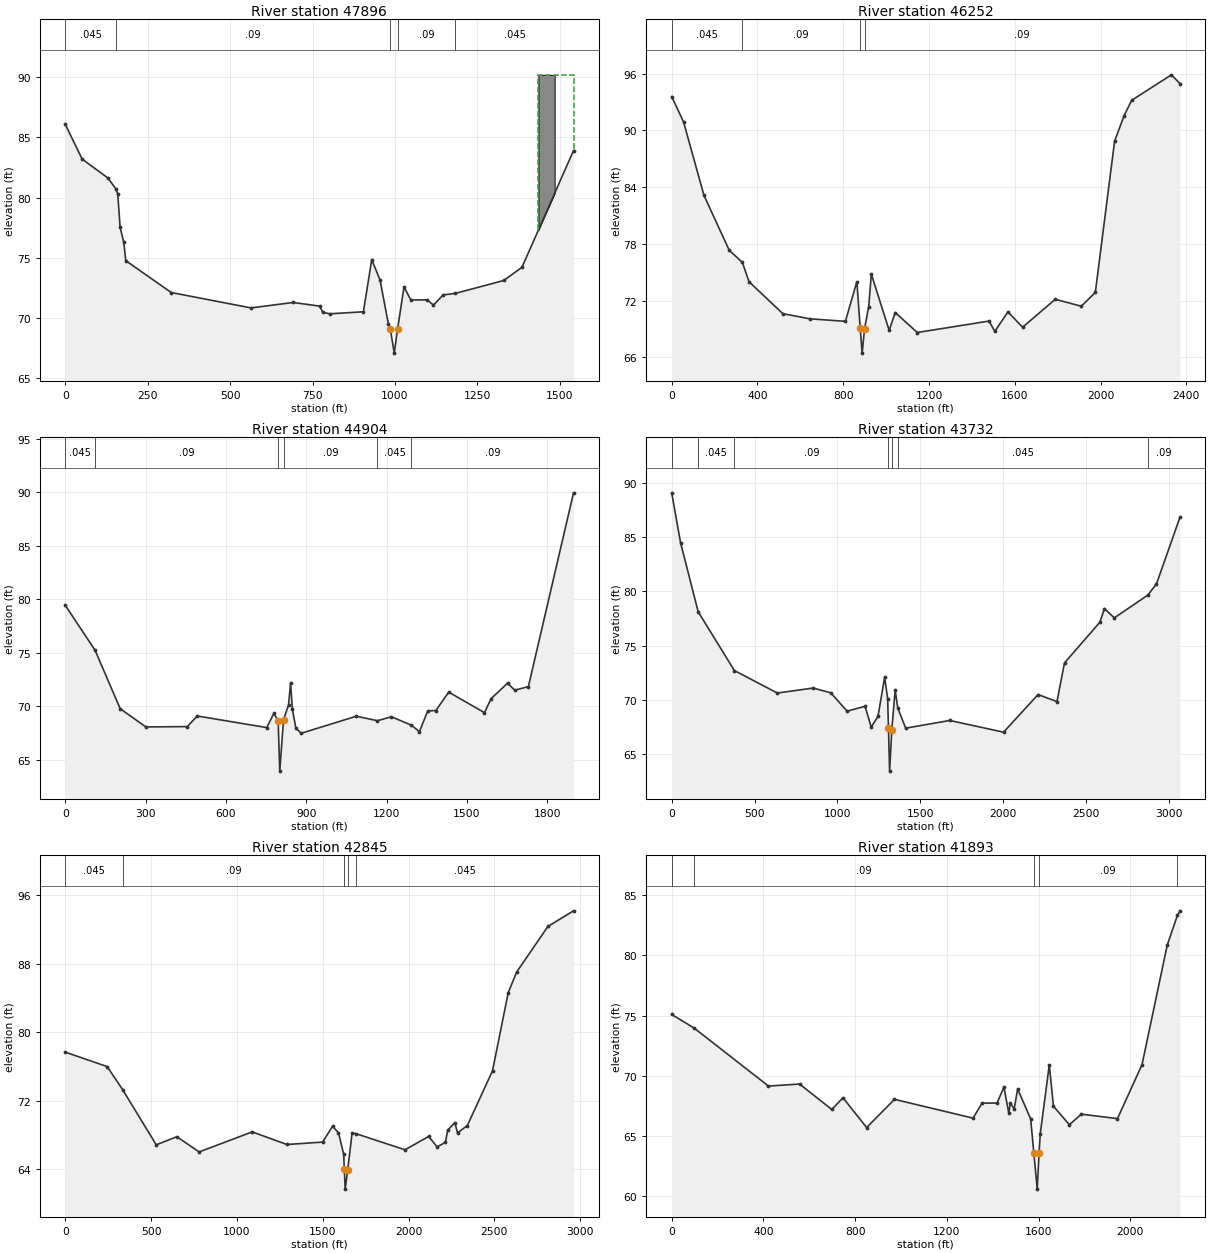
Type RM Length L Ch R = 1 ,47896   ,1534.36,1643.86,1727.95
XS GIS Cut Line= 3
2338843.65104169633936.7343750152337800.03645833633258.385416672
2337560.40104169633083.135416672
#Sta/Elev= 30
       0   86.09   51.45   83.19  129.62   81.62  153.23   80.73  159.27   80.32
  166.51   77.52  177.78   76.26  183.57   74.75  321.51    72.1  563.41   70.82
  691.25   71.27  771.62   70.97  781.66   70.44   803.7   70.33  904.34    70.5
  929.62   74.83  954.82   73.14  979.98    69.5  986.13   69.03  997.91   67.06
 1007.74   69.03 1027.46   72.56 1048.14   71.48 1097.54   71.49 1116.82   71.05
    1146    71.9 1183.47   72.03    1330    73.1 1385.22    74.2 1541.58    83.9
#Mann= 5 ,-1 , 0
       0    .045       0  153.23     .09       0  986.13     .05       0
 1007.74     .09       0 1183.47    .045       0
#XS Ineff= 2 , 0
       0                 1435.09       0    90.2
Permanent Ineff=
       F       F
#Block Obstruct= 1 ,-1
 1435.09  1484.3  90.197
Bank Sta=986.13,1007.74
XS Rating Curve= 0 ,0
Exp/Cntr=0.3,0.1

Type RM Length L Ch R = 1 ,46252   ,1411.14,1348.07,1245.98
XS GIS Cut Line= 2
2339763.42906073632873.1981812272338141.16532159631145.298663706
#Sta/Elev= 30
       0   93.57   55.28    90.9  150.48   83.13  268.65   77.31  329.44   76.05
  360.66      74  518.41   70.62  643.57   70.08  810.02   69.81  863.47      74
  879.05    69.1   888.2   66.45  899.19   69.02  918.66   71.36  930.92    74.8
 1014.08   68.86 1042.32   70.74 1145.16   68.63 1479.65   69.84 1506.58   68.75
 1567.81   70.81 1636.14   69.19 1788.43   72.14  1909.9   71.41 1975.35   72.87
 2065.22   88.86 2109.87   91.57 2144.97   93.18 2329.97   95.87  2370.1   94.94
#Mann= 4 ,-1 , 0
       0    .045       0  329.44     .09       0  879.05     .05       0
  899.19     .09       0
Bank Sta=879.05,899.19
XS Rating Curve= 0 ,0
Exp/Cntr=0.3,0.1

Type RM Length L Ch R = 1 ,44904   ,984.08,1171.92,1210.7
XS GIS Cut Line= 3
2340647.21875001631635.2552083282340000.00000001631176.182291687
2339098.92187501630537.041666687
#Sta/Elev= 30
       0   79.44  111.62   75.23   205.3   69.77  301.24   68.07   455.9    68.1
  493.21   69.09  752.66   68.01  779.37   69.34  795.17   68.64  801.17   63.94
  815.27   68.74  834.05   70.13  841.57   72.17   848.4   69.72  861.44   67.95
  881.74   67.48 1087.26   69.07 1166.09   68.65 1217.98   69.02 1293.08   68.23
  1322.8   67.62 1353.74   69.57 1384.09    69.6  1432.2   71.32 1565.74    69.4
 1590.28   70.71 1651.77   72.15 1678.81    71.5 1729.65   71.84 1898.24   89.94
#Mann= 6 ,-1 , 0
       0    .045       0  111.62     .09       0  795.17     .05       0
  815.27     .09       0 1166.09    .045       0 1293.08     .09       0
Bank Sta=795.17,815.27
XS Rating Curve= 0 ,0
Exp/Cntr=0.3,0.1

Type RM Length L Ch R = 1 ,43732   ,760.13,887.18,1140.5
XS GIS Cut Line= 4
2341329.59975713631410.5281335412340730.69931428630262.561193377
2340162.00556245629795.9057941442339126.33923699629750.537330702
#Sta/Elev= 30
       0   89.09   53.83   84.48   159.8   78.13  378.48    72.7  637.91   70.63
   853.8   71.09  959.93   70.65 1058.69   68.96 1166.96   69.41 1203.84   67.49
 1244.87   68.47 1284.88   72.08  1303.2   70.12  1308.1   67.37 1314.96   63.43
  1328.2   67.24 1348.57   70.89 1364.25   69.25    1412   67.39 1678.04    68.1
  2002.4   67.02 2210.72   70.49 2324.77   69.84 2370.31   73.41 2583.81   77.16
 2611.34   78.42 2670.59   77.56 2872.35   79.65 2924.78   80.68 3067.11   86.85
#Mann= 7 ,-1 , 0
       0     .09       0   159.8    .045       0  378.48     .09       0
  1308.1     .05       0  1328.2     .09       0 1364.25    .045       0
 2872.35     .09       0
Bank Sta=1308.1,1328.2
XS Rating Curve= 0 ,0
Exp/Cntr=0.3,0.1

Type RM Length L Ch R = 1 ,42845   ,568.87,951.82,964
XS GIS Cut Line= 4
2341857.77864893631070.9845602662341290.01290861629579.118306071
2341234.75073077629522.7933940892340907.05664368 628279.18184638
#Sta/Elev= 30
       0   77.66  244.67   75.97   335.8   73.24  530.47   66.84  650.19   67.79
   780.3   66.01 1089.31   68.35 1291.57   66.88 1499.68   67.16 1557.14      69
 1591.84   68.26 1622.46   65.72 1625.58   64.07 1631.05   61.67 1645.42   63.88
 1671.01   68.18 1691.4568.16017  1979.5   66.26 2117.34   67.82 2166.63    66.6
 2214.85   67.13 2228.43   68.55 2269.72   69.44 2285.28   68.24 2342.35   69.08
 2489.31   75.48 2580.68    84.6 2630.04   87.01 2812.16   92.33 2961.22   94.15
#Mann= 5 ,-1 , 0
       0    .045       0   335.8     .09       0 1625.58     .05       0
 1645.42     .09       0 1691.45    .045       0
Bank Sta=1625.58,1645.42
XS Rating Curve= 0 ,0
Exp/Cntr=0.3,0.1

Type RM Length L Ch R = 1 ,41893   ,1224.8,1287.83,1339.02
XS GIS Cut Line= 3
2341988.80208333630795.8750000152342019.92708334630000.000000015
2342075.44270833628580.395833343
#Sta/Elev= 30
       0   75.09   96.89   73.98  422.15   69.15  557.68   69.32  698.42   67.21
  747.16   68.18  850.37   65.71  971.77   68.05 1314.38   66.49 1354.19   67.74
 1419.17   67.74 1449.35   69.07 1470.34    66.9 1477.03   67.75 1493.89   67.24
 1508.97   68.91 1565.92   66.42  1579.7   63.59  1594.4    60.6 1602.41   63.59
  1607.6   65.18    1647   70.91 1665.16   67.48 1734.68   65.94 1786.79   66.82
 1944.39   66.45 2051.56   70.93 2161.54   80.85 2206.09   83.32 2217.17   83.69
#Mann= 5 ,-1 , 0
       0    .045       0   96.89     .09       0  1579.7     .05       0
 1602.41     .09       0 2206.09    .045       0
Bank Sta=1579.7,1602.41
XS Rating Curve= 0 ,0
Exp/Cntr=0.3,0.1

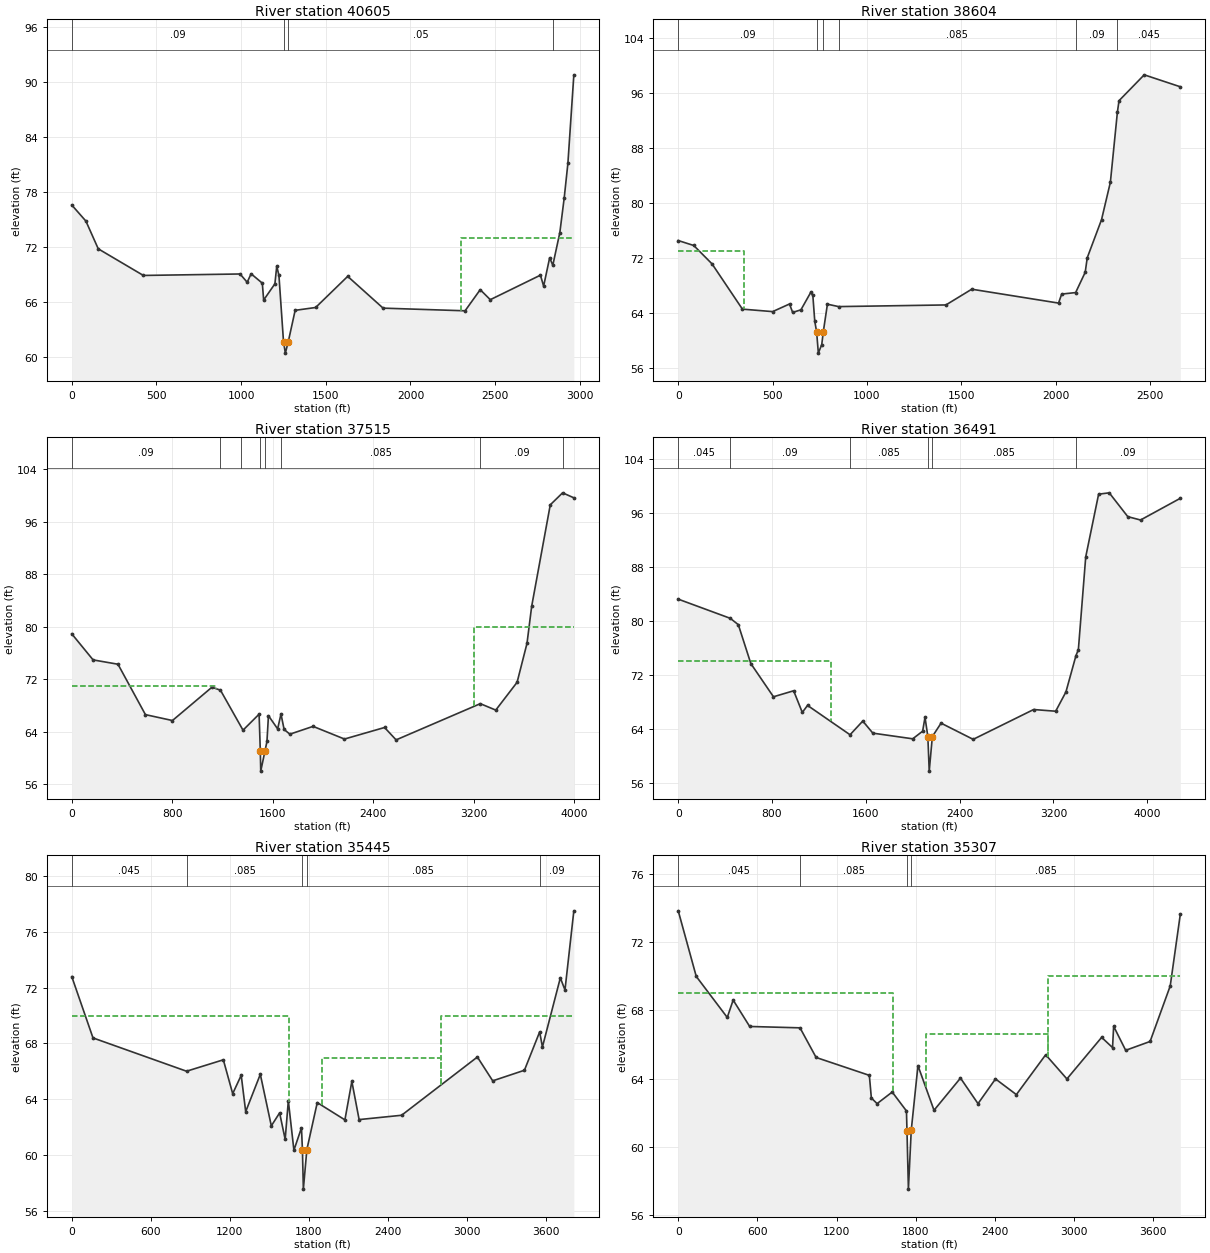
Type RM Length L Ch R = 1 ,40605   ,1913.93,2001.63,1895
XS GIS Cut Line= 3
2343140.48958334630522.0104166872343217.18229167630000.000000015
   2343571.40625627588.989583343
#Sta/Elev= 30
       0    76.6   83.47   74.85  156.36   71.83  422.73   68.93   993.5   69.09
 1035.72   68.19 1058.89   69.11 1125.04   68.09 1133.03   66.25 1199.37   68.02
 1210.32   69.94 1223.18   68.94 1250.33   61.69 1261.09   60.47 1278.08   61.69
 1318.93   65.13 1439.89   65.44 1629.23   68.83 1838.23   65.37 2322.31   65.08
 2411.68   67.38  2471.1   66.29 2767.16   68.96 2786.09   67.77 2821.71   70.86
 2840.29   70.04 2881.69   73.59  2907.6   77.37 2929.39   81.14  2964.5   90.78
#Mann= 4 ,-1 , 0
       0     .09       0 1250.33     .05       0 1278.08     .05       0
 2840.29     .09       0
#XS Ineff= 2 , 0
       0                    2300       0      73
Permanent Ineff=
       F       F
Bank Sta=1250.33,1278.08
XS Rating Curve= 0 ,0
Exp/Cntr=0.3,0.1

Type RM Length L Ch R = 1 ,38604   ,1135.28,1088.48,1161.6
XS GIS Cut Line= 5
  2344869.546875630526.3489583282345154.65104167 630000.00000003
  2345294.859375629741.1614583282345180.42708334628406.119791672
 2345187.3837453627978.705024347
#Sta/Elev= 30
       0   74.53    82.3   73.81  179.24   71.13  340.08   64.55  500.15   64.19
  589.64    65.3  606.24   64.07   650.1   64.45  701.97   66.98  713.28   66.54
  723.43   62.79  733.32   61.24  742.38   58.15   760.5    59.4  768.63   61.25
  790.47   65.27  849.73   64.92 1418.43   65.16 1555.23   67.45 2015.23   65.43
 2031.75   66.74  2105.7   66.96 2156.43   69.91 2167.31   72.03  2242.9   77.56
 2289.87   83.02 2327.04   93.22 2335.69   94.88 2469.16   98.64 2660.39    96.9
#Mann= 6 ,-1 , 0
       0     .09       0  733.32     .05       0  768.63     .09       0
  849.73    .085       0  2105.7     .09       0 2327.04    .045       0
#XS Ineff= 2 , 0
       0     350      73               0
Permanent Ineff=
       F       F
Bank Sta=733.32,768.63
XS Rating Curve= 0 ,0
Exp/Cntr=0.3,0.1

Type RM Length L Ch R = 1 ,37515   ,1048,1023.91,945.52
XS GIS Cut Line= 4
2345761.57042955631379.656923249  2346010.016591  630910.3697294
  2346241.899675630308.5779161162346661.49763656 627520.45988211
#Sta/Elev= 30
       0    78.9   169.7   74.93  367.61   74.27   586.2   66.59  801.18   65.69
 1115.06   70.76 1183.05   70.32 1362.77   64.22 1490.75   66.66 1500.23   61.11
 1503.79   57.98 1538.37   61.12 1553.24    62.5 1565.13   66.43 1638.26   64.42
  1664.966.67546 1689.93   64.33 1735.69   63.61 1920.42    64.8 2170.11   62.87
 2489.23   64.63 2580.94   62.74 3251.08   68.26 3374.05   67.28 3543.89   71.52
 3622.64   77.45 3659.85    83.1 3807.84   98.56 3905.93  100.39 3995.43   99.63
#Mann= 8 ,-1 , 0
       0     .09       0 1183.05    .085       0 1344.46     .09       0
 1500.23     .05       0 1538.37     .09       0  1664.9    .085       0
 3251.08     .09       0 3905.93    .045       0
#XS Ineff= 2 , 0
       0    1150      71    3200       0      80
Permanent Ineff=
       T       F
Bank Sta=1500.23,1538.37
XS Rating Curve= 0 ,0
Exp/Cntr=0.3,0.1

Type RM Length L Ch R = 1 ,36491   ,973.55,1046.9,1107.47
XS GIS Cut Line= 6
2347163.33903968632067.8913092322347237.78645833   631495.515625
2347228.73958333631414.1197916722347308.10416669 630000.00000003
2347384.19791669628644.1770833282347522.77766292627807.553224221
#Sta/Elev= 30
       0    83.2  443.55   80.36  512.29   79.42  619.13   73.65  812.08   68.73
   984.1   69.62 1057.96   66.41 1102.59   67.45  1465.1    63.1 1573.51   65.13
 1659.55   63.34  1999.6    62.5 2084.14   63.63 2104.37   65.69 2128.48   62.84
  2140.3   57.71 2167.02   62.84 2241.31   64.82 2515.14   62.42 3030.67   66.84
 3218.61   66.59 3305.91   69.44 3391.74   74.84 3412.04   75.71 3474.91   89.47
 3584.77   98.76 3675.38   98.96 3833.47   95.43 3942.25   94.93 4281.42   98.15
#Mann= 6 ,-1 , 0
       0    .045       0  443.55     .09       0  1465.1    .085       0
 2128.48     .05       0 2167.02    .085       0 3391.74     .09       0
#XS Ineff= 2 , 0
       0    1300      74               0
Permanent Ineff=
       F       F
Bank Sta=2128.48,2167.02
XS Rating Curve= 0 ,0
Exp/Cntr=0.5,0.3

Type RM Length L Ch R = 1 ,35445   ,142.13,137.99,133.16
XS GIS Cut Line= 3
2348057.94615354631760.8064610722348243.38195162630535.121063981
2348716.01709551628009.123668136
#Sta/Elev= 30
       0    72.8  161.04    68.4  870.84   66.01 1149.98   66.83 1220.92    64.4
 1285.65   65.72 1319.61   63.11 1430.59   65.79 1514.04   62.09 1577.05   63.02
 1619.15   61.12 1643.17   63.89 1685.49   60.34 1742.87   61.95 1750.03   60.39
 1757.16   57.55  1783.8   60.39 1862.65   63.76 2072.44   62.52 2125.05   65.28
 2180.27   62.54 2502.53   62.85 3077.55   67.03 3193.92   65.32 3434.53   66.08
 3550.04   68.83 3571.09   67.75 3707.01   72.71 3742.22   71.84 3809.47   77.52
#Mann= 5 ,-1 , 0
       0    .045       0  870.84    .085       0 1750.03     .05       0
  1783.8    .085       0 3550.04     .09       0
#XS Ineff= 3 ,-1
       0  1644.5      70  1895.5    2800   66.95    2800    3810      70
Permanent Ineff=
       F       F       F
Bank Sta=1750.03,1783.8
XS Rating Curve= 0 ,0
Exp/Cntr=0.5,0.3

Type RM Length L Ch R = 1 ,35307   ,653.45,1119.19,1264.4
XS GIS Cut Line= 2
2348168.75534996631778.897758439 2348831.1420856628031.427967727
#Sta/Elev= 30
       0   73.85  136.49      70   371.6   67.59  416.35   68.61  541.47   67.06
  923.08   66.98 1045.11   65.24  1448.5   64.19 1463.82   62.86 1507.31   62.53
 1621.87   63.21 1729.82    62.1 1733.76   60.94 1744.59   57.51 1766.19   60.97
 1816.97   64.76 1938.74   62.14 2139.43   64.03 2272.14   62.53 2404.69   63.98
 2562.89   63.06  2785.2    65.4    2946   63.98 3209.25   66.42 3291.93   65.82
 3300.25   67.07 3391.51   65.66 3576.62   66.18 3729.11   69.44 3805.56   73.65
#Mann= 4 ,-1 , 0
       0    .045       0  923.08    .085       0 1733.76     .05       0
 1766.19    .085       0
#XS Ineff= 3 ,-1
       0  1625.5      69  1876.5    2800    66.6    2800    3810      70
Permanent Ineff=
       F       F       F
Bank Sta=1733.76,1766.19
XS Rating Curve= 0 ,0
Exp/Cntr=0.5,0.3

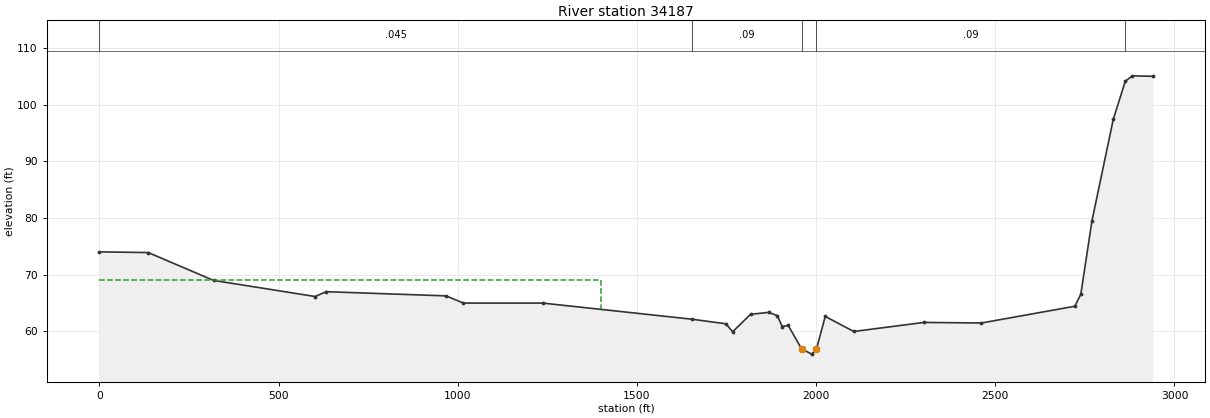
Type RM Length L Ch R = 1 ,34187   ,418.51,437.81,493.24
XS GIS Cut Line= 5
 2348132.5727552631925.8895495982348275.06518134631625.168185115
2349451.64112349630460.3153654342349874.98375389629888.219969347
2349941.28556225629658.157939285
#Sta/Elev= 30
       0   74.04  136.43   73.92  318.58   69.01  602.08   66.17  632.84   67.02
  967.61   66.28 1015.87   65.01 1237.28   65.01 1653.21   62.17 1748.48   61.36
 1767.18   59.95 1817.16   63.03 1867.48   63.37 1891.67   62.81 1905.47   60.88
 1922.35   61.07 1959.66   56.93 1987.89   56.01 2001.07    56.9 2025.61   62.66
 2105.11      60 2300.81    61.6 2461.57    61.5 2721.89   64.45 2738.74   66.55
 2769.89   79.51 2829.37   97.41 2862.83  104.13 2882.62  105.08  2939.5     105
#Mann= 5 ,-1 , 0
       0    .045       0 1653.21     .09       0 1959.66     .05       0
 2001.07     .09       0 2862.83    .045       0
#XS Ineff= 2 , 0
       0    1400      69               0
Permanent Ineff=
       T       F
Bank Sta=1959.66,2001.07
XS Rating Curve= 0 ,0
Exp/Cntr=0.3,0.1