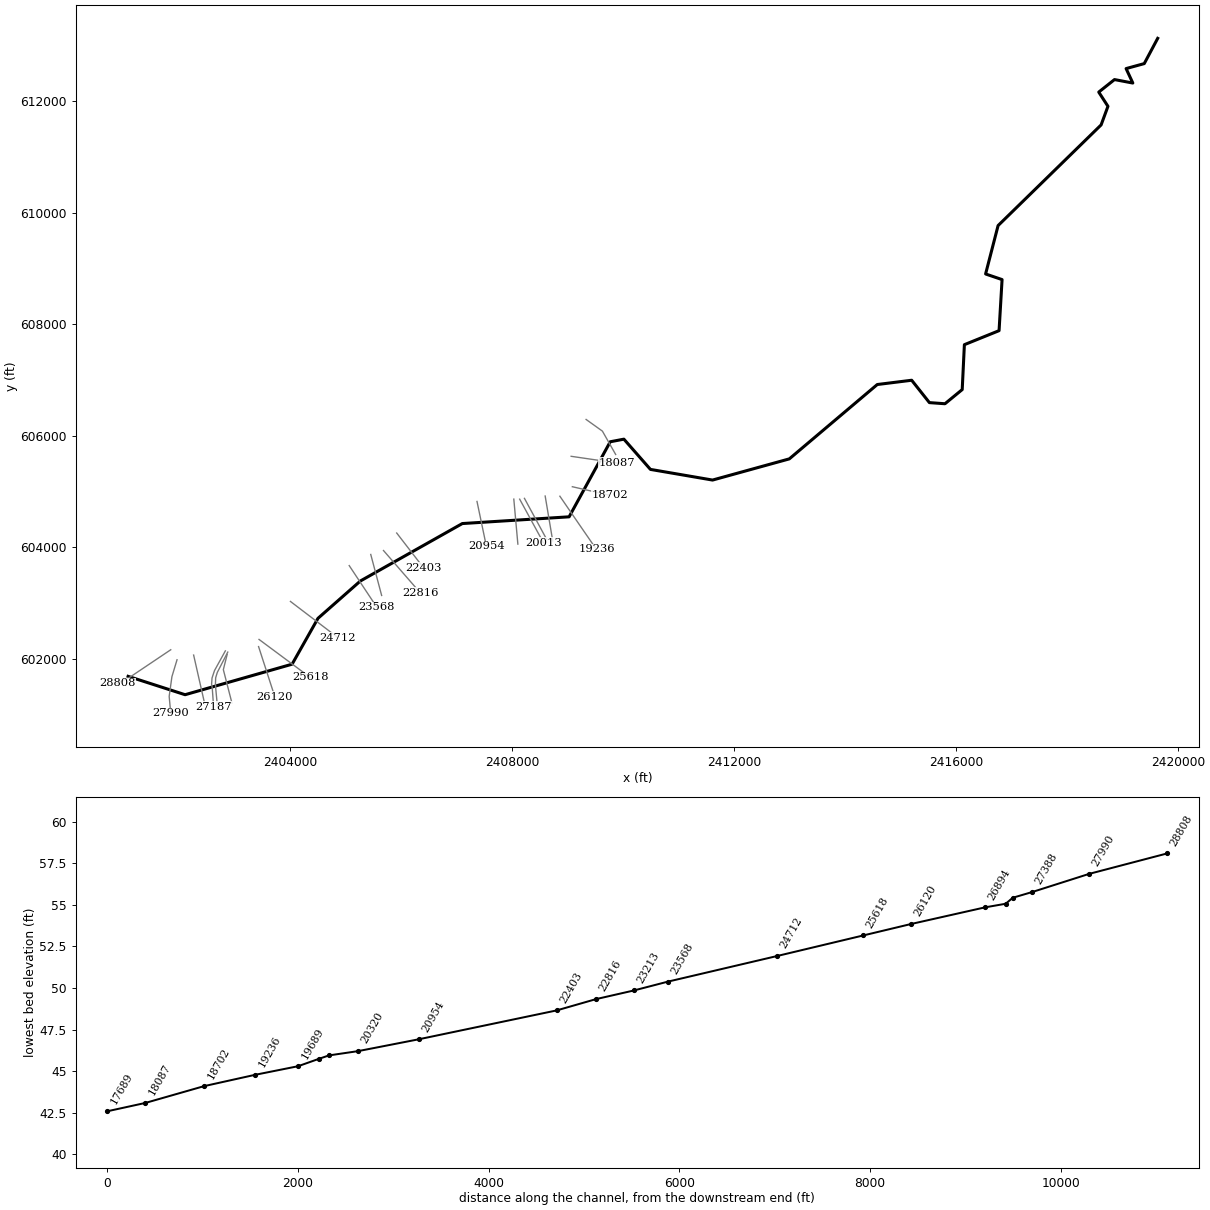
--- DTL_Rainbow_Creek.prj (project) ---

Proj Title=DTL_Rainbow_Creek
Current Plan=p01
Default Exp/Contr=0.3,0.1
English Units
Geom File=g01
Geom File=g02
Flow File=f01
Flow File=f02
Plan File=p01
Plan File=p06
Y Axis Title=Elevation
X Axis Title(PF)=Main Channel Distance
X Axis Title(XS)=Station
BEGIN DESCRIPTION:
END DESCRIPTION:
DSS Export Rating Curves= 0
DSS Export Rating Curve Sorted= 0
DSS Export Volume Flow Curves= 0
DXF OffsetX= 0
DXF OffsetY= 0
DXF ScaleX= 1
DXF ScaleY= 10

--- DTL_Rainbow_Creek.p01 (plan) ---

Plan Title=DTL_Rainbow_Creek
Program Version=4.00
Short Identifier=Mulit-Profile
Geom File=g01
Flow File=f01
Subcritical Flow
K Sum by GR= 0
Std Step Tol= 0.01
Critical Tol= 0.01
Num of Std Step Trials= 20
Max Error Tol= 0.3
Flow Tol Ratio= 0.001
Split Flow NTrial= 30
Split Flow Tol= 0.02
Split Flow Ratio= 0.02
Log Output Level= 0
Friction Slope Method= 1
Unsteady Friction Slope Method= 2
Unsteady Bridges Friction Slope Method= 1
Parabolic Critical Depth
Global Vel Dist= 0 , 0 , 0
Global Log Level= 0
CheckData=True
Encroach Param=-1 ,10,10, 2
Encroach River=Rainbow_Crk
Encroach Reach=Main
Encroach Node=28808
       1     705     925
Encroach Node=27990
       1     615     835
Encroach Node=27388
       1     465     655
Encroach Node=27187
       1     540     690
Encroach Node=27113
       1     500     650
Encroach Node=26894
       1     360     505
Encroach Node=26120
       1     410     555
Encroach Node=25618
       1     630     775
Encroach Node=24712
       1     455     615
Encroach Node=23568
       1     215     385
Encroach Node=23213
       1     295     420
Encroach Node=22816
       1     270     445
Encroach Node=22403
       1     415     590
Encroach Node=20954
       1     275     380
Encroach Node=20320
       1     320     410
Encroach Node=20013
       1     425     486
Encroach Node=19910
       1     425     510
Encroach Node=19689
       1     420     510
Encroach Node=19236
       1     350     480
Encroach Node=18702
       1     255     390
Encroach Node=18087
       1     410     545
Encroach Node=17689
       1     490     625
Encroach Node=17435
       1     510     645
Encroach Node=17203
       1  654.09  724.09
Encroach Node=17069
       1  761.59  831.59
Encroach Node=16830
       1     570     735
Encroach Node=16321
       1     240     440
Encroach Node=15971
       1     485     680
Encroach Node=15007
       1     420     580
Encroach Node=14115
       1     550     710
Encroach Node=13447
       1     643  838.03
Encroach Node=12163
       1     565     755
Encroach Node=11462
       1     320     490
Encroach Node=10956
       1     235     405
Encroach Node=10419
       1     365     525
Encroach Node=9937
       1     250     410
Encroach Node=9538
       1     250     410
Encroach Node=9188
       1     210     370
Encroach Node=8892
       1     300     460
Encroach Node=8597
       1     430     560
Encroach Node=8094
       1     580     690
Encroach Node=7938
       1  513.75  606.85
Encroach Node=7865
       1  472.74  555.84
Encroach Node=7714
       1     383  516.53
Encroach Node=7199
       1     310     450
Encroach Node=6600
       1     385     535
Encroach Node=6038
       1     595     755
Encroach Node=5667
       1     465     625
Encroach Node=5370
       1     410     570
Encroach Node=4387
       1     420     590
Encroach Node=3725
       1     630     850
Encroach Node=2679
       1     400     645
Encroach Node=2276
       1     250     460
Encroach Node=1910
       1     260     460
Encroach Node=1368
       1     435     625
Encroach Node=1257
       1  450.55  640.55
Encroach Node=1112
       1  348.66  538.66
Encroach Node=985
       1     260     410
Encroach Node=565
       1     410     550
Encroach Node=386
       1     300     420
Encroach Node=183
       1     325     420
Computation Interval=1HOUR
Output Interval=1HOUR
Run HTab= 0
Run UNet= 0
Run PostProcess= 0
Run WQNet= 0
UNET Theta= 1
UNET Theta Warmup= 1
UNET ZTol= 0.02
UNET ZSATol= 0.05
UNET MxIter= 20
UNET MaxInSteps= 0
UNET DtIC= 0
UNET DtMin= 0
UNET MaxCRTS= 20
UNET WFStab= 2
UNET SFStab= 1
UNET WFX= 1
UNET SFX= 1
UNET DSS MLevel= 4
UNET DZMax Abort= 100
UNET Convert EG Bridges= 0
UNET Use Existing IB Tables=-1
UNET Froude Reduction=False
UNET Froude Limit= 1
UNET Froude Power= 10
UNET Time Slicing=0,0, 5
Instantaneous Interval=1HOUR
Write IC File= 0
Echo Input=False
Echo Output=False
Write Detailed= 0
Detailed Automatic Start=False, 10
WQ ULTIMATE=-1
WQ Max Comp Step=1HOUR
WQ Output Interval=15MIN
WQ Output Selected Increments= 0
WQ Output face flow=0
WQ Output face velocity=0
WQ Output face area=0
WQ Output face dispersion=0
WQ Output cell volume=0
WQ Output cell surface area=0
WQ Output cell continuity=0
WQ Output face conc=0
WQ Output face dconc_dx=0
WQ Output face courant=0
WQ Output face peclet=0
WQ Output face adv mass=0
WQ Output face disp mass=0
WQ Output cell mass=0
WQ Output cell source sink temp=0
WQ Output cell source sink nsm=0
WQ Output MaxMinRange=-1
WQ Daily Max Min Mean=-1
WQ Daily Range=0
WQ Daily Time=0
WQ Create Restart=0
WQ Fixed Restart=0
WQ System Summary=False
Sorting and Armoring Iterations= 10
XS Update Threshold= 0.02
Hydraulics Update Threshold= 0.02
Energy Slope Method= 1
Volume Change Method= 0
XS Weighting Method= 0
Number of US Weighted Cross Sections= 1
Number of DS Weighted Cross Sections= 1
Upstream XS Weight=0.25
Main XS Weight=0.5
Downstream XS Weight=0.25
Number of DS XS's Weighted with US Boundary= 1
Upstream Boundary Weight= 1
Weight of XSs Associated with US Boundary= 0
Number of US XS's Weighted with DS Boundary= 1
Downstream Boundary Weight= 0.5
Weight of XSs Associated with DS Boundary= 0.5
Sediment Output Level= 4
Mass or Volume Output= 0
Output Increment Type= 1
Profile and TS Output Increment= 10
XS Output Flag= 0
XS Output Increment= 10
Disregard all LS=0
Disregard all Conn=0
Disregard all Breaches=0
Disregard all Pumps=0

--- DTL_Rainbow_Creek.p06 (plan) ---

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Plan Title=DTL_Rainbow_Creek_Future
Short Identifier=Future
Geom File=g01
Flow File=f02
Encroach Param=-1 ,0,0, 0

--- DTL_Rainbow_Creek.f01 (steady flow) ---

Flow Title=DTL_Rainbow_Creek
Program Version=4.00
Number of Profiles= 6
Profile Names=100-yr,FWay,10-yr,25-yr,50-yr,500-yr
River Rch & RM=Rainbow_Crk,Main            ,28808
    1300    1300     570     820    1040    2040
River Rch & RM=Rainbow_Crk,Main            ,27990
    1450    1450     640     920    1170    2270
River Rch & RM=Rainbow_Crk,Main            ,23213
    1510    1510     670     960    1210    2350
River Rch & RM=Rainbow_Crk,Main            ,19236
    1650    1650     740    1050    1330    2570
River Rch & RM=Rainbow_Crk,Main            ,17435
    1870    1870     850    1200    1510    2890
River Rch & RM=Rainbow_Crk,Main            ,14115
    1960    1960     890    1260    1590    3020
River Rch & RM=Rainbow_Crk,Main            ,12163
    2040    2040     930    1310    1650    3140
River Rch & RM=Rainbow_Crk,Main            ,9538
    2110    2110     970    1360    1720    3250
River Rch & RM=Rainbow_Crk,Main            ,5370
    2160    2160     990    1390    1750    3310
Boundary for River Rch & Prof#=Rainbow_Crk,Main            , 1
Up Type= 0
Dn Type= 3
Dn Slope=0.00102
Boundary for River Rch & Prof#=Rainbow_Crk,Main            , 2
Up Type= 0
Dn Type= 3
Dn Slope=0.00102
Boundary for River Rch & Prof#=Rainbow_Crk,Main            , 3
Up Type= 0
Dn Type= 3
Dn Slope=0.00102
Boundary for River Rch & Prof#=Rainbow_Crk,Main            , 4
Up Type= 0
Dn Type= 3
Dn Slope=0.00102
Boundary for River Rch & Prof#=Rainbow_Crk,Main            , 5
Up Type= 0
Dn Type= 3
Dn Slope=0.00102
Boundary for River Rch & Prof#=Rainbow_Crk,Main            , 6
Up Type= 0
Dn Type= 3
Dn Slope=0.00102
DSS Import GetInterval= 0
DSS Import GetPeak= 0
DSS Import FillOption= 0

--- DTL_Rainbow_Creek.f02 (steady flow) ---

Flow Title=DTL_Rainbow_Creek_Future
Program Version=4.00
Number of Profiles= 3
Profile Names=100-yr 10%,100-yr 20%,100-yr 35%
River Rch & RM=Rainbow_Crk,Main            ,28808
    2220    2840    3470
River Rch & RM=Rainbow_Crk,Main            ,27990
    2470    3160    3860
River Rch & RM=Rainbow_Crk,Main            ,23213
    2560    3280    4010
River Rch & RM=Rainbow_Crk,Main            ,19236
    2800    3590    4390
River Rch & RM=Rainbow_Crk,Main            ,17435
    3160    4050    4940
River Rch & RM=Rainbow_Crk,Main            ,14115
    3310    4240    5180
River Rch & RM=Rainbow_Crk,Main            ,12163
    3430    4400    5370
River Rch & RM=Rainbow_Crk,Main            ,9538
    3550    4560    5570
River Rch & RM=Rainbow_Crk,Main            ,5370
    3630    4650    5680
Boundary for River Rch & Prof#=Rainbow_Crk,Main            , 1
Up Type= 0
Dn Type= 3
Dn Slope=0.00102
Boundary for River Rch & Prof#=Rainbow_Crk,Main            , 2
Up Type= 0
Dn Type= 3
Dn Slope=0.00102
Boundary for River Rch & Prof#=Rainbow_Crk,Main            , 3
Up Type= 0
Dn Type= 3
Dn Slope=0.00102
DSS Import GetInterval= 0
DSS Import GetPeak= 0
DSS Import FillOption= 0

--- DTL_Rainbow_Creek.g01 (geometry) ---

Geom Title=DTL_Rainbow_Creek
Program Version=4.00

River Reach=Rainbow_Crk     ,Main
Reach XY= 30
2401079.25000001      601688.1252402105.99677368601358.799475312
2404033.55617923601905.758602157 2404500.0431587602728.083358333
2405263.27118161603397.008083567 2407100.2994214604426.800094768
2409024.08669509604547.5083158462409764.68192656 605892.90203014
2410011.12787798605939.4249903412410488.93125314605397.495372728
2411607.99705283605206.3740226632412991.11208622605586.101968169
2414575.40748805606918.9219094222415195.29449847606995.621924922
2415514.66833341606594.5185652382415795.06347203606574.400528371
2416105.63566585606828.3907435982416144.61436225 607633.11221756
2416769.53088188607884.5876781492416823.59810589608799.958354771
2416526.85706238608900.5485390282416751.92759964609768.138878137
2418607.81649895611572.4753080012418731.03947462611905.680293337
2418565.06567062612160.9278858452418848.97337444612385.162663192
2419179.30920015 612322.90922235 2419057.9575734612582.149282366
2419384.87567224612671.4230708782419627.24353722613124.355529264

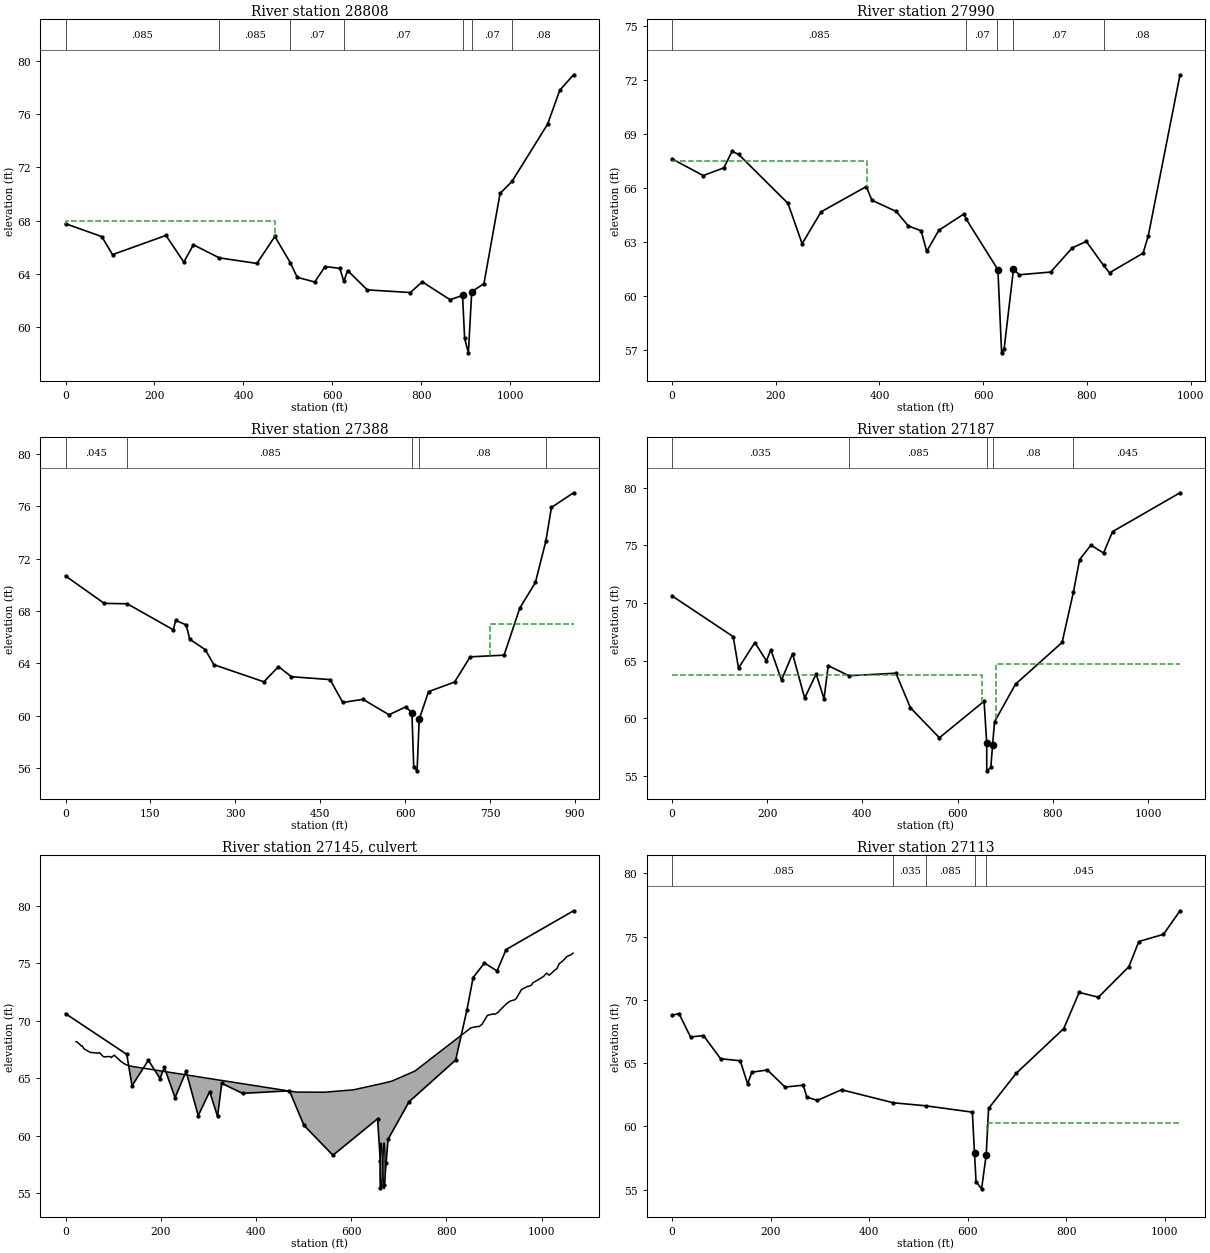
Type RM Length L Ch R = 1 ,28808   ,637.69,818.08,960.25
XS GIS Cut Line= 3
2401847.49999999      602164.6252401095.74999999601662.437500015
2400879.25000004     601563.5625
#Sta/Elev= 30
       0   67.78   81.65   66.81  105.65   65.46  225.82    66.9  265.96    64.9
  287.49    66.2  345.48   65.22  430.22    64.8  470.67   66.82  505.25   64.86
   520.9   63.76  560.37   63.41  583.52   64.57  616.66   64.43  625.74   63.45
  634.13   64.27  678.27   62.82  775.16   62.62  802.04   63.42  864.58   62.08
  892.53    62.4   897.2   59.18  905.64    58.1   913.2   62.69  940.62   63.28
  976.92   70.05 1003.76   70.95 1083.91   75.25 1111.02   77.78 1142.07   78.94
#Mann= 7 ,-1 , 0
       0    .085       0  345.48    .085       0  505.25     .07       0
  625.74     .07       0  892.53     .05       0   913.2     .07       0
 1003.76     .08       0
#XS Ineff= 2 , 0
       0     470      68               0
Permanent Ineff=
       F       F
Bank Sta=892.53,913.2
XS Rating Curve= 0 ,0
Exp/Cntr=0.3,0.1

Type RM Length L Ch R = 1 ,27990   ,542.37,601.76,614.74
XS GIS Cut Line= 4
      2401960.75         601985.2401868.50000003        601681.5
2401819.25000001     601329.0625      2401847.75601024.187500015
#Sta/Elev= 30
       0   67.63   60.15    66.7  100.06   67.13  115.81   68.04  128.25   67.88
  223.58   65.16  250.89   62.92  287.43   64.69  374.54   66.09  385.48   65.33
  432.27   64.71  455.42   63.91  480.21   63.64  491.01    62.5  514.52   63.67
  562.67   64.57     567   64.29  628.27   61.48  635.39   56.87  640.14   57.07
  658.29   61.51   669.6    61.2  729.89   61.35  771.48   62.69  798.66   63.05
   831.9   61.72  843.37   61.31  908.18    62.4  918.17   63.37  979.28   72.29
#Mann= 5 ,-1 , 0
       0    .085       0     567     .07       0  627.31     .05       0
  658.29     .07       0   831.9     .08       0
#XS Ineff= 2 , 0
       0     375    67.5               0
Permanent Ineff=
       F       F
Bank Sta=628.27,658.29
XS Rating Curve= 0 ,0
Exp/Cntr=0.3,0.1

Type RM Length L Ch R = 1 ,27388   ,246.62,201.19,199.5
XS GIS Cut Line= 2
2402259.88664448602069.2541101132402459.29126643601194.499373451
#Sta/Elev= 30
       0   70.68    68.4   68.58  109.01   68.55  190.33   66.56  194.53   67.28
  213.25   66.93  219.32   65.84  246.86   65.04  261.99   63.89  350.37   62.58
  376.13   63.74  398.97   62.97  467.16   62.75  489.71      61   525.3   61.24
  571.33   60.06  600.74   60.66  611.74   60.22  614.95   56.06  620.89   55.77
  624.62   59.72  641.14   61.83  687.08   62.56   714.7   64.49   774.5   64.62
  802.28   68.22  829.87   70.18   848.3   73.35  858.18   75.92  897.19   77.04
#Mann= 5 ,-1 , 0
       0    .045       0  109.01    .085       0  611.74     .05       0
  624.62     .08       0   848.3    .045       0
#XS Ineff= 2 , 0
       0                     750       0      67
Permanent Ineff=
       F       F
Bank Sta=611.74,624.62
XS Rating Curve= 0 ,0
Exp/Cntr=0.5,0.3

Type RM Length L Ch R = 1 ,27187   ,82.78,73.47,65.4
BEGIN DESCRIPTION:
Survey Section
END DESCRIPTION:
XS GIS Cut Line= 6
2402831.40358599602144.6684958932402635.84499475601791.709087312
2402591.32759188 601658.156878652402583.14129998601547.404499993
2402594.87950002601483.3047000022402619.85276365601138.896898478
#Sta/Elev= 30
       0   70.61  128.64   67.07  139.78   64.34  174.07   66.56  198.49   64.97
  207.62   65.94  230.13    63.3  253.31   65.59  278.75   61.74  302.89   63.83
  319.38   61.68  328.24   64.55  371.95   63.68  470.49    63.9  500.92    60.9
  561.83    58.3 655.679   61.47 661.217   57.82  661.28   55.43  669.83   55.72
  673.49   57.65 677.669   59.69 721.754   62.95  819.61   66.57  843.17    70.9
  856.36   73.75  880.16   75.01  906.68   74.32  925.54   76.18  1067.3   79.55
#Mann= 5 ,-1 , 0
       0    .035       0  371.95    .085       0 661.217     .05       0
  673.49     .08       0  843.17    .045       0
#XS Ineff= 2 , 0
       0  651.18   63.78  681.18       0    64.7
Permanent Ineff=
       F       F
Bank Sta=661.217,673.49
XS Rating Curve= 0 ,0
Exp/Cntr=0.5,0.3

Type RM Length L Ch R = 2 ,27145   ,,,
BEGIN DESCRIPTION:
Pridgen Road
END DESCRIPTION:
Bridge Culvert--1,0,-1,-1, 0
Deck Dist Width WeirC Skew NumUp NumDn MinLoCord MaxHiCord MaxSubmerge Is_Ogee
31.6,20.5,2.6,0, 60, 64, , , 0.98, 0, 1,1,,
      22   24.09   33.22   34.96   39.12   52.24   67.49    71.3   72.18   79.48
   81.71   93.96   95.91  102.31  117.64  117.67  117.68  126.67  127.28  134.84
  141.59 484.465  544.77 605.277 666.451 685.292 734.145 851.809  863.22  869.25
  875.58  886.39  898.82  900.42  904.75  909.31  910.96   927.5  934.26  943.02
   946.9  957.82  971.35  972.37  975.34  979.71  981.24  999.63 1004.45 1010.78
 1015.95 1020.51  1026.2 1032.34 1037.16 1043.89 1053.93 1059.77 1065.95 1066.39
   68.17   68.16    67.8   67.82   67.54   67.24   67.18   67.22   67.18   66.87
   66.86   66.88   66.79      67   66.41   66.41   66.41   66.18   66.17   66.07
   66.01   63.79   63.78   63.99   64.55   64.74   65.62   69.38   69.48   69.49
   69.71   70.46   70.59   70.54   70.61   70.74   70.84   71.51    71.7    71.8
   71.92    72.7   72.99   72.99   73.01   73.13   73.27   73.72   73.85   74.13
   73.95    74.1   74.34   74.52   74.95   75.16    75.6   75.68   75.85   75.87
                                                                                
                                                                                
                                                                                
                                                                                
                                                                                
                                                                                
       0    2.09   11.22   12.96   17.12   30.24   45.49    49.3   50.18   57.48
   59.71   71.96   73.91   80.31   95.64   95.67   95.68  104.67  105.28  112.84
  119.59  127.11  141.38  213.27  261.14 462.465  522.77 583.277 644.451 663.292
 712.145 829.809  841.22  847.25  853.58  864.39  876.82  878.42  882.75  887.31
  888.96   905.5  912.26  921.02   924.9  935.82  949.35  950.37  953.34  957.71
  959.24  977.63  982.45  988.78  993.95  998.51  1004.2 1010.34 1015.16 1021.89
 1031.93 1037.77 1043.95 1044.39
   68.17   68.16    67.8   67.82   67.54   67.24   67.18   67.22   67.18   66.87
   66.86   66.88   66.79      67   66.41   66.41   66.41   66.18   66.17   66.07
   66.01   65.88   65.65   64.72   64.16   63.79   63.78   63.99   64.55   64.74
   65.62   69.38   69.48   69.49   69.71   70.46   70.59   70.54   70.61   70.74
   70.84   71.51    71.7    71.8   71.92    72.7   72.99   72.99   73.01   73.13
   73.27   73.72   73.85   74.13   73.95    74.1   74.34   74.52   74.95   75.16
    75.6   75.68   75.85   75.87
                                                                                
                                                                                
                                                                                
                                                                                
                                                                                
                                                                                
                                
BR Coef=-1 , 0 , 0 ,1.25, 0 ,,,0.8,0,2,0,
WSPro=,,,, 1 ,,,, 0 ,,,, 0 ,,,,-1 ,-1 ,-1 , 0 , 0 , 0 , 0 , 0
Multiple Barrel Culv=1,4,,52,0.024,0.9,1,2,3,55.38,56.27, 2,Culvert #1  , 0 ,17.6
 663.177 622.177 669.177 628.177
Culvert Bottom n=0.024
BC Design=,, 0 ,, 0 ,,,,,,
BC Use User HTab Curves=0
BC User HTab FreeFlow(D)= 0

Type RM Length L Ch R = 1 ,27113   ,145.68,219,209.67
BEGIN DESCRIPTION:
Survyed Section
END DESCRIPTION:
XS GIS Cut Line= 6
2402875.03287666602122.652006894  2402686.628868601758.960724384
2402656.81810716601662.3738591972402653.04349999601559.568399996
2402657.51389998601476.8875000182402688.75172023601145.697478309
#Sta/Elev= 30
       0   68.78   14.26   68.92   37.63   67.07   63.96   67.18   98.74   65.35
  138.57   65.19  153.52   63.36  162.28   64.29  193.78   64.46  229.48   63.11
  266.32   63.26  273.74   62.31  295.29   62.06  344.16    62.9  449.12   61.87
  515.32   61.63   609.6   61.13 613.984   57.89 617.098   55.63 628.411   55.07
 637.721   57.76 642.573   61.42 698.353   64.19  795.08   67.73  826.42   70.59
  865.39   70.21  927.22   72.62  947.49   74.61  997.51   75.18 1031.05   77.04
#Mann= 5 ,-1 , 0
       0    .085       0  449.12    .035       0  515.32    .085       0
 613.984     .05       0 637.721    .045       0
#XS Ineff= 2 , 0
       0  610.18   60.27  640.18       0   60.27
Permanent Ineff=
       F       F
Bank Sta=613.984,637.721
XS Rating Curve= 0 ,0
Exp/Cntr=0.5,0.3

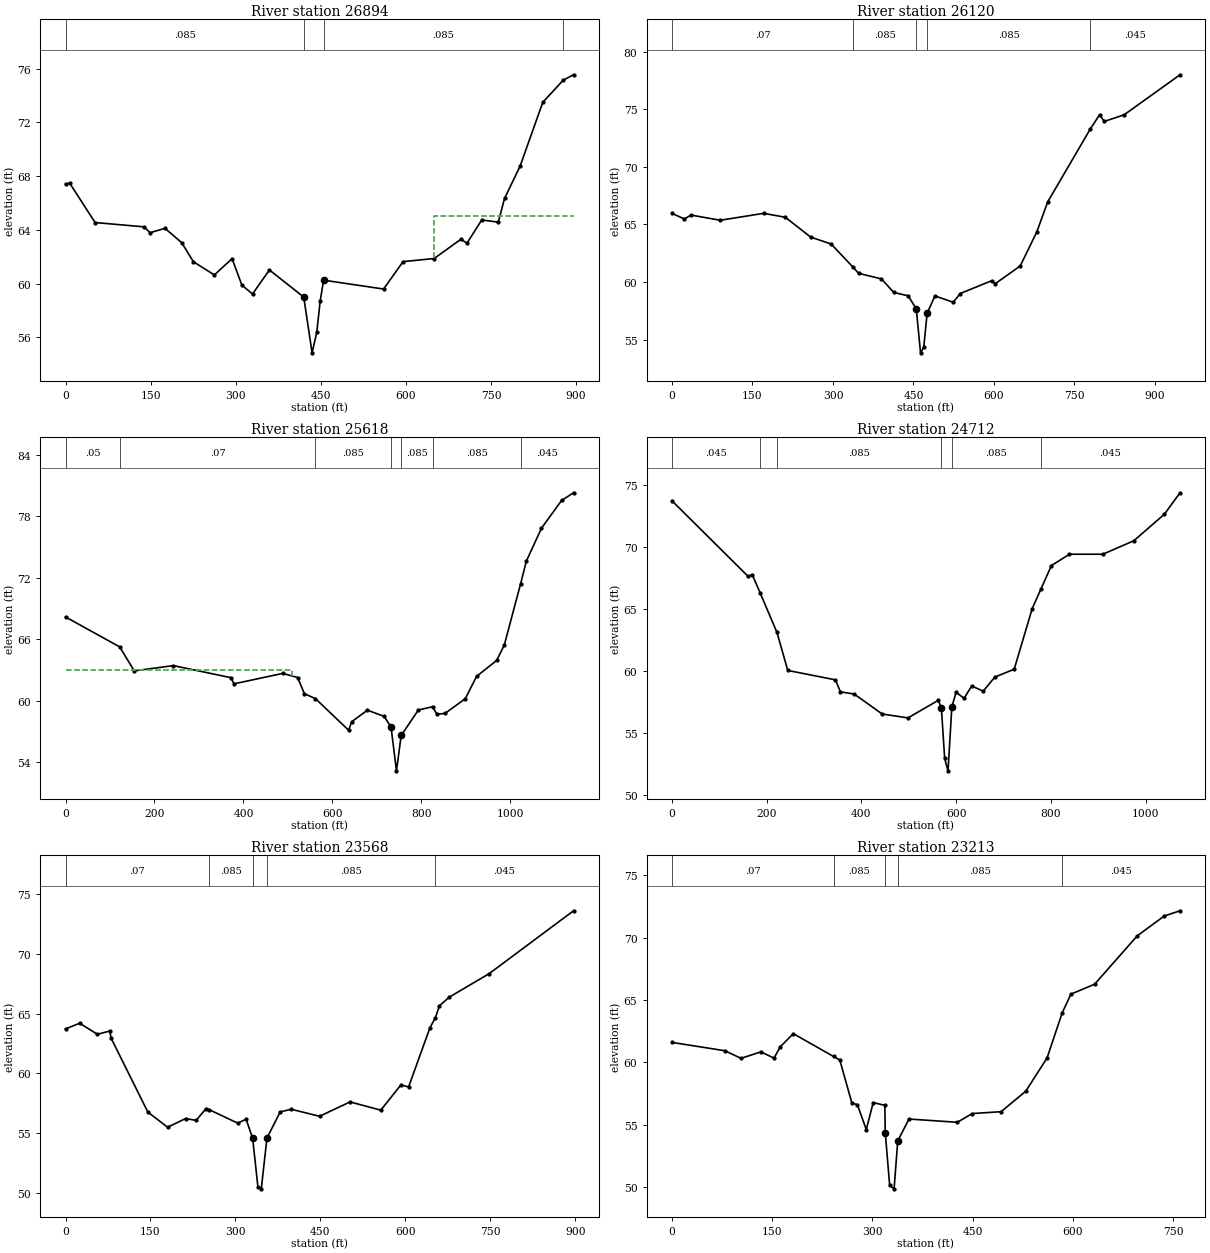
Type RM Length L Ch R = 1 ,26894   ,758.44,774.48,753.16
XS GIS Cut Line= 3
2402863.50802089602078.7527172272402795.02212751601808.233438537
2402949.85302062601209.863887176
#Sta/Elev= 30
       0   67.42     7.4   67.48   52.15   64.55  138.39   64.23  148.96   63.79
  175.33   64.12  204.86   63.05  225.41   61.63  262.37   60.65  293.59   61.86
  310.91   59.89  329.67   59.23   359.4   61.02  419.94      59  434.62   54.85
  442.93   56.39  448.87    58.7  454.92   60.26  560.65    59.6  594.97   61.64
  649.71   61.87  697.07   63.31  707.63   63.01  733.57   64.74  762.78   64.58
  773.91   66.35  801.29   68.75  841.27    73.5  877.39   75.15  895.49   75.55
#Mann= 4 ,-1 , 0
       0    .085       0  419.94     .05       0  454.92    .085       0
  877.39    .045       0
#XS Ineff= 2 , 0
       0                     650       0      65
Permanent Ineff=
       F       F
Bank Sta=419.94,454.92
XS Rating Curve= 0 ,0
Exp/Cntr=0.3,0.1

Type RM Length L Ch R = 1 ,26120   ,392.7,502.34,536.57
XS GIS Cut Line= 2
2403429.83366296602221.4796081782403722.98785119601321.372382373
#Sta/Elev= 30
       0   65.96   23.13   65.47   35.48   65.81   89.92   65.36  170.82   65.96
   211.2   65.62  258.35    63.9  296.51    63.3  337.48   61.28  347.83   60.75
  390.26   60.27  413.33   59.09  440.19    58.8  455.24   57.66  463.18   53.85
  469.12   54.33   475.4   57.27  489.93   58.79  524.16   58.24  537.11      59
  595.65   60.11  602.63   59.86  648.84   61.39  679.63   64.33  700.16   66.96
   778.9   73.24  796.76   74.52  805.44   73.94  842.37   74.51  946.64   77.99
#Mann= 5 ,-1 , 0
       0     .07       0  337.48    .085       0  455.24     .05       0
   475.4    .085       0   778.9    .045       0
Bank Sta=455.24,475.4
XS Rating Curve= 0 ,0
Exp/Cntr=0.3,0.1

Type RM Length L Ch R = 1 ,25618   ,885.2,905.47,886.61
XS GIS Cut Line= 2
2403437.82575417602349.7306472962404356.43882959 601671.37022239
#Sta/Elev= 30
       0   68.18  121.73   65.26  154.43   62.92  242.54   63.43  372.15   62.25
  378.59   61.65  488.22   62.67  521.68   62.27  536.98   60.69  561.83   60.21
  636.42   57.12  642.99   57.94  678.58   59.08  715.96   58.48  731.64   57.45
  743.94   53.16  754.48   56.61  793.17    59.1  825.39   59.42  834.47   58.69
  852.87   58.76  898.55    60.2  924.18   62.39  968.98   63.93  986.24   65.43
 1022.83    71.4 1035.84   73.63 1069.86   76.84 1115.01   79.55 1141.94    80.3
#Mann= 7 ,-1 , 0
       0     .05       0  121.73     .07       0  561.83    .085       0
  731.64     .05       0  754.48    .085       0  825.39    .085       0
 1022.83    .045       0
#XS Ineff= 2 , 0
       0     510      63               0
Permanent Ineff=
       F       F
Bank Sta=731.64,754.48
XS Rating Curve= 0 ,0
Exp/Cntr=0.3,0.1

Type RM Length L Ch R = 1 ,24712   ,1095.85,1143.88,1031.37
XS GIS Cut Line= 2
2404003.75524269603030.7503249352404858.44421399602382.507965073
#Sta/Elev= 30
       0   73.76  161.05   67.64  169.34    67.8  186.65   66.27  221.73   63.11
  244.49   60.04  345.19   59.28  355.61   58.31  384.92   58.13  443.67   56.52
  498.19    56.2  562.17   57.62  568.81   57.03  575.77   52.93   582.9   51.92
  590.96    57.1  599.98   58.28  616.69   57.78  632.83   58.79  657.01   58.36
  681.66    59.5  722.58   60.14  760.71   65.05  779.11   66.63  801.14   68.52
  839.33   69.44  909.85   69.44  975.19   70.53 1039.81   72.68 1072.71   74.41
#Mann= 6 ,-1 , 0
       0    .045       0  186.65     .07       0  221.73    .085       0
  568.81     .05       0  590.96    .085       0  779.11    .045       0
Bank Sta=568.81,590.96
XS Rating Curve= 0 ,0
Exp/Cntr=0.3,0.1

Type RM Length L Ch R = 1 ,23568   ,357.57,355.58,285.16
XS GIS Cut Line= 2
 2405062.5931886603673.0045595472405560.05750018602926.808092117
#Sta/Elev= 30
       0   63.72   24.94   64.19   56.31   63.27   78.21   63.54   80.57   62.94
  145.37   56.78  180.14   55.52  212.08   56.24  230.65   56.09  248.22   57.08
   253.8   56.98  303.98   55.86  318.84   56.19   330.4   54.58  339.67   50.53
  345.61   50.38  355.59   54.61  378.95   56.79  398.23   57.02  448.46   56.43
   502.3   57.63  556.53   56.94  591.93   59.04  605.65   58.88  643.21    63.8
  652.97   64.66  660.17   65.65   677.5   66.37  747.66   68.32  896.82   73.57
#Mann= 5 ,-1 , 0
       0     .07       0   253.8    .085       0   330.4     .05       0
  355.59    .085       0  652.97    .045       0
Bank Sta=330.4,355.59
XS Rating Curve= 0 ,0
Exp/Cntr=0.3,0.1

Type RM Length L Ch R = 1 ,23213   ,352.31,397.01,431.13
XS GIS Cut Line= 2
2405450.76609841603872.7440180182405646.73688781603137.853557676
#Sta/Elev= 30
       0    61.6   79.24   60.93  103.39   60.32   133.1   60.84  152.75   60.34
  162.34   61.26  181.66    62.3  241.86   60.47  251.24   60.19  269.41   56.72
  277.49   56.61  290.89   54.61  301.29   56.77  318.66   56.55   319.3   54.36
  325.89   50.13  332.54   49.85     338    53.7  354.85   55.45  427.28   55.19
  449.37   55.89   492.7   56.04   529.6   57.68  561.53   60.35  584.19   63.97
   597.2   65.47   632.8   66.27  696.36   70.14  736.87   71.74  760.57   72.16
#Mann= 5 ,-1 , 0
       0     .07       0  241.86    .085       0  318.66     .05       0
     338    .085       0  584.19    .045       0
Bank Sta=319.3,338
XS Rating Curve= 0 ,0
Exp/Cntr=0.3,0.1

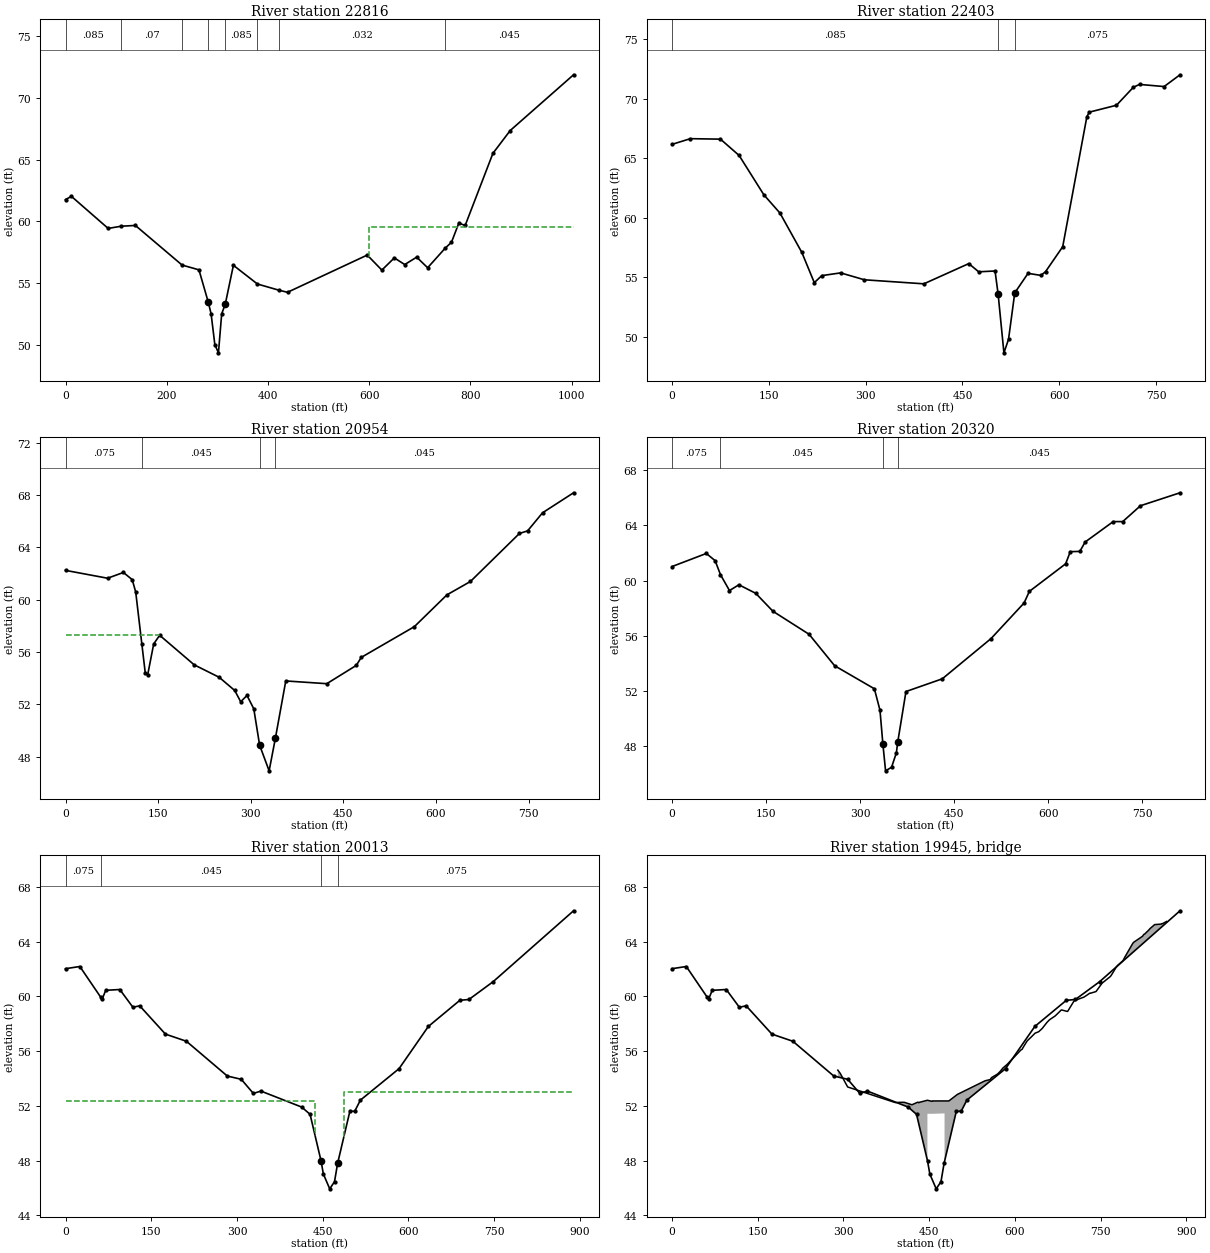
Type RM Length L Ch R = 1 ,22816   ,367.97,412.9,366.32
XS GIS Cut Line= 2
2405680.10172741603943.2443474082406340.73088397603187.649749622
#Sta/Elev= 30
       0   61.76   11.68   62.02   84.27   59.42   110.1    59.6  138.07   59.66
  230.24   56.45  263.63   56.06  282.19   53.42  287.65   52.49  295.01      50
  302.14   49.33  308.53   52.49  315.69   53.29  331.68   56.43  379.19   54.91
  421.64   54.41  438.57   54.24  596.11   57.26  624.96   56.04   649.6   57.03
  670.15   56.49  693.81   57.09  715.41   56.23  749.94   57.81  762.54    58.3
  777.04   59.85  789.57   59.66  844.39   65.51  878.57   67.36 1003.67   71.88
#Mann= 8 ,-1 , 0
       0    .085       0   110.1     .07       0  230.24    .085       0
  282.19     .05       0  315.69    .085       0  379.19    .045       0
  421.64    .032       0  749.94    .045       0
#XS Ineff= 2 , 0
       0                     600       0    59.5
Permanent Ineff=
       F       F
Bank Sta=282.19,315.69
XS Rating Curve= 0 ,0
Exp/Cntr=0.3,0.1

Type RM Length L Ch R = 1 ,22403   ,1435.87,1448.58,1372.31
XS GIS Cut Line= 2
 2405918.0810578604257.1482588052406400.47069328603635.317869291
#Sta/Elev= 30
       0   66.17   28.47   66.65   75.13   66.61     104   65.24  142.37   61.93
  167.25    60.4  201.16   57.09  220.48   54.55  232.08   55.14  261.28   55.37
  298.05   54.79  390.18   54.45  459.79   56.15  475.16   55.46  500.47   55.53
  505.21    53.6  514.22   48.65  521.37   49.79  530.98   53.69  551.58   55.33
  571.45   55.16  578.65   55.47  605.29   57.57  642.72    68.5  646.56   68.88
  688.59   69.46  714.71   70.97  724.26   71.21  762.36   71.03     787   72.02
#Mann= 3 ,-1 , 0
       0    .085       0  505.21     .05       0  530.98    .075       0
Bank Sta=505.21,530.98
XS Rating Curve= 0 ,0
Exp/Cntr=0.3,0.1

Type RM Length L Ch R = 1 ,20954   ,643.43,633.77,619.16
XS GIS Cut Line= 2
2407364.70607662604822.7069120852407533.99229802604017.565127537
#Sta/Elev= 30
       0   62.23   68.13   61.63   93.77   62.07  108.06   61.52  113.71   60.57
  123.58   56.62  129.11   54.41  133.09   54.25  142.83   56.61  152.51   57.27
  208.44   55.01  248.87   54.06  274.06   53.05  283.73   52.19  293.93   52.67
  304.91   51.65  314.37   48.87  329.75   46.91  339.88    49.4  356.72   53.78
  423.14   53.57  470.96   54.97  478.97   55.58  564.97   57.93  617.73   60.36
  655.73   61.38  735.09   65.05  748.37   65.25  772.53   66.63  822.75   68.16
#Mann= 4 ,-1 , 0
       0    .075       0  123.58    .045       0  314.37     .05       0
  339.88    .045       0
#XS Ineff= 2 , 0
       0  152.51    57.3               0
Permanent Ineff=
       F       F
Bank Sta=314.37,339.88
XS Rating Curve= 0 ,0
Exp/Cntr=0.3,0.1

Type RM Length L Ch R = 1 ,20320   ,244.38,307.36,318.35
XS GIS Cut Line= 2
 2408027.8019172604864.6771308482408100.77646089604058.116384491
#Sta/Elev= 30
       0   61.01   54.72   61.96   68.78   61.44   77.34   60.42    91.7   59.27
  106.67   59.69  133.53   59.07  160.93   57.77  218.58    56.1  259.28   53.82
  322.64   52.15   331.6   50.59  336.17   48.16   340.5    46.2  350.06   46.46
  357.74   47.51  359.79   48.26  373.01   51.95  430.85   52.87  508.63   55.79
  561.29   58.37   569.7   59.21  627.53   61.21  634.97   62.09  650.17   62.11
  658.64   62.79  703.36   64.27  718.57   64.27  746.81   65.42  809.86   66.36
#Mann= 4 ,-1 , 0
       0    .075       0   77.34    .045       0  336.17     .05       0
  359.79    .045       0
Bank Sta=336.17,359.79
XS Rating Curve= 0 ,0
Exp/Cntr=0.5,0.3

Type RM Length L Ch R = 1 ,20013   ,102.15,102.56,92.44
XS GIS Cut Line= 2
2408133.45297331604863.7056872252408561.21822625604084.330358893
#Sta/Elev= 30
       0   62.02    25.1   62.18   61.26   59.96   64.48   59.83   70.38   60.44
   95.01    60.5  117.98    59.2  129.79   59.31  174.93   57.24  211.55   56.72
  283.11   54.18  307.56   53.94   328.7   52.91  341.98   53.08  413.46   51.91
     428   51.38  447.19   47.98  451.26   47.02  462.37   45.94  470.73   46.46
  476.17    47.8  497.59    51.6  506.15   51.61  516.06   52.42  583.73   54.72
  634.94    57.8  690.08   59.71  705.96   59.77  748.32   61.07  889.05   66.25
#Mann= 4 ,-1 , 0
       0    .075       0   61.26    .045       0  447.19     .05       0
  476.17    .075       0
#XS Ineff= 2 , 0
       0     437   52.36     487       0      53
Permanent Ineff=
       F       F
Bank Sta=447.19,476.17
XS Rating Curve= 0 ,0
Exp/Cntr=0.5,0.3

Type RM Length L Ch R = 3 ,19945   ,,,
BEGIN DESCRIPTION:
Unnamed Adcess Rd.
END DESCRIPTION:
Bridge Culvert--1,0,-1,-1, 0
Deck Dist Width WeirC Skew NumUp NumDn MinLoCord MaxHiCord MaxSubmerge Is_Ogee
50,12,2.6,0, 73, 102, , , 0.98, 0, 0,0,,
  290.22  294.37  307.46  387.92   391.1  399.38  406.56  420.01  423.05  430.06
   432.1  432.98  447.04  455.27  455.98     477  484.51  499.57  547.74  556.76
  559.37  569.58  573.99  579.04  586.58  590.87  599.25  610.55   612.9  614.22
  621.48   629.2  635.41   641.9  648.03  656.29  660.71  670.65  676.55  681.39
  691.59   692.2   692.5  693.16  703.25  711.45  720.81  728.76  729.92   730.7
   731.4  732.54  742.08  753.12  753.75  767.21  769.23  777.38  779.99  789.33
  792.41  806.39     808  823.48  825.65  827.16  833.89  836.59   844.6  856.45
  857.08  858.39  865.57
   54.61   54.38   53.38   52.28   52.24   52.26   52.26   52.08   52.14   52.27
   52.23   52.26   52.41   52.33   52.36   52.36   52.36   52.84   53.83   53.92
   54.07   54.32    54.5   54.76   55.03   55.22   55.58   56.08   56.14   56.25
   56.74   57.05   57.31   57.42   57.66    58.1   58.29   58.57   58.81   59.01
    58.9    58.9   58.91   58.95   59.64    59.8   59.94   60.16    60.2   60.21
   60.24   60.23   60.35   60.99      61   61.45   61.57   62.13   62.26   62.61
   62.86   63.87   63.95   64.39   64.52   64.55   64.82   64.95   65.24   65.28
   65.31   65.31   65.47
                                                                                
                   51.42   51.42   51.42   51.45
                                                                                
                                                                                
                                                                                
                                                                                
                                                                                
                        
      30   34.67   55.44   76.17   79.61   81.42   88.69   106.9  107.61  109.16
  110.11  116.37  124.66  136.15  138.24  144.15  146.11  149.97  158.59     163
  170.48  180.59  185.21  191.24  198.57  201.88  215.32   220.4  225.62  229.23
  236.68  327.46  407.92   411.1  419.38  426.56  440.01  443.05  450.06   452.1
  452.98  467.04  475.27  475.98     497  504.51  519.57  567.74  576.76  579.37
  589.58  593.99  599.04  606.58  610.87  619.25  630.55   632.9  634.22  641.48
   649.2  655.41   661.9  668.03  676.29  680.71  690.65  696.55  701.39  711.59
   712.2   712.5  713.16  723.25  731.45  740.81  748.76  749.92   750.7   751.4
  752.54  762.08  773.12  773.75  787.21  789.23  797.38  799.99  809.33  812.41
  826.39     828  843.48  845.65  847.16  853.89  856.59   864.6  876.45  877.08
  878.39  885.57
   62.68   62.85   62.44   62.34   62.32   62.34   62.73   62.51   62.49   62.42
    62.4   62.08   61.25   60.82   60.98    60.8   60.55   60.43   59.96   59.51
   59.35   58.58   58.46      58   57.71   57.77    57.3   57.27   57.09   56.78
   56.78   53.38   52.28   52.24   52.26   52.26   52.08   52.14   52.27   52.23
   52.26   52.41   52.33   52.36   52.36   52.36   52.84   53.83   53.92   54.07
   54.32    54.5   54.76   55.03   55.22   55.58   56.08   56.14   56.25   56.74
   57.05   57.31   57.42   57.66    58.1   58.29   58.57   58.81   59.01    58.9
    58.9   58.91   58.95   59.64    59.8   59.94   60.16    60.2   60.21   60.24
   60.23   60.35   60.99      61   61.45   61.57   62.13   62.26   62.61   62.86
   63.87   63.95   64.39   64.52   64.55   64.82   64.95   65.24   65.28   65.31
   65.31   65.47
                                                                                
                                                                                
                                                                                
                                                                                
           51.42   51.42   51.42   51.45
                                                                                
                                                                                
                                                                                
                                                                                
                                                                                
                
BR Coef=-1 , 1 , 0 ,1.25, 0 ,,,0.8,0,2,0,
WSPro=,,,, 1 ,,,, 0 ,,,, 0 ,,,,-1 ,-1 ,-1 , 0 , 0 , 0 , 0 , 0
BC Design=,, 0 ,, 0 ,,,,,,
BC Use User HTab Curves=0
BC User HTab FreeFlow(D)= 0

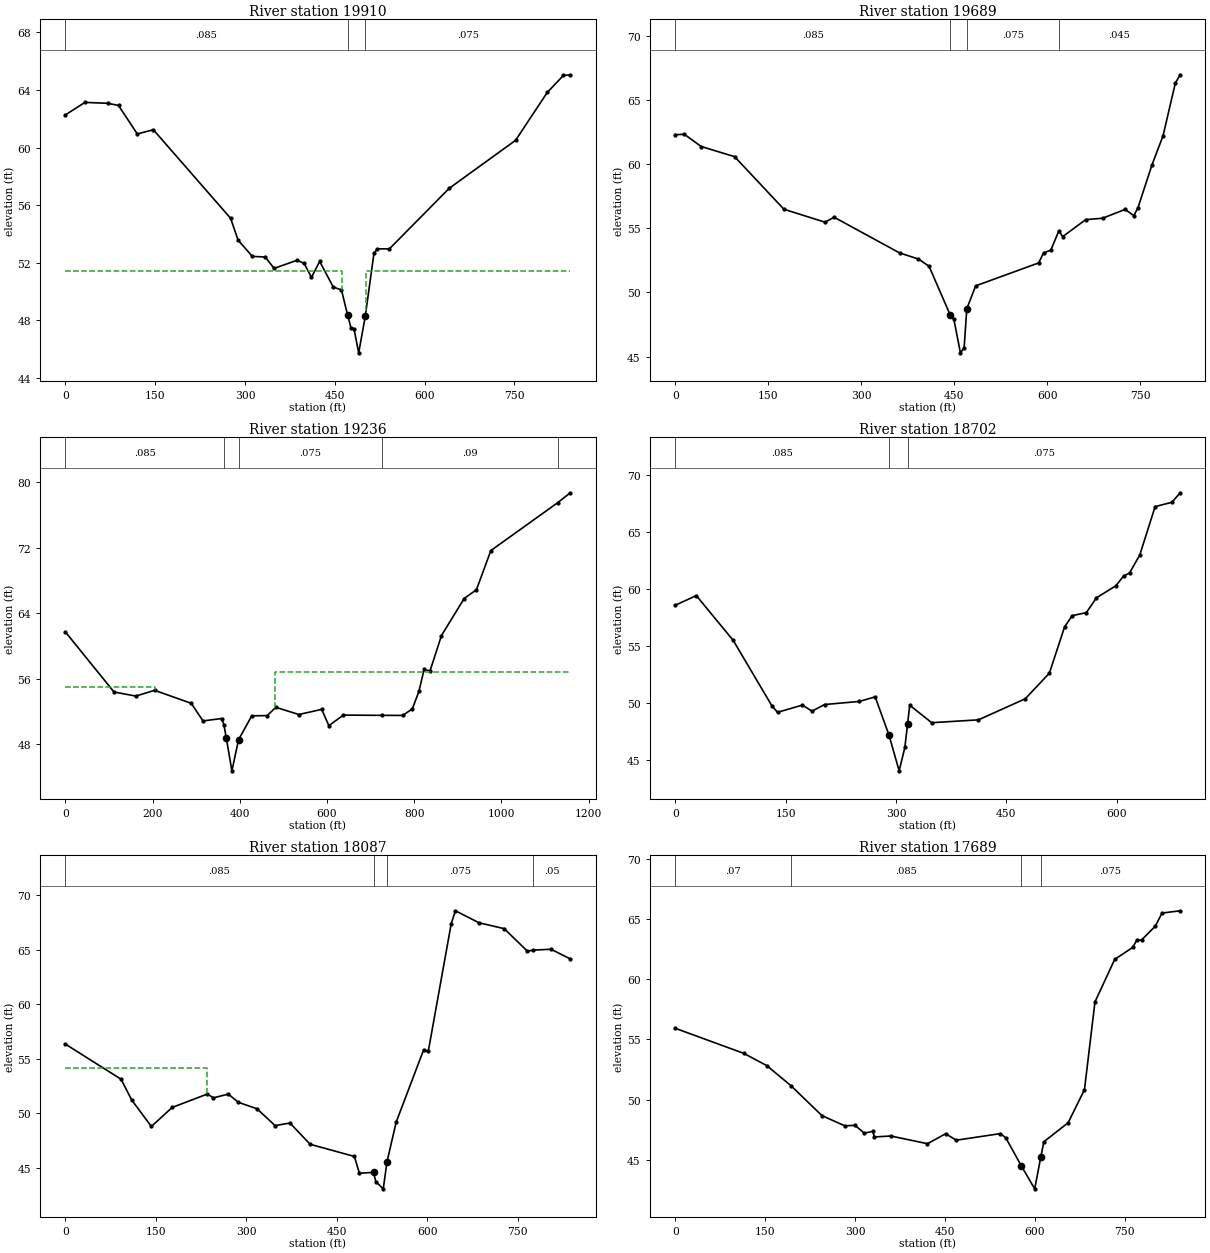
Type RM Length L Ch R = 1 ,19910   ,264.05,221.43,215.49
XS GIS Cut Line= 2
 2408219.3300885604878.2885936052408622.79049754604137.801015526
#Sta/Elev= 30
       0   62.27   32.63   63.14   70.61   63.08    88.8   62.93  120.08   60.95
  146.97   61.24  275.93   55.09  288.46   53.57  312.25   52.44  333.72    52.4
   348.6   51.61  386.86   52.17  398.71   51.96  410.98   50.98  424.68   52.09
  447.44   50.31   461.1   50.11  471.17   48.39  476.86    47.5  482.01   47.41
  489.84   45.74  500.79   48.27  515.38   52.67  521.21   52.97  541.01   52.96
     641   57.17  751.92   60.51  804.73   63.83  831.61   65.01  843.27   65.06
#Mann= 3 , 0 , 0
       0    .085       0  471.17     .05       0  500.79    .075       0
#XS Ineff= 2 , 0
       0     462   51.42     502       0   51.42
Permanent Ineff=
       F       F
Bank Sta=471.17,500.79
XS Rating Curve= 0 ,0
Exp/Cntr=0.5,0.3

Type RM Length L Ch R = 1 ,19689   ,399.44,452.7,527.9
XS GIS Cut Line= 2
2408592.65896751 604920.148708062408728.47155961604117.186907157
#Sta/Elev= 30
       0   62.29   14.82   62.32   41.96   61.37   95.77   60.58  175.34   56.48
  241.73   55.47  256.25   55.86  361.75   53.08  392.24    52.6  409.37   52.04
  443.62   48.23  449.45    47.9  459.98   45.29  465.95   45.68   470.3   48.73
  484.58   50.51  586.28    52.3  593.97   53.08  605.73   53.29  618.67   54.79
  625.07   54.35  661.95   55.67  689.34   55.78  725.55   56.47  739.64   55.98
  746.24   56.59  768.86   59.93  786.72    62.2  806.57   66.31  814.37   66.96
#Mann= 4 ,-1 , 0
       0    .085       0  443.62     .05       0   470.3    .075       0
  618.67    .045       0
Bank Sta=443.62,470.3
XS Rating Curve= 0 ,0
Exp/Cntr=0.3,0.1

Type RM Length L Ch R = 1 ,19236   ,479.6,533.9,675.32
XS GIS Cut Line= 3
2408857.64289917604916.6653385912409181.43625712604446.974079296
2409515.87976764603963.889008552
#Sta/Elev= 30
       0   61.72  111.52   54.39  161.43   53.89  204.73   54.59  288.58   53.01
  315.64   50.86  358.16   51.15  363.56   50.41  369.12   48.77  381.95   44.77
  397.21   48.57  427.48   51.48  463.02   51.51  482.52   52.52  535.54   51.64
  587.84   52.27  604.28   50.28  637.56   51.57  726.44   51.54   773.9   51.53
  795.84   52.34     811   54.49  822.72   57.14  836.22   56.95  862.49   61.27
   914.5   65.79  942.71   66.86   975.8   71.64 1129.32   77.49 1158.04   78.69
#Mann= 5 ,-1 , 0
       0    .085       0  363.56     .05       0  397.21    .075       0
  726.44     .09       0 1129.32    .045       0
#XS Ineff= 2 , 0
       0     205      55  480.29       0   56.79
Permanent Ineff=
       F       F
Bank Sta=369.12,397.21
XS Rating Curve= 0 ,0
Exp/Cntr=0.3,0.1

Type RM Length L Ch R = 1 ,18702   ,554.8,615.19,582.18
XS GIS Cut Line= 2
2409082.34188363605086.9585746822409751.22890466604934.188082233
#Sta/Elev= 30
       0   58.57   28.68   59.42   78.93   55.49  131.16    49.8   139.1   49.21
  172.84   49.84  185.94   49.31  202.94   49.89  250.15   50.16  271.71   50.56
  290.57    47.2  304.28   44.09  312.06   46.14  315.68   48.16  318.65   49.83
  348.51    48.3  412.03   48.55  475.58   50.39   508.4   52.63  529.13   56.69
  539.39   57.66  558.67   57.93   572.3   59.22  598.82   60.28  609.24   61.13
  617.29   61.39  631.22   62.97  652.07    67.2  674.93   67.58  686.11   68.41
#Mann= 3 ,-1 , 0
       0    .085       0  290.57     .05       0  315.68    .075       0
Bank Sta=290.57,315.68
XS Rating Curve= 0 ,0
Exp/Cntr=0.3,0.1

Type RM Length L Ch R = 1 ,18087   ,547.77,397.95,335.13
XS GIS Cut Line= 2
2409060.72517282605632.249430686  2409888.845349605511.673312232
#Sta/Elev= 30
       0   56.36   92.25   53.14   109.9   51.24  142.52    48.8   177.1   50.55
  235.46   51.78  245.35   51.43   270.1   51.77  286.65   51.02  317.76   50.42
  347.64   48.88  372.24   49.12   405.6   47.17  479.03   46.05  487.31   44.51
  510.72   44.59  514.52   43.73  526.85   43.08  532.96   45.54  548.23    49.2
  593.95   55.86   601.4   55.68  639.52   67.42  646.41   68.59  685.49   67.49
  727.31   66.95  765.78   64.88  775.01   64.98  804.91   65.06  836.85   64.17
#Mann= 4 ,-1 , 0
       0    .085       0  510.72     .05       0  532.96    .075       0
  775.01     .05       0
#XS Ineff= 2 , 0
       0  234.17   54.18               0
Permanent Ineff=
       F       F
Bank Sta=510.72,532.96
XS Rating Curve= 0 ,0
Exp/Cntr=0.3,0.1

Type RM Length L Ch R = 1 ,17689   ,386.28,254.55,237.33
XS GIS Cut Line= 3
2409330.07781738606292.6067854022409623.89825925 606083.38984862
2409862.71007483605665.009086683
#Sta/Elev= 30
       0   55.92  114.19   53.84  152.74   52.82  193.09   51.15  244.66   48.67
  283.05   47.81  299.82   47.86  315.45   47.21   329.5   47.35  332.39   46.89
  359.52   46.97   420.9   46.33  451.27   47.16  468.79   46.62   542.7   47.17
  551.74    46.8   577.3    44.5  599.74   42.58  610.01   45.24  614.99   46.49
  655.52   48.07  682.79   50.82   700.3   58.11  733.23   61.64  763.02   62.63
  770.17   63.24  778.01   63.25  800.91    64.4  812.16   65.49  842.44   65.68
#Mann= 4 ,-1 , 0
       0     .07       0  193.09    .085       0   577.3     .05       0
  610.01    .075       0
Bank Sta=577.3,610.01
XS Rating Curve= 0 ,0
Exp/Cntr=0.3,0.1