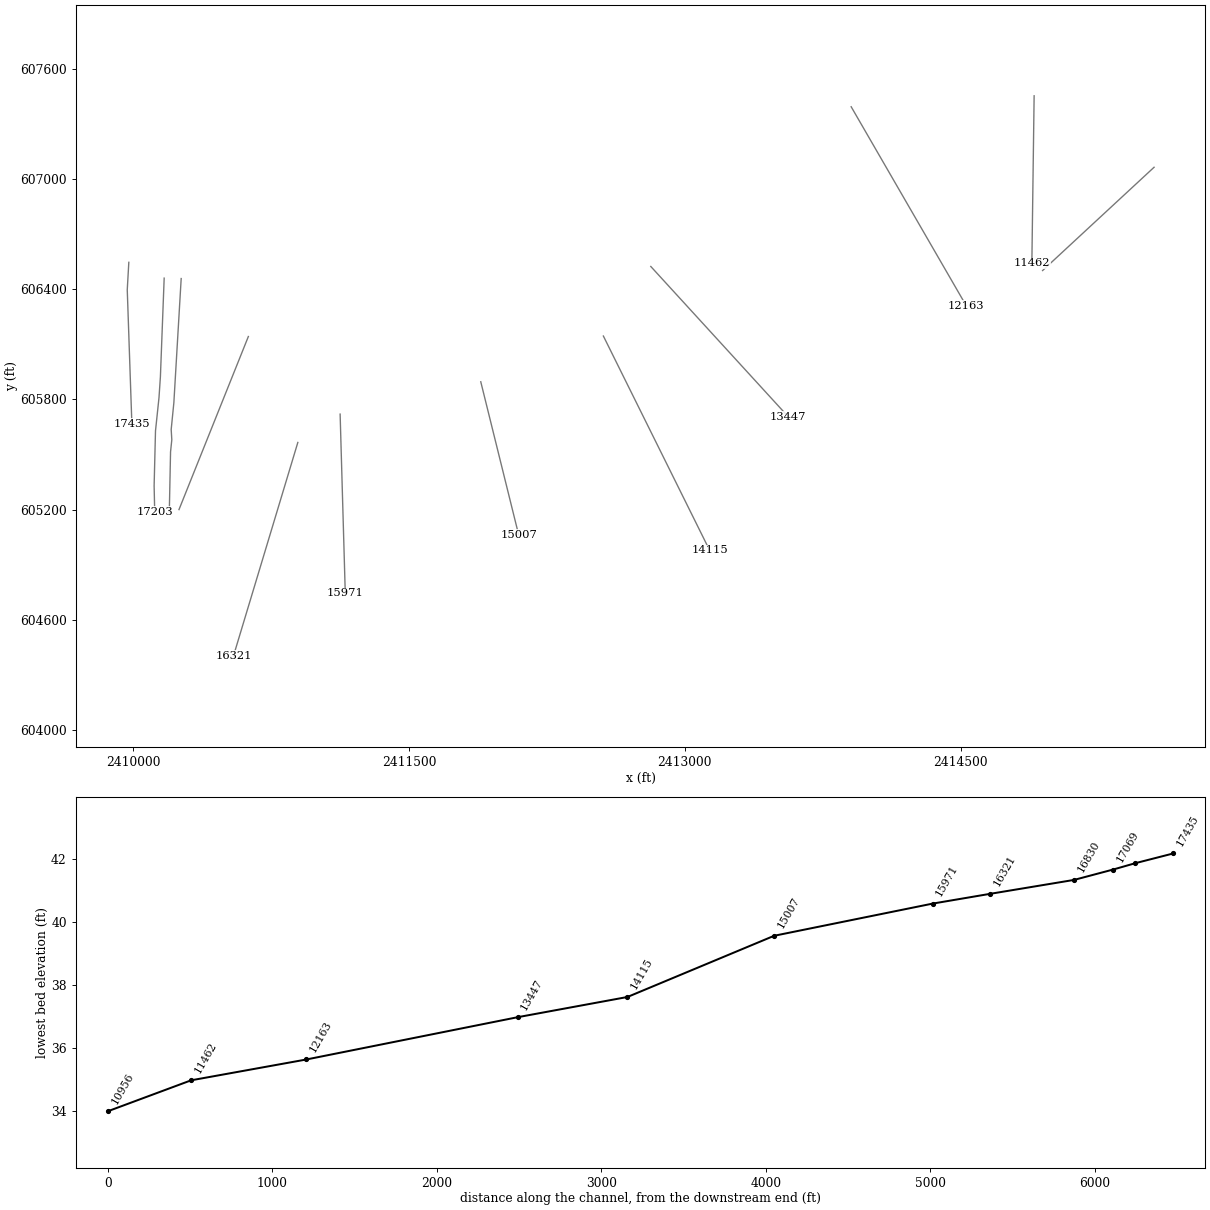
HEC-RAS study DTL_Rainbow_Creek.prj: DTL_Rainbow_Creek

--- DTL_Rainbow_Creek.g01 (geometry) --- (continued)

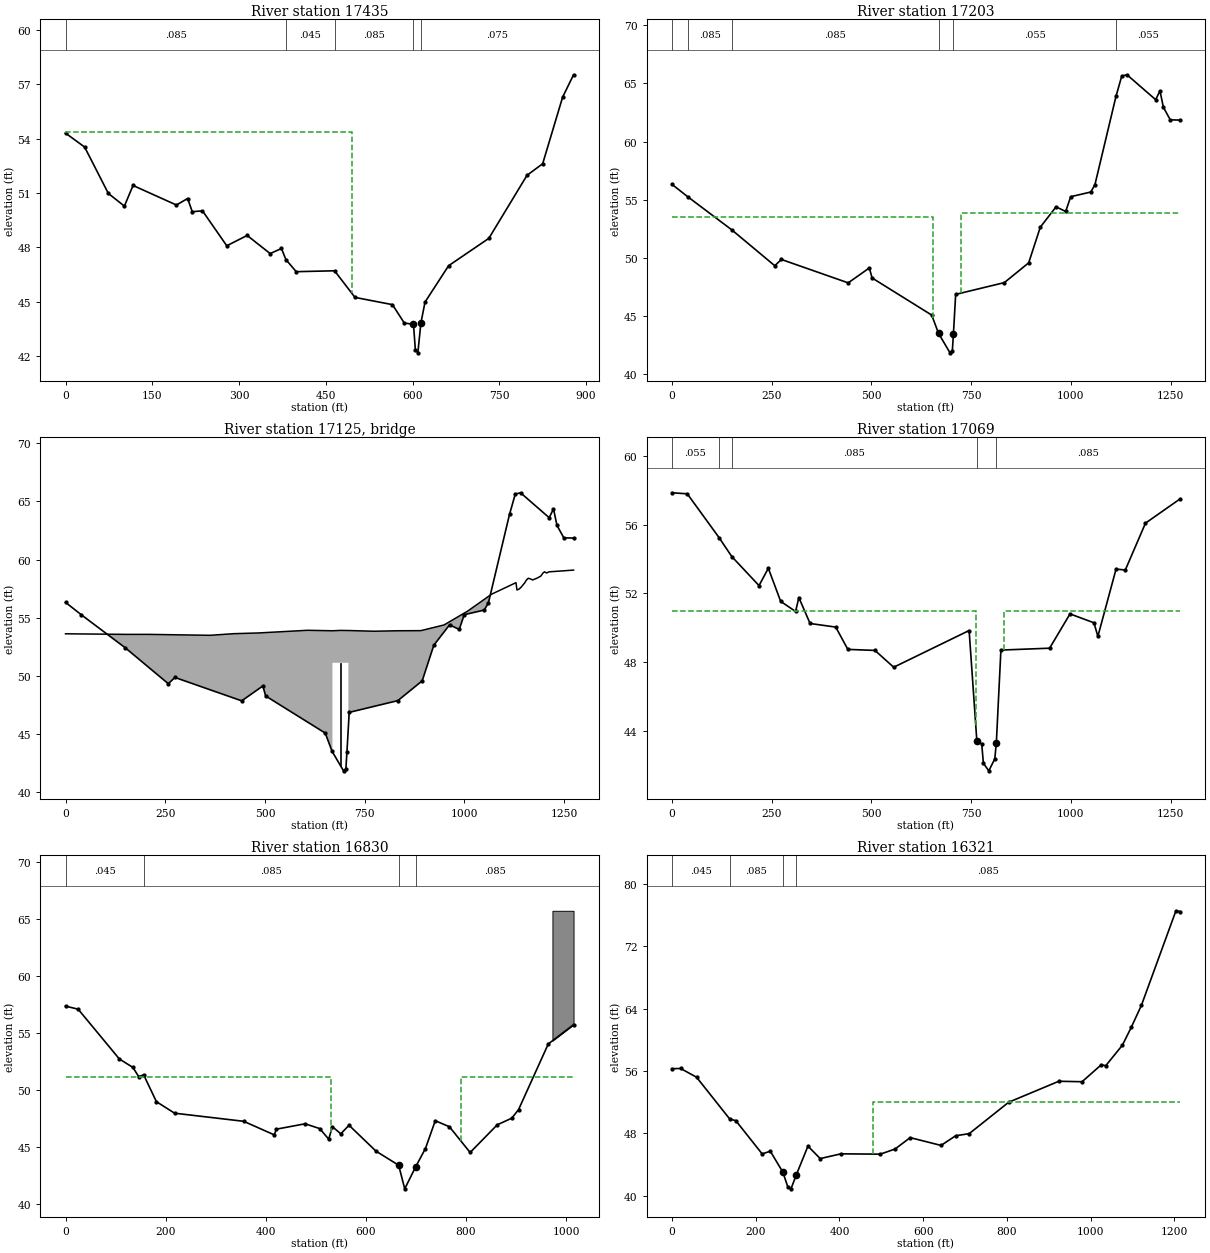
Type RM Length L Ch R = 1 ,17435   ,419.17,231.94,192.41
XS GIS Cut Line= 3
2409975.62231524606546.5376734582409967.13026378606396.777840853
2409992.15234438605668.961669162
#Sta/Elev= 30
       0    54.3   33.08   53.53   74.04   50.97   101.8   50.27  116.73   51.41
  191.75   50.33  211.12   50.69  219.12   49.96  236.79   50.01  278.76   48.08
     314   48.65  353.79   47.65  373.34   47.93  380.95   47.32  398.82   46.65
  465.12    46.7  500.43   45.23  565.19   44.83  585.57   43.82  601.57   43.74
  604.76   42.35  609.11   42.17  614.28    43.8  621.46   44.97  662.25   46.98
  731.82   48.49   797.8   51.97  824.88   52.61  859.31   56.28  878.25   57.52
#Mann= 5 ,-1 , 0
       0    .085       0  380.95    .045       0  465.12    .085       0
  601.57     .05       0  614.28    .075       0
#XS Ineff= 2 , 0
       0  494.62   54.37               0
Permanent Ineff=
       F       F
Bank Sta=601.57,614.28
XS Rating Curve= 0 ,0
Exp/Cntr=0.5,0.3

Type RM Length L Ch R = 1 ,17203   ,120.97,134.08,123.8
BEGIN DESCRIPTION:
Survyed Section
END DESCRIPTION:
XS GIS Cut Line= 6
  2410167.929527606460.3882603352410147.40340002605923.287799999
2410139.73230003605809.7668000012410120.75940001605629.336800009
2410113.28228657605330.1455883092410116.37022449605189.335620135
#Sta/Elev= 30
       0   56.33   39.73   55.26     150   52.42  257.72   49.34  274.22   49.88
  441.68   47.87  494.71   49.15  501.65   48.29 651.098    45.1 668.069   43.54
 696.914   41.86 702.772   42.03 705.471   43.49 711.095   46.88 833.044   47.89
 894.115   49.59  923.22   52.65  962.72    54.4  986.85      54  999.47   55.27
 1049.72   55.67 1060.09   56.29  1112.9   63.88 1127.38   65.63 1140.55   65.74
 1212.44    63.6 1223.17   64.36 1231.84   62.94  1249.1   61.87 1273.44   61.85
#Mann= 6 ,-1 , 0
       0     .05       0   39.73    .085       0     150    .085       0
 668.069     .05       0 705.471    .055       0  1112.9    .055       0
#XS Ineff= 2 , 0
       0  654.09    53.5  724.09       0   53.85
Permanent Ineff=
       F       F
Bank Sta=668.069,705.471
XS Rating Curve= 0 ,0
Exp/Cntr=0.5,0.3

Type RM Length L Ch R = 3 ,17125   ,,,
BEGIN DESCRIPTION:
RT 58
END DESCRIPTION:
Bridge Culvert--1,0,-1,-1, 0
Deck Dist Width WeirC Skew NumUp NumDn MinLoCord MaxHiCord MaxSubmerge Is_Ogee
55.5,42,2.6,0, 35, 30, , , 0.98, 0, 1,1,,
       0     150  209.39 362.549 421.932  482.71 606.259 669.082  669.09 689.219
  709.09 711.065 772.593 832.228 890.692 948.9141008.0881067.9811129.123 1131.68
 1137.27 1141.98 1150.92  1154.7 1159.89 1167.16 1170.53 1177.81  1181.4 1191.23
 1197.11 1200.81 1206.04 1211.85 1273.44
   53.63   53.58   53.58    53.5   53.64    53.7   53.93   53.89   53.89   53.92
   53.91   53.91   53.85   53.89    53.9   54.39   55.58   57.03   58.02   57.39
   57.48   57.63      58   58.22    58.4   58.32   58.25   58.35    58.4   58.58
   58.86   58.95   58.85   58.95    59.1
                                                                   51.14   51.14
   51.14
                                                                                
                                        
       0     150   257.5  316.89 470.049 529.432  590.21 713.759 776.582  776.59
 796.719  816.59 818.565 880.093 939.728 998.1921056.4141115.5881175.4811236.623
 1267.39 1274.66 1278.03 1285.31  1288.9 1298.73 1304.61 1308.31 1313.54 1319.35
   54.15   54.15   53.58   53.58    53.5   53.64    53.7   53.93   53.89   53.89
   53.92   53.91   53.91   53.85   53.89    53.9   54.39   55.58   57.03   58.02
    58.4   58.32   58.25   58.35    58.4   58.58   58.86   58.95   58.85   58.95
                                                                           51.14
   51.14   51.14
                                                                                
Pier Skew, UpSta & Num, DnSta & Num=  ,689.22, 2 ,796.72, 2 , 0 , 0 , 0 ,,
       1       1
      30   51.17
       1       1
      30   51.25
BR Coef=-1 , 1 , 0 ,1.25, 0 ,,,0.8,0,2,0,
WSPro=,,,, 1 ,,,, 0 ,,,, 0 ,,,,-1 ,-1 ,-1 , 0 , 0 , 0 , 0 , 0
BC Design=,, 0 ,, 0 ,,,,,,
BC Use User HTab Curves=0
BC User HTab FreeFlow(D)= 0

Type RM Length L Ch R = 1 ,17069   ,234.94,238.43,249.66
BEGIN DESCRIPTION:
Survyed Section
END DESCRIPTION:
XS GIS Cut Line= 6
2410260.45401286606458.120540351    2410220.5971605782.293100014
2410206.09010002605636.659300014    2410209.4505605580.657700017
2410202.61889999605514.9722999932410195.86747016605188.500733241
#Sta/Elev= 30
       0   57.87   38.37   57.81  117.92   55.26     150   54.15  218.21   52.46
  241.51   53.47  272.48   51.54  309.84   50.95  318.05   51.76  346.22   50.25
   410.5   50.04  440.84   48.74  508.79   48.68  555.75    47.7 744.843   49.84
 764.253   43.39 776.425   43.23  780.61    42.1  794.18   41.66 809.198   42.36
   813.1   43.31 824.496    48.7 946.589   48.81  997.73   50.81 1057.71   50.29
 1067.56    49.5 1113.15   53.42 1136.36   53.37  1186.9    56.1 1273.45   57.51
#Mann= 5 ,-1 , 0
       0    .055       0  117.92    .085       0     150    .085       0
 764.253     .05       0   813.1    .085       0
#XS Ineff= 2 , 0
       0  761.59      51  831.59       0      51
Permanent Ineff=
       F       F
Bank Sta=764.253,813.1
XS Rating Curve= 0 ,0
Exp/Cntr=0.5,0.3

Type RM Length L Ch R = 1 ,16830   ,485,509.26,513.78
XS GIS Cut Line= 2
2410625.87616551606142.5896740562410248.51236367605200.481423974
#Sta/Elev= 30
       0   57.37   25.24    57.1  107.58   52.73   134.6   51.99  146.37   51.17
  156.09   51.34  181.61   48.98  217.91   47.97  355.84   47.26  416.89   46.07
  421.48   46.57  478.65   47.04   507.8   46.62  525.78   45.69  533.14   46.79
  549.85   46.16   566.4   46.91  620.21   44.64  665.56    43.4  677.64   41.33
  699.76   43.29  719.02   44.87  738.65   47.31  766.95   46.78   808.3   44.52
  862.43   46.95  891.33   47.53  904.97   48.28  964.42   54.05 1014.88   55.74
#Mann= 4 ,-1 , 0
       0    .045       0  156.09    .085       0  665.56     .05       0
  699.76    .085       0
#XS Ineff= 2 , 0
       0     530   51.18     790       0   51.18
Permanent Ineff=
       F       F
#Block Obstruct= 1 ,-1
  972.69 1014.88  65.739
Bank Sta=665.56,699.76
XS Rating Curve= 0 ,0
Exp/Cntr=0.3,0.1

Type RM Length L Ch R = 1 ,16321   ,312.13,350.02,378.92
XS GIS Cut Line= 2
2410894.94313195605565.9147131892410544.93510592604404.075712442
#Sta/Elev= 30
       0    56.3   20.59   56.33   58.73   55.21  138.21   49.83  152.41   49.64
   215.4   45.37   234.9   45.72  264.92   43.02  276.74   41.13  284.28   40.89
  296.92   42.68  324.79   46.37  354.08   44.77  403.43   45.38  497.57   45.34
  532.94      46  568.91   47.46  642.68   46.46  677.56    47.7  709.94   47.97
  804.22      52  923.99   54.69   979.5   54.63 1025.24    56.8 1036.12   56.69
 1075.69   59.31 1097.37   61.65 1121.37   64.45 1203.65   76.56 1213.42   76.46
#Mann= 4 ,-1 , 0
       0    .045       0  138.21    .085       0  264.92     .05       0
  296.92    .085       0
#XS Ineff= 2 , 0
       0                     480       0      52
Permanent Ineff=
       F       F
Bank Sta=264.92,296.92
XS Rating Curve= 0 ,0
Exp/Cntr=0.3,0.1

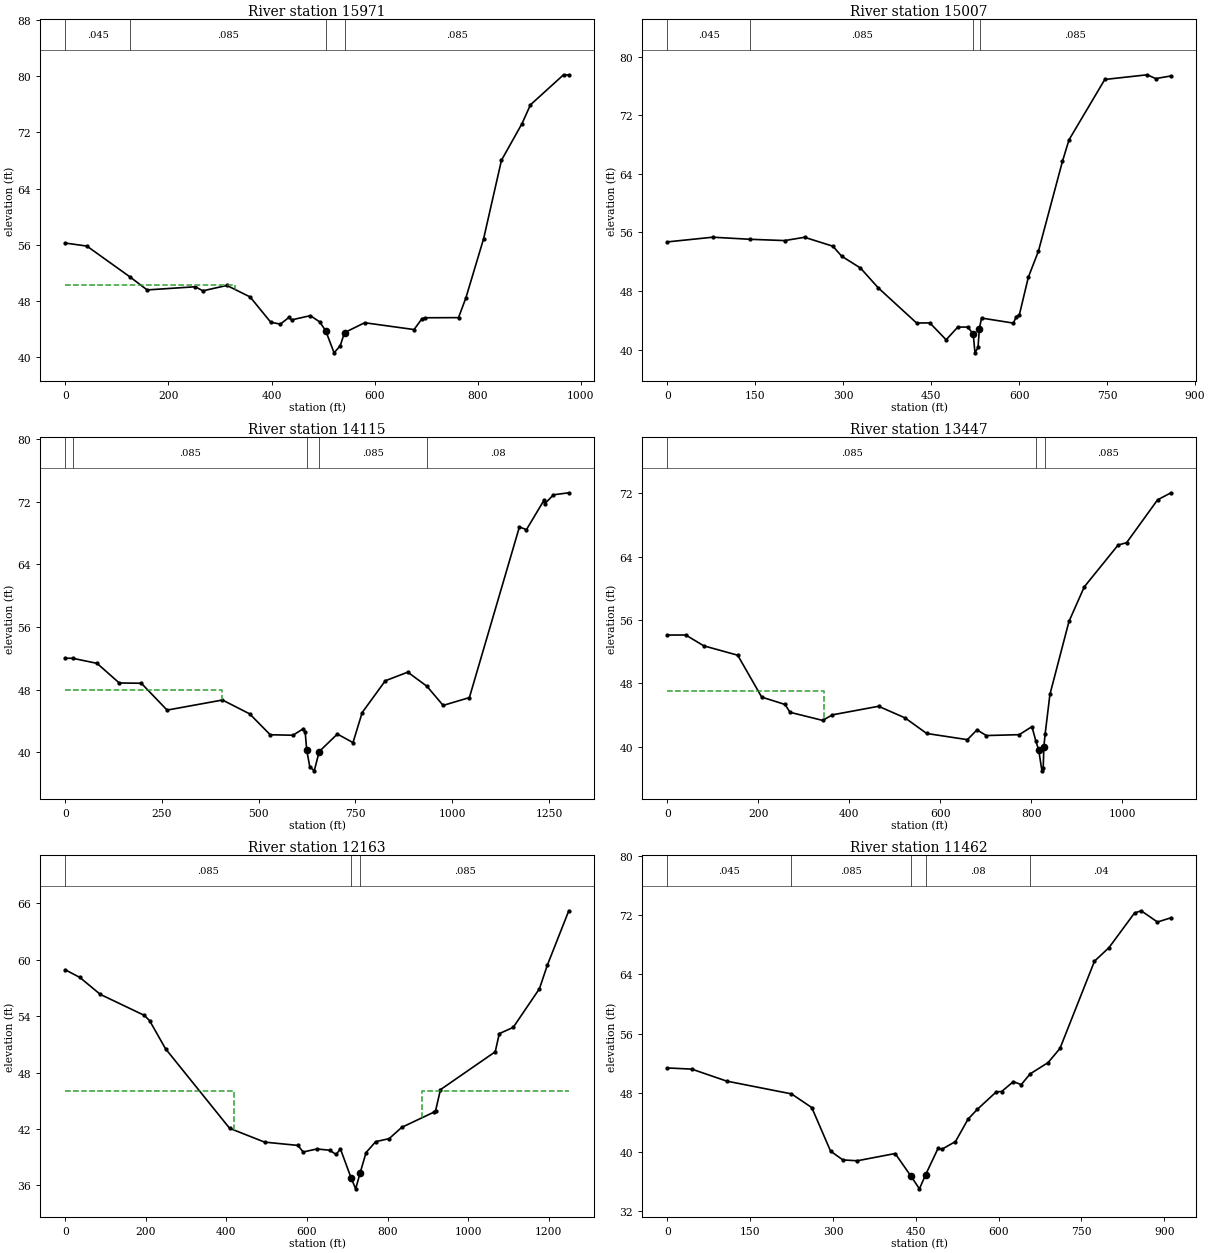
Type RM Length L Ch R = 1 ,15971   ,892.63,964.09,933.81
XS GIS Cut Line= 2
2411125.01715527605720.2618795482411153.02111627604744.123810321
#Sta/Elev= 30
       0   56.23   41.87    55.8  125.39   51.41  158.76   49.55  252.16      50
  266.95   49.42  313.38   50.19  358.46   48.55  398.42   44.95  417.13   44.67
   434.1   45.65  439.01   45.28  475.34   45.88  493.29      45  505.09   43.73
  521.34   40.58  533.19   41.58  541.57   43.46  580.65   44.87   676.4    43.9
  691.58   45.42  697.88   45.58   762.7    45.6  777.01   48.42  811.43   56.87
     846   68.04  885.61   73.23  902.25   75.94   966.4   80.22  976.54   80.19
#Mann= 4 ,-1 , 0
       0    .045       0  125.39    .085       0  505.09     .05       0
  541.57    .085       0
#XS Ineff= 2 , 0
       0     330    50.2               0
Permanent Ineff=
       F       F
Bank Sta=505.09,541.57
XS Rating Curve= 0 ,0
Exp/Cntr=0.3,0.1

Type RM Length L Ch R = 1 ,15007   ,830.97,892.41,872.59
XS GIS Cut Line= 2
2411890.01579897605896.2292914542412096.29373817605062.548448116
#Sta/Elev= 30
       0   54.71    77.2   55.35  141.5355.06309  200.01   54.89  233.85   55.34
  282.15   54.12  297.27   52.75  329.09   51.15  359.73   48.42  425.03   43.63
  447.55   43.65  475.31   41.34  495.25   43.08  511.88   43.08   521.5   42.17
  524.54   39.56  529.69   40.29  532.07   42.88  535.73   44.31  590.14   43.62
  594.93   44.51  600.26   44.76  615.57   49.89  632.75   53.44  673.69   65.69
  684.94   68.65  745.96   76.89  818.41   77.53  832.72   77.01  858.82   77.37
#Mann= 4 ,-1 , 0
       0    .045       0  141.53    .085       0   521.5     .05       0
  532.88    .085       0
Bank Sta=521.5,532.07
XS Rating Curve= 0 ,0
Exp/Cntr=0.3,0.1

Type RM Length L Ch R = 1 ,14115   ,621.14,667.26,666.91
XS GIS Cut Line= 2
2412556.93782727606145.1921830182413134.69482045 604979.26816085
#Sta/Elev= 30
       0   52.01   19.52      52   82.26   51.35   139.4   48.85  196.55   48.81
  263.13   45.38  406.22   46.67  476.53    44.9  529.63   42.23  588.38   42.17
  615.36   43.01  620.06   42.54  623.92   40.29  631.83   38.15  643.47   37.62
  656.21   40.08  703.13   42.32  743.56   41.23  767.33   45.07  827.08   49.13
  885.14   50.23  934.54   48.43  976.58   45.98 1044.35   46.98 1173.63   68.78
 1191.82   68.44 1237.47   72.22 1238.86   71.73 1261.59   72.89 1301.22   73.15
#Mann= 5 ,-1 , 0
       0    .045       0   19.52    .085       0  623.92     .05       0
  656.21    .085       0  934.54     .08       0
#XS Ineff= 2 , 0
       0  406.22      48  885.14       0   50.23
Permanent Ineff=
       F       F
Bank Sta=623.92,656.21
XS Rating Curve= 0 ,0
Exp/Cntr=0.3,0.1

Type RM Length L Ch R = 1 ,13447   ,1285.39,1284.56,1228.22
XS GIS Cut Line= 2
2412814.89661813606523.8269901872413562.23335151605706.298408955
#Sta/Elev= 30
       0    54.1   40.15   54.11   79.95   52.74  154.48   51.56  207.27   46.28
  258.52   45.35  269.73   44.36  341.41   43.34  362.92   44.04  464.42   45.12
  522.53   43.66  570.31   41.69  659.87   40.91   680.9   42.15  701.43   41.43
  773.84   41.54  801.79   42.55  810.68   40.69  816.63   39.62   823.8   36.98
   826.6   37.31  828.03      40  830.84   41.62  841.39   46.62   883.3   55.82
  916.97   60.18  991.36   65.45 1010.12   65.75 1078.22   71.15 1107.64   72.04
#Mann= 3 ,-1 , 0
       0    .085       0  810.68     .05       0  830.84    .085       0
#XS Ineff= 2 , 0
       0     345      47               0
Permanent Ineff=
       F       F
Bank Sta=816.63,828.03
XS Rating Curve= 0 ,0
Exp/Cntr=0.3,0.1

Type RM Length L Ch R = 1 ,12163   ,739.61,700.96,647.57
XS GIS Cut Line= 2
2413904.81728354607393.2063632312414530.16570377606311.142804652
#Sta/Elev= 30
       0   58.94   36.15   58.13   86.77   56.33  196.36   54.09  209.48   53.52
  248.87   50.54  407.92   42.08  494.76   40.61  577.44   40.26  590.43   39.56
  624.51   39.88  655.98   39.75  672.18    39.3  683.01   39.88  709.12   36.84
  720.79   35.64  732.11   37.37  746.65    39.5  770.51   40.66  803.93   40.98
  835.05   42.18  915.55   43.81  919.21   43.96  931.24   46.19 1067.21   50.22
 1077.26   52.15 1111.95   52.82 1176.94   56.93 1196.62   59.44 1249.77   65.22
#Mann= 3 ,-1 , 0
       0    .085       0  709.12     .05       0  732.11    .085       0
#XS Ineff= 2 , 0
       0     420      46     885       0      46
Permanent Ineff=
       F       F
Bank Sta=709.12,732.11
XS Rating Curve= 0 ,0
Exp/Cntr=0.3,0.1

Type RM Length L Ch R = 1 ,11462   ,538.08,506.13,417.57
XS GIS Cut Line= 2
2414900.00739348607452.8367415672414887.62059681606540.342719093
#Sta/Elev= 30
       0   51.34   44.16   51.18  107.29   49.56  224.68   47.83  261.46   45.98
  295.55   40.08  317.93   38.89  343.99   38.78  412.57   39.76  441.41   36.67
  456.52   34.98  467.79    36.9  490.27   40.46  496.88   40.32  521.86   41.38
  544.67   44.42  561.41   45.74  595.89   48.11  605.55   48.15  626.67   49.49
  640.94   49.08  656.97   50.53  689.71   52.07  711.15   53.98  773.71   65.79
  800.05   67.63  846.24   72.31  858.34   72.61  887.74   71.09  912.24   71.66
#Mann= 5 ,-1 , 0
       0    .045       0  224.68    .085       0  441.41     .05       0
  467.79     .08       0  656.97     .04       0
Bank Sta=441.41,467.79
XS Rating Curve= 0 ,0
Exp/Cntr=0.3,0.1

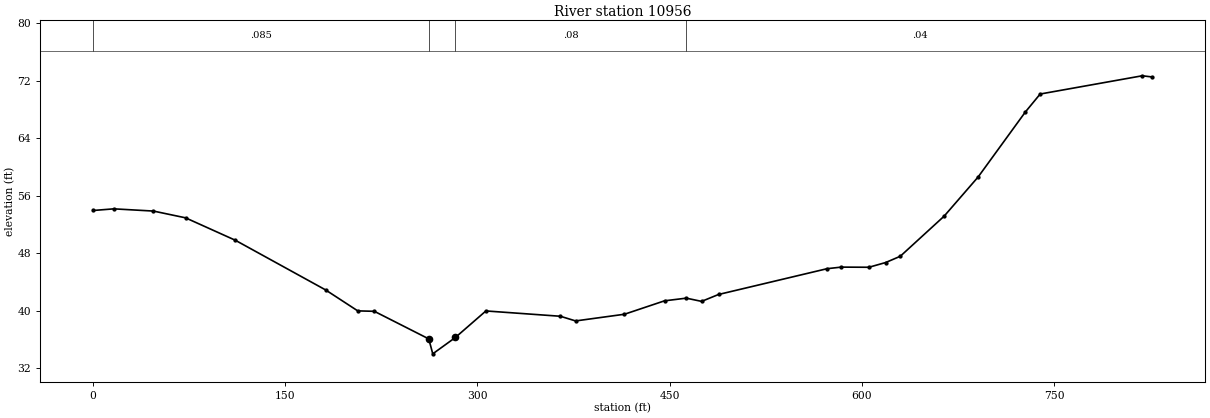
Type RM Length L Ch R = 1 ,10956   ,359.6,536.95,572.17
XS GIS Cut Line= 2
2415552.42566112607063.8778522912414946.04106921606501.735913038
#Sta/Elev= 30
       0   53.95   16.23   54.18   47.15   53.87   72.18   52.93  111.02   49.81
  181.46    42.9  206.58   39.98  219.53   39.92  262.02   36.08  265.14      34
  282.82   36.28  306.62   39.97  364.75   39.23  376.62   38.58  414.75   39.51
  446.06   41.38  463.04   41.75  474.97    41.3  488.18   42.26   572.9   45.85
  583.93   46.07   605.6   46.05  618.66   46.71  630.05   47.58  664.27   53.16
  690.83   58.62  727.67   67.66  739.23   70.16  818.89    72.7  826.87   72.53
#Mann= 4 ,-1 , 0
       0    .085       0  262.02     .05       0  282.82     .08       0
  463.04     .04       0
Bank Sta=262.02,282.82
XS Rating Curve= 0 ,0
Exp/Cntr=0.3,0.1