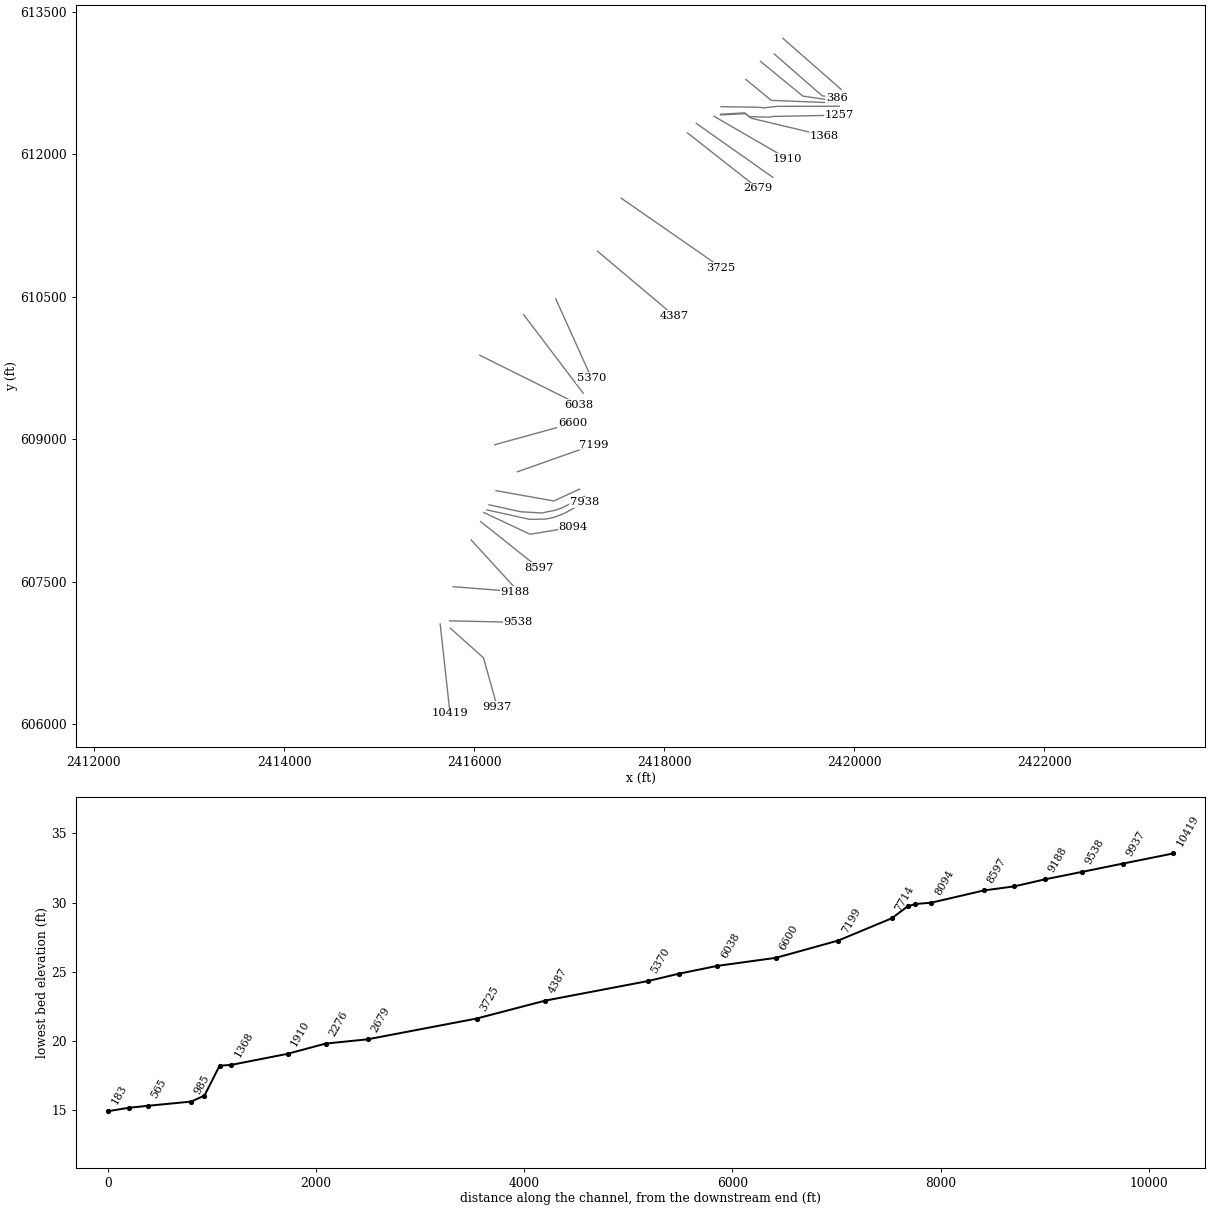
HEC-RAS study DTL_Rainbow_Creek.prj: DTL_Rainbow_Creek

--- DTL_Rainbow_Creek.g01 (geometry) --- (continued)

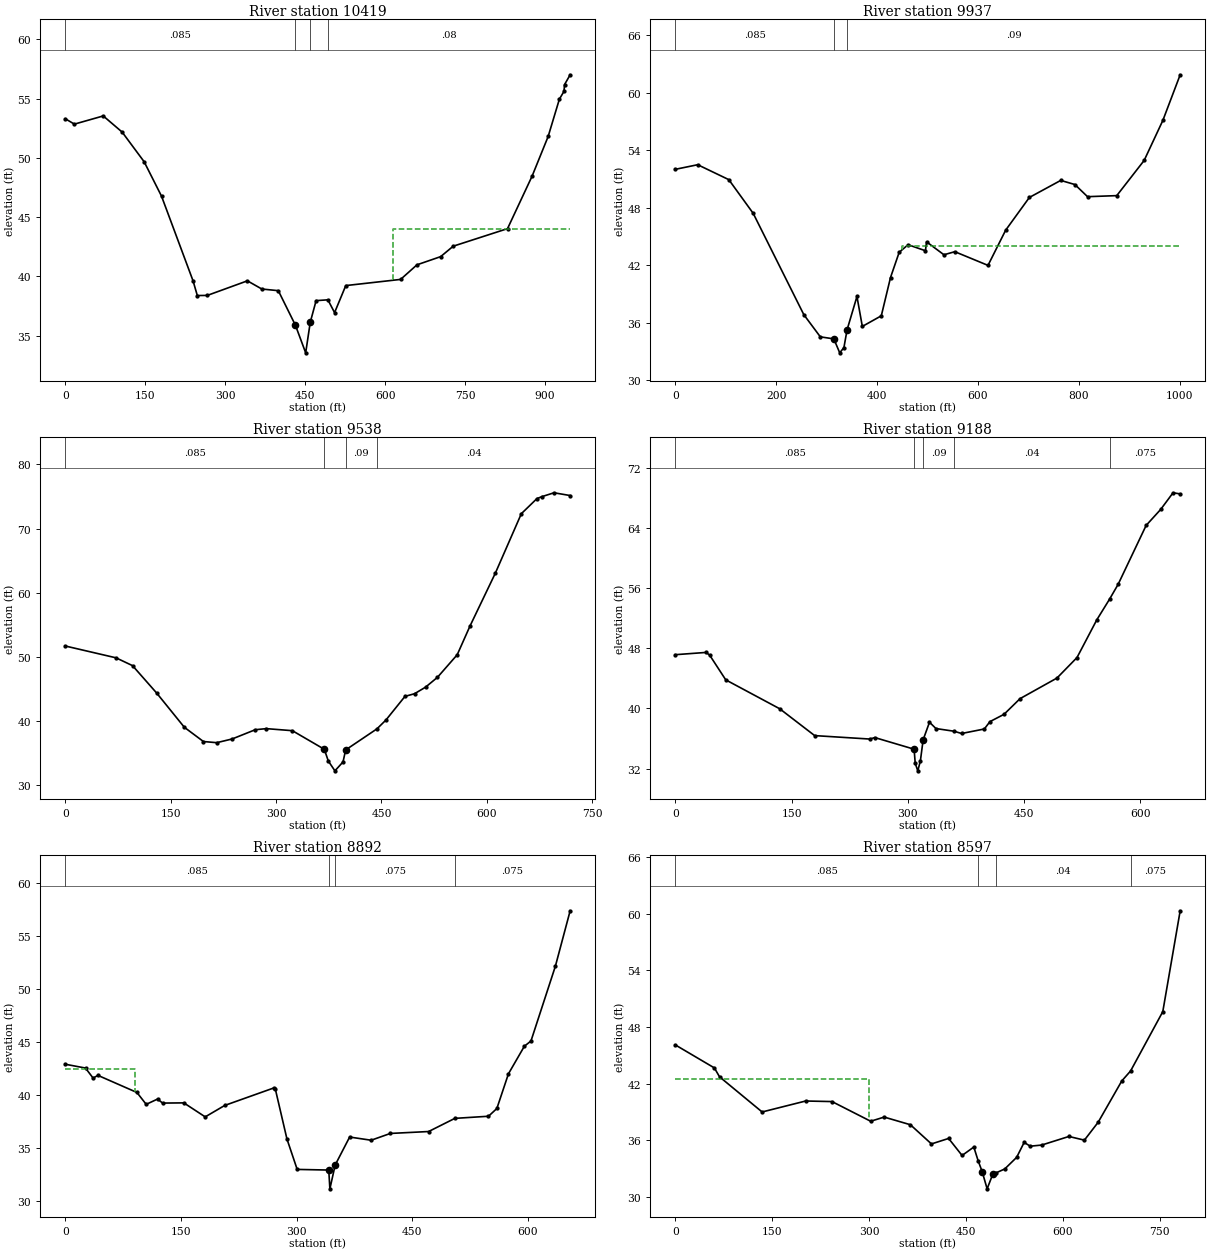
Type RM Length L Ch R = 1 ,10419   ,287.93,481.67,426.92
XS GIS Cut Line= 2
2415643.21519461607056.4592476342415746.43850029606115.062699571
#Sta/Elev= 30
       0   53.29   16.97   52.84   71.11   53.53  106.54   52.17  147.81   49.67
  180.41   46.77  239.57   39.63  247.59   38.39  266.29    38.4  341.52   39.63
  368.62   38.94  399.54    38.8  431.72   35.88  450.88   33.56  459.43   36.13
  470.44   37.96  492.55   38.03  505.09   36.95  526.12   39.23  628.96   39.75
  659.67   40.98  704.09   41.67  727.67   42.55  829.55   44.03  875.69   48.46
  905.78    51.8  926.88   54.95  935.45    55.6  936.63   56.18  947.04      57
#Mann= 4 ,-1 , 0
       0    .085       0  431.72     .05       0  459.43     .09       0
  492.55     .08       0
#XS Ineff= 2 , 0
       0                     615       0      44
Permanent Ineff=
       F       F
Bank Sta=431.72,459.43
XS Rating Curve= 0 ,0
Exp/Cntr=0.3,0.1

Type RM Length L Ch R = 1 ,9937    ,247.9,399.21,392.98
XS GIS Cut Line= 3
 2415750.2163434607011.8276727352416098.95254652606699.526595354
2416242.45888054606186.361044154
#Sta/Elev= 30
       0   52.01   44.29   52.49  105.96   50.93  154.31   47.41  254.71   36.82
  287.47    34.5  314.21   34.29  325.91   32.83  334.23   33.38   340.5   35.24
  360.07   38.72  370.72   35.59  408.34    36.7   426.6    40.7  443.82   43.34
   461.5   44.13  495.86    43.5  498.14   44.43  532.55   43.08  554.15    43.4
  619.92   41.97  654.96   45.65  701.97   49.07  764.14   50.85  792.21   50.42
  817.29   49.15  875.25   49.26  929.59   52.94  966.72   57.13 1000.99   61.89
#Mann= 3 , 0 , 0
       0    .085       0  314.21     .05       0   340.5     .09       0
#XS Ineff= 2 , 0
       0                     450       0      44
Permanent Ineff=
       F       F
Bank Sta=314.21,340.5
XS Rating Curve= 0 ,0
Exp/Cntr=0.3,0.1

Type RM Length L Ch R = 1 ,9538    ,348.87,350.24,340.84
XS GIS Cut Line= 2
2415742.30956811607089.490705475 2416460.7437758607072.974976569
#Sta/Elev= 30
       0   51.68   72.12   49.84   95.65   48.62   129.9   44.36  169.41   39.01
  196.56   36.79  215.51   36.61  237.48   37.19  270.37   38.63  286.09    38.8
  323.18   38.48  368.65   35.58  374.35   33.75  383.75   32.22  395.29   33.61
  399.05   35.48  443.53   38.76  456.37   40.14   483.5   43.83  497.06   44.24
  512.82   45.27  529.73    46.8  557.86   50.32  576.23   54.84  612.01   63.01
  649.14   72.31  671.41   74.67  678.73   74.98  695.65   75.57  718.62   75.14
#Mann= 4 ,-1 , 0
       0    .085       0  368.65     .05       0  399.05     .09       0
  443.53     .04       0
Bank Sta=368.65,399.05
XS Rating Curve= 0 ,0
Exp/Cntr=0.3,0.1

Type RM Length L Ch R = 1 ,9188    ,396.01,296.01,232.31
XS GIS Cut Line= 2
2415779.46995816607448.7078093442416428.69527425607397.536272913
#Sta/Elev= 30
       0   47.15   39.56   47.45   44.16    47.1      65    43.8  134.65   39.95
   179.7   36.38  251.05   35.92  257.24   36.12     308   34.57  309.42   32.69
  312.75   31.69  316.07      33  319.64   35.82  327.84   38.16  336.14   37.32
  359.61   36.96  369.24   36.66  398.58   37.26  405.81   38.24  423.95   39.21
  444.69    41.3   492.3   44.04  518.15   46.77  543.69   51.79   560.2   54.55
  571.18   56.51  607.35   64.36  626.14   66.49  642.04    68.7  651.24   68.55
#Mann= 5 ,-1 , 0
       0    .085       0     308     .05       0  319.64     .09       0
  359.61     .04       0   560.2    .075       0
Bank Sta=308,319.64
XS Rating Curve= 0 ,0
Exp/Cntr=0.3,0.1

Type RM Length L Ch R = 1 ,8892    ,250.99,294.74,307.23
XS GIS Cut Line= 2
2415969.40084066607940.0507445342416411.19658908607456.965673804
#Sta/Elev= 30
       0   42.92   26.14   42.56   35.95   41.62    42.3   41.87   92.83   40.26
  104.86   39.14   119.6   39.64  126.13   39.26  153.64   39.28  181.38   37.96
  206.73   39.04   270.1   40.68  272.38   40.56  287.37   35.88  300.65   33.01
   341.6   32.95  343.06   31.18  349.89   33.42  368.68   36.06  396.58   35.76
   421.5    36.4  471.11   36.58  505.12   37.82  548.74   38.02   559.6   38.75
  574.63   42.02   595.3   44.62  603.83   45.11   635.5   52.16  654.64   57.38
#Mann= 4 ,-1 , 0
       0    .085       0   341.6     .05       0  349.89    .075       0
  505.12    .075       0
#XS Ineff= 2 , 0
       0      90    42.5               0
Permanent Ineff=
       F       F
Bank Sta=341.6,349.89
XS Rating Curve= 0 ,0
Exp/Cntr=0.3,0.1

Type RM Length L Ch R = 1 ,8597    ,217.03,502.4,458.39
XS GIS Cut Line= 2
2416068.49521413 608134.110559272416679.57718393607646.896556303
#Sta/Elev= 30
       0    46.1   60.37   43.67   68.37   42.73  134.31   39.01  201.74   40.17
  242.52   40.11  302.36   38.03  323.28   38.47  363.85   37.66  396.47   35.63
  423.02   36.21  443.88   34.41  462.06    35.3  468.84   33.83  475.06   32.69
  482.66   30.88  491.37   32.42  496.12   32.56   509.9   32.98  528.37   34.21
  539.98   35.79  549.43   35.39  567.08   35.51  609.28   36.42  633.25   36.03
  654.64   37.93  691.13   42.29  704.79   43.35  754.62   49.62  781.54   60.29
#Mann= 4 ,-1 , 0
       0    .085       0  468.84     .05       0  496.12     .04       0
  704.79    .075       0
#XS Ineff= 2 , 0
       0     300    42.5               0
Permanent Ineff=
       F       F
Bank Sta=475.06,491.37
XS Rating Curve= 0 ,0
Exp/Cntr=0.3,0.1

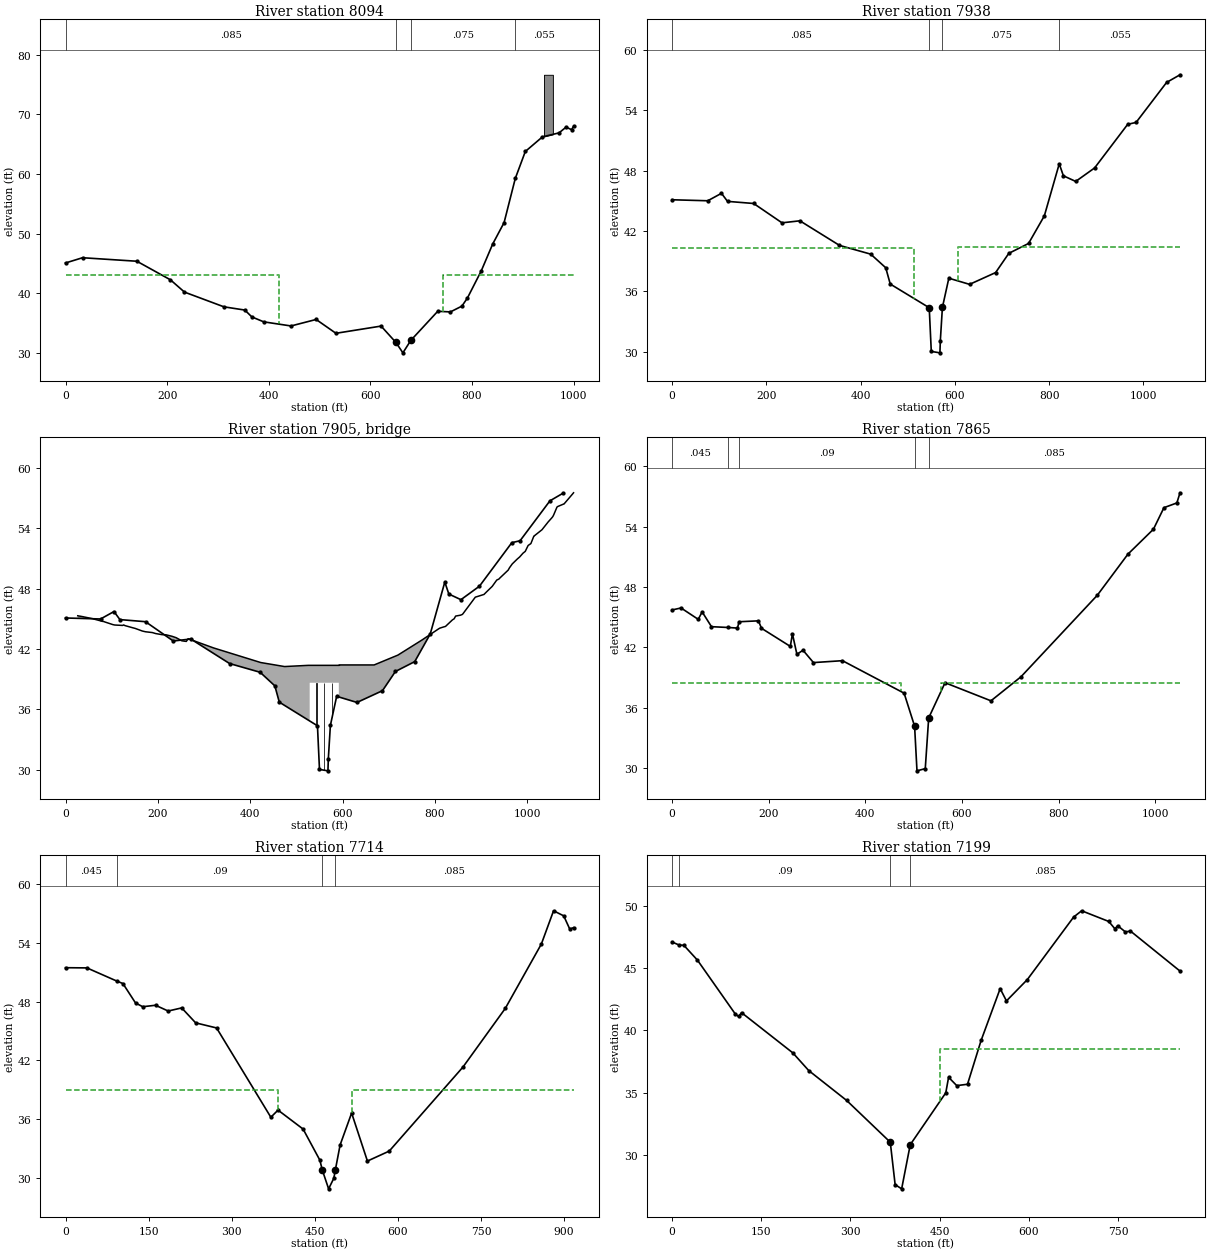
Type RM Length L Ch R = 1 ,8094    ,183.94,156.21,142.54
XS GIS Cut Line= 3
 2416100.8672124608229.9643011392416588.87755938608000.557727769
2417043.51967753608075.636242688
#Sta/Elev= 30
       0   45.08   33.54   45.96   140.5   45.37   206.6   42.25  234.22   40.19
  311.86   37.72   352.9   37.18   366.8   36.03  390.21    35.2   443.9   34.51
  493.32    35.6   532.3   33.28   621.2   34.49  650.33   31.75  664.13      30
  679.82    32.1  732.68   36.97  757.66   36.87   780.3   37.84   791.2   39.21
  818.36   43.75   840.9   48.26  863.34   51.86  885.34   59.26  905.11   63.79
  938.81   66.24  971.45   66.91  985.25   67.87  996.09   67.45 1000.04      68
#Mann= 4 ,-1 , 0
       0    .085       0  650.33     .05       0  679.82    .075       0
  885.34    .055       0
#XS Ineff= 2 , 0
       0     420      43   742.5       0      43
Permanent Ineff=
       F       F
#Block Obstruct= 1 ,-1
  941.81  959.38   76.66
Bank Sta=650.33,679.82
XS Rating Curve= 0 ,0
Exp/Cntr=0.5,0.3

Type RM Length L Ch R = 1 ,7938    ,71.74,72.77,66.54
BEGIN DESCRIPTION:
Survyed Section
END DESCRIPTION:
XS GIS Cut Line= 6
2416134.06479475608257.171257079    2416586.1776608157.058500022
2416753.92560001608160.5377000122416851.17364818 608181.32526882
2416953.32416432608222.5783618542417160.68378025608336.086082697
#Sta/Elev= 30
       0    45.1   75.89      45  105.01   45.74  117.78   44.94  173.25   44.73
  233.37   42.81  271.31   43.01  355.27   40.57  421.48    39.7  453.33   38.35
 462.958   36.73 545.609   34.38 549.967   30.04 568.298    29.9 569.151    31.1
 573.553   34.41 587.178   37.31 631.212    36.7  686.39   37.87  714.42   39.78
  756.25   40.76  789.75    43.5  821.37   48.67  830.12   47.48  856.27   46.92
  896.37   48.26  966.54   52.59  984.35   52.78 1049.03   56.75 1077.49   57.51
#Mann= 4 ,-1 , 0
       0    .085       0 545.609     .05       0 573.553    .075       0
  821.37    .055       0
#XS Ineff= 2 , 0
       0  513.75   40.27  606.85       0   40.43
Permanent Ineff=
       F       F
Bank Sta=545.609,573.553
XS Rating Curve= 0 ,0
Exp/Cntr=0.5,0.3

Type RM Length L Ch R = 3 ,7905    ,,,
BEGIN DESCRIPTION:
1091 (Shady Grove Church Road)
END DESCRIPTION:
Bridge Culvert--1,0,-1,-1, 0
Deck Dist Width WeirC Skew NumUp NumDn MinLoCord MaxHiCord MaxSubmerge Is_Ogee
20,25,2.6,0, 92, 88, , , 0.98, 0, 1,1,,
   26.48   38.67   39.41   40.39   59.93   60.97   62.46   81.41   82.78    84.8
   102.6  106.73  123.88  125.79  128.92  145.32  151.07  166.54  173.16  187.97
  195.34  209.24  217.46  230.61  239.57  251.86   261.6 265.554 320.791 422.752
 474.374 525.765 527.604 527.604 528.754 528.754 543.309 560.164 577.544 591.851
 591.851 593.001 593.001 594.838 668.303 719.821  771.93  807.99  810.65  818.82
  822.88  837.84  841.61  844.81  854.28  854.73  859.22  860.67  887.43   906.2
  913.42     924  933.83  938.49  940.72  958.59  961.54  967.51  978.49  983.51
  990.62  995.52 1001.81 1007.78 1014.04  1014.2 1014.44 1029.73 1031.72 1045.18
 1051.21  1053.5 1055.36 1057.23 1064.31 1066.18  1078.7  1079.4 1095.62 1099.12
 1099.58 1100.16
   45.32   45.22    45.2    45.2   45.02   44.99   44.98   44.75   44.75   44.71
   44.44    44.4   44.36   44.41   44.34   44.13   44.06    43.8   43.73   43.65
   43.55   43.44   43.43   43.28   43.14   42.83   42.77   43.04   42.12   40.67
   40.27   40.39   40.39   40.39   40.39   40.39   40.39   40.39   40.39   40.39
   40.39   40.39   40.43   40.43   40.43   41.41   42.91   44.02   44.09   44.21
   44.26   44.91   45.02   45.29   45.37   45.37   45.45   45.52   47.17   47.44
   47.77   48.24   48.87   48.97   49.08   49.86    50.1   50.48   50.97   51.17
   51.54   51.72   52.31    52.5   53.22   53.24   53.24    53.8   53.87   54.65
   54.96   55.08   55.19   55.36   56.13   56.19   56.43   56.43    57.3   57.49
   57.52   57.55
                                                                                
                                                                                
                                                                                
                       0       0       0   38.66   38.66   38.66   38.66   38.66
       0       0       0
                                                                                
                                                                                
                                                                                
                                                                                
                
   13.92   14.96   16.45    35.4   36.77   38.79   56.59   60.72   77.87   79.78
   82.91   99.31  105.06  120.53  127.15  141.96  149.33  163.23  171.45   184.6
  193.56  205.85  215.59 219.544 274.781 376.742 428.364  479.37 481.594 481.594
 482.744 482.744 497.299 514.154 531.534 545.841 545.841 546.991 546.991 548.828
 622.293 673.811  725.92  761.98  764.64  772.81  776.87  791.83   795.6   798.8
  808.27  808.72  813.21  814.66  841.42  860.19  867.41  877.99  887.82  892.48
  894.71  912.58  915.53   921.5  932.48   937.5  944.61  949.51   955.8  961.77
  968.03  968.19  968.43  983.72  985.71  999.17  1005.2 1007.49 1009.35 1011.22
  1018.3 1020.17 1032.69 1033.39 1049.61 1053.11 1053.57 1054.15
   45.02   44.99   44.98   44.75   44.75   44.71   44.44    44.4   44.36   44.41
   44.34   44.13   44.06    43.8   43.73   43.65   43.55   43.44   43.43   43.28
   43.14   42.83   42.77   43.04   42.12   40.67   40.27   40.39   40.39   40.39
   40.39   40.39   40.39   40.39   40.39   40.39   40.39   40.39   40.43   40.43
   40.43   41.41   42.91   44.02   44.09   44.21   44.26   44.91   45.02   45.29
   45.37   45.37   45.45   45.52   47.17   47.44   47.77   48.24   48.87   48.97
   49.08   49.86    50.1   50.48   50.97   51.17   51.54   51.72   52.31    52.5
   53.22   53.24   53.24    53.8   53.87   54.65   54.96   55.08   55.19   55.36
   56.13   56.19   56.43   56.43    57.3   57.49   57.52   57.55
                                                                                
                                                                                
                                                                       0       0
       0   38.66   38.66   38.66   38.66   38.66       0       0       0
                                                                                
                                                                                
                                                                                
                                                                                
                                                                
Pier Skew, UpSta & Num, DnSta & Num=  ,543.31, 2 ,497.3, 2 , 0 , 0 , 0 ,,
     .95     .95
      29   38.73
     .95     .95
      29   38.73
Pier Skew, UpSta & Num, DnSta & Num=  ,560.16, 2 ,514.15, 2 , 0 , 0 , 0 ,,
     .95     .95
      29   38.73
     .95     .95
      29   38.73
Pier Skew, UpSta & Num, DnSta & Num=  ,577.54, 2 ,531.53, 2 , 0 , 0 , 0 ,,
     .95     .95
      29   38.73
     .95     .95
      29   38.73
BR Coef=-1 , 1 , 0 ,0.9, 0 ,,,0.8,0,1.2,0,
WSPro=,,,, 1 ,,,, 0 ,,,, 0 ,,,,-1 ,-1 ,-1 , 0 , 0 , 0 , 0 , 0
BC Design=,, 0 ,, 0 ,,,,,,
BC Use User HTab Curves=0
BC User HTab FreeFlow(D)= 0

Type RM Length L Ch R = 1 ,7865    ,161.49,151.95,157.29
BEGIN DESCRIPTION:
Survyed Section
END DESCRIPTION:
XS GIS Cut Line= 6
2416157.72879829608310.9778469652416489.71797575608237.311609387
    2416712.2403608224.4977000062416853.69409998608253.835400015
2416923.95952538608278.1577057842417161.81332022608399.340322167
#Sta/Elev= 30
       0   45.72   18.72   45.92   54.35   44.79   62.41   45.53   81.72   44.06
  116.13   43.98  135.53   43.92  138.72   44.55  178.88   44.64  185.19    43.9
  244.81    42.1  249.18   43.35  258.44   41.31  271.03   41.72  292.66   40.49
  352.63   40.68 480.197   37.45 501.892   34.17 506.826   29.73 523.953   29.95
  531.04   34.99 564.868   38.49 659.843   36.69  721.94   39.08  879.77   47.18
   943.2   51.27  995.97   53.75 1017.66   55.89 1044.41   56.36 1050.92   57.37
#Mann= 5 ,-1 , 0
       0    .045       0  116.13    .035       0  138.72     .09       0
 501.892     .05       0  531.04    .085       0
#XS Ineff= 2 , 0
       0  472.74    38.5  555.84       0    38.5
Permanent Ineff=
       F       F
Bank Sta=501.892,531.04
XS Rating Curve= 0 ,0
Exp/Cntr=0.5,0.3

Type RM Length L Ch R = 1 ,7714    ,355.29,514.33,452.64
XS GIS Cut Line= 3
2416230.16909926608459.3708745092416839.13927579608350.924130753
2417110.25613526 608476.05498895
#Sta/Elev= 30
       0   51.48   38.63   51.46   92.72   50.11  103.65   49.86  126.45   47.87
   139.4   47.49  162.49   47.64  185.35   47.05  209.75   47.37  234.96   45.84
  272.71   45.32  370.71   36.19  383.66   36.92  428.94   34.98   459.2    31.8
   463.6   30.79  474.97   28.87  484.37   29.95   487.1   30.79  495.75   33.36
  516.53   36.62  545.04   31.71  584.44   32.73  717.49   41.32  793.93   47.32
  859.04    53.9  881.06    57.3  899.43   56.78  910.29   55.43  917.15   55.57
#Mann= 4 ,-1 , 0
       0    .045       0   92.72     .09       0   463.6     .05       0
   487.1    .085       0
#XS Ineff= 2 , 0
       0     383      39  516.53       0      39
Permanent Ineff=
       F       F
Bank Sta=463.6,487.1
XS Rating Curve= 0 ,0
Exp/Cntr=0.3,0.1

Type RM Length L Ch R = 1 ,7199    ,374.11,599.02,316.28
XS GIS Cut Line= 2
2416456.61484362608658.4849522862417261.75662814608943.381276026
#Sta/Elev= 30
       0   47.11   11.87   46.87   20.07   46.84   42.84   45.65  106.58   41.31
  112.07   41.12  116.94   41.43  203.24   38.19  229.93   36.77  293.59   34.37
  366.98   31.01  375.15    27.6  386.11   27.26  400.55   30.81  460.29   34.98
  465.02   36.23  478.76   35.56  496.82   35.67  519.65   39.19  551.73   43.36
  562.28   42.37  597.43   44.09   675.3   49.12  688.73   49.62  734.32   48.76
  744.62   48.17  749.23   48.42  762.28   47.92  770.73   47.99  854.06   44.77
#Mann= 4 ,-1 , 0
       0    .045       0   11.87     .09       0  366.98     .05       0
  400.55    .085       0
#XS Ineff= 2 , 0
       0                     450       0    38.5
Permanent Ineff=
       F       F
Bank Sta=366.98,400.55
XS Rating Curve= 0 ,0
Exp/Cntr=0.3,0.1

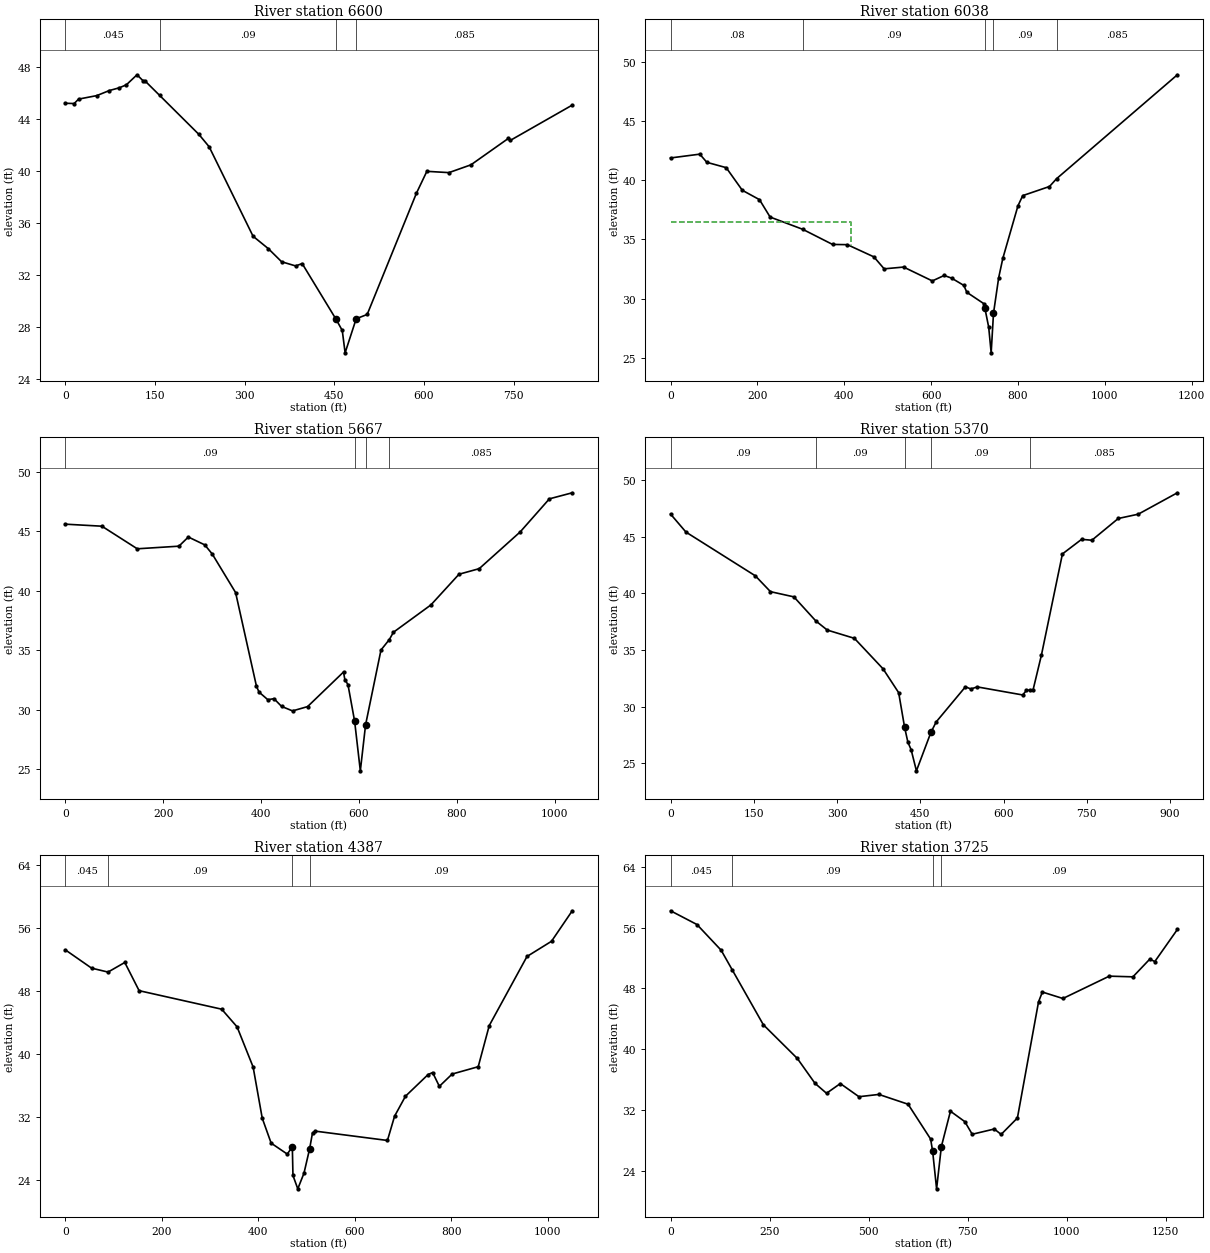
Type RM Length L Ch R = 1 ,6600    ,726.16,561.86,499.35
XS GIS Cut Line= 2
2416217.65601343608943.2101928892417035.17762029609168.445737645
#Sta/Elev= 30
       0   45.19   14.67   45.17   21.96   45.51    52.5   45.78   73.51   46.17
   90.15   46.38  101.95   46.61  119.75   47.38  129.44   46.94  133.53   46.89
  157.72   45.79  223.25    42.8   240.4   41.85  313.94   34.97  339.63   34.01
  361.68   33.01   385.1   32.69  396.09   32.87  452.48   28.61  463.16   27.73
  467.93   26.01  486.48   28.63  504.86   28.96  587.37   38.29  604.71   39.96
  641.59   39.86  678.48   40.46  741.09   42.49  744.46   42.34  847.98   45.05
#Mann= 4 ,-1 , 0
       0    .045       0  157.72     .09       0  452.48     .05       0
  486.48    .085       0
Bank Sta=452.48,486.48
XS Rating Curve= 0 ,0
Exp/Cntr=0.3,0.1

Type RM Length L Ch R = 1 ,6038    ,488.76,371.07,301.18
XS GIS Cut Line= 2
2416060.23734966609884.7778241192417104.85720345 609364.53236334
#Sta/Elev= 30
       0   41.88   67.27    42.2   83.59   41.51  128.13   41.06  165.24   39.15
  204.72   38.36  229.28   36.89  304.12   35.86  372.99   34.58  407.18   34.56
   468.2   33.53  491.86   32.52  536.61   32.67  602.74    31.5  629.97   31.96
  646.98   31.74  675.31   31.12  682.24   30.54  721.34   29.58  723.54   29.24
  732.54    27.6  738.24   25.43  743.61   28.77  755.57   31.78  765.06    33.4
  799.92   37.84  810.91    38.7  872.52   39.47   888.9   40.13    1167    48.9
#Mann= 5 ,-1 , 0
       0     .08       0  304.12     .09       0  723.54     .05       0
  743.61     .09       0   888.9    .085       0
#XS Ineff= 2 , 0
       0     415    36.5               0
Permanent Ineff=
       F       F
Bank Sta=723.54,743.61
XS Rating Curve= 0 ,0
Exp/Cntr=0.3,0.1

Type RM Length L Ch R = 1 ,5667    ,283.99,297.21,233.39
XS GIS Cut Line= 2
2416522.14110172610311.3075758812417147.79539274609485.443911746
#Sta/Elev= 30
       0    45.6   74.54   45.43  146.83   43.53  231.96   43.75  251.23   44.52
   284.8   43.86  300.14   43.09  347.85   39.85  390.53   31.97  395.78   31.48
  413.77   30.84  426.23   30.93   441.8   30.28  464.23    29.9  494.98   30.26
  568.49   33.17  571.15   32.54  577.57   32.11   591.2   29.03  602.85   24.86
  613.58   28.73  645.08   35.02  662.17    35.9  670.44   36.51  747.13   38.81
  804.53   41.39   845.9   41.86  929.68   44.95  989.34   47.73  1036.1   48.24
#Mann= 4 ,-1 , 0
       0     .09       0   591.2     .05       0  613.58     .09       0
  662.17    .085       0
Bank Sta=591.2,613.58
XS Rating Curve= 0 ,0
Exp/Cntr=0.3,0.1

Type RM Length L Ch R = 1 ,5370    ,848.76,982.8,952.41
XS GIS Cut Line= 2
2416858.92407827610478.3064871132417234.23209807609645.841358185
#Sta/Elev= 30
       0      47   27.73   45.41  152.69   41.55  180.01   40.15   222.2   39.69
  261.62   37.57   282.3   36.76  331.22   36.03  382.81   33.34  411.01   31.23
  421.62   28.19  427.55   26.87  433.48   26.19  442.99   24.33  469.12   27.73
  478.62   28.65  531.31   31.75  541.03   31.56  552.69   31.74  634.34   31.03
  641.25   31.43  647.98   31.47  653.27    31.5  668.17   34.54  706.04   43.48
  740.63   44.77  759.11   44.69  806.65   46.61   842.7   46.99  913.16   48.88
#Mann= 5 ,-1 , 0
       0     .09       0  261.62     .09       0  421.62     .05       0
  469.12     .09       0  647.98    .085       0
Bank Sta=421.62,469.12
XS Rating Curve= 0 ,0
Exp/Cntr=0.3,0.1

Type RM Length L Ch R = 1 ,4387    ,648.57,662.17,663.2
XS GIS Cut Line= 2
2417298.44531548610979.844578058 2418101.9561588610302.697684303
#Sta/Elev= 30
       0   53.24    54.2   50.93   88.27   50.43  123.04   51.65  152.74   48.07
  323.93   45.72  355.82   43.48  389.13   38.38     408   31.89  426.49   28.72
   459.9   27.33  470.41   28.26  471.71   24.62  481.71   22.92  494.54    24.9
  506.21   27.99   512.3   30.04  518.38   30.24  667.59   29.06   682.4   32.14
  704.94   34.67  751.98   37.43   761.3   37.68  775.23   35.93   801.8   37.49
  855.82   38.42  878.68   43.64  956.95   52.41 1007.79   54.34 1050.79   58.21
#Mann= 4 ,-1 , 0
       0    .045       0   88.27     .09       0  470.41     .05       0
  506.21     .09       0
Bank Sta=470.41,506.21
XS Rating Curve= 0 ,0
Exp/Cntr=0.3,0.1

Type RM Length L Ch R = 1 ,3725    ,971.46,1045.77,948.86
XS GIS Cut Line= 2
2417548.21413893611537.5899862352418599.31334785610807.659980088
#Sta/Elev= 30
       0    58.2   66.72   56.39  127.73   53.01  155.48   50.45  234.22   43.21
  320.16   38.77  364.71    35.5  393.82   34.19  428.66   35.47  475.68   33.74
  525.96   34.04  599.77   32.75  656.65   28.17  661.73   26.57  671.73   21.62
  683.74   27.17  706.72   31.83  743.01   30.46  761.69    28.8  817.44   29.49
   834.7   28.78  875.79   30.94  929.14   46.22  938.78   47.51  990.68   46.66
 1107.78    49.6 1167.46   49.51 1210.03   51.84 1222.72   51.52 1279.69   55.74
#Mann= 4 ,-1 , 0
       0    .045       0  155.48     .09       0  661.73     .05       0
  683.74     .09       0
#XS Ineff= 2 , 0
       0  525.96   34.04               0
Permanent Ineff=
       F       F
Bank Sta=661.73,683.74
XS Rating Curve= 0 ,0
Exp/Cntr=0.3,0.1

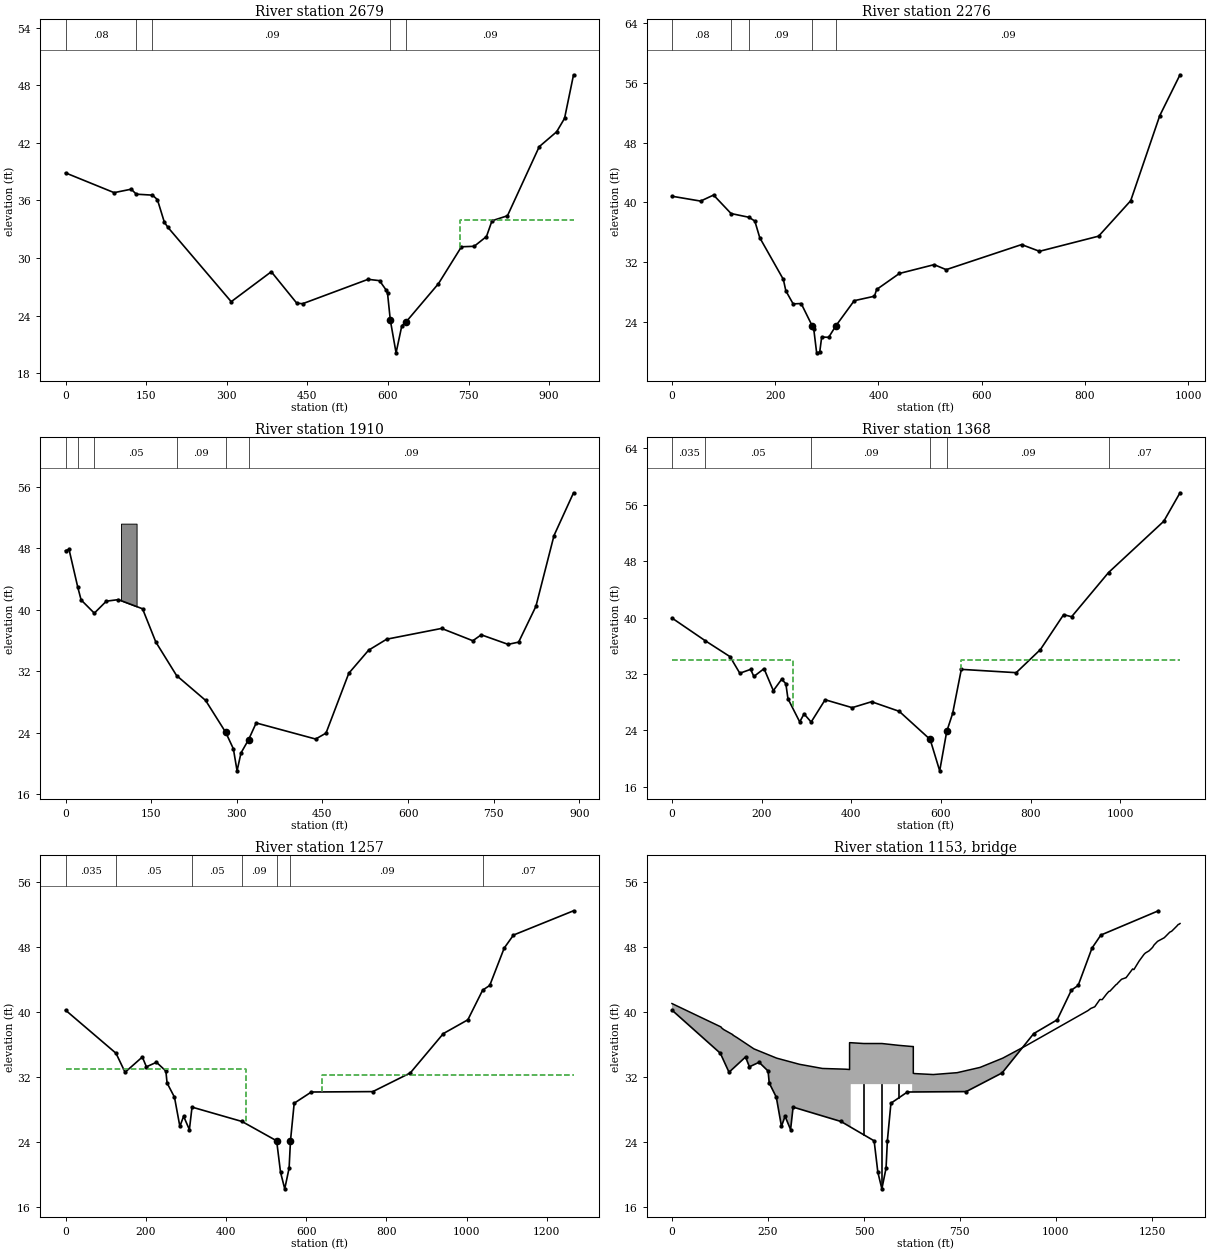
Type RM Length L Ch R = 1 ,2679    ,158.67,403.71,172.86
XS GIS Cut Line= 2
2418243.58569941612225.7961439042418987.21900828611641.865701407
#Sta/Elev= 30
       0   38.87   90.45   36.81  122.34   37.17  131.71   36.65  161.87   36.55
  171.05   36.08  184.01   33.72  190.82   33.18   308.4   25.45  382.99   28.57
  430.47   25.29  441.38   25.24  563.12   27.78  584.43   27.64  596.49   26.68
  599.35   26.31  604.51   23.52   615.2   20.12  625.89   22.94  633.02   23.29
     694   27.32  736.86   31.17   760.6   31.22  783.47   32.24  793.75   33.88
   822.5    34.4  881.64    41.6  914.03   43.15  928.76   44.55   945.5   49.09
#Mann= 5 ,-1 , 0
       0     .08       0  131.71    .035       0  161.87     .09       0
  604.51     .05       0  633.02     .09       0
#XS Ineff= 2 , 0
       0                     735       0      34
Permanent Ineff=
       F       F
Bank Sta=604.51,633.02
XS Rating Curve= 0 ,0
Exp/Cntr=0.3,0.1

Type RM Length L Ch R = 1 ,2276    ,192.54,365.77,231.63
XS GIS Cut Line= 2
2418336.61550865612325.8031888312419141.06847377611758.683278546
#Sta/Elev= 30
       0    40.8   55.47   40.15   80.58   40.96  114.47   38.48  148.9237.98348
   160.5   37.48  170.08   35.24  215.79   29.65  220.61   28.12  234.77   26.37
  250.32   26.42  272.15   23.36  274.69      23  280.29   19.81  286.22    19.9
  290.05   21.93   303.6   21.89  317.31   23.41  353.07    26.8  392.32    27.4
  396.46    28.3  440.61   30.45  507.92   31.63  531.24   30.96  677.34   34.32
  711.99   33.42  826.58   35.45  888.71    40.2     945    51.6  984.26   57.08
#Mann= 5 ,-1 , 0
       0     .08       0  114.47    .035       0  148.92     .09       0
  272.15     .05       0  317.31     .09       0
Bank Sta=272.15,317.31
XS Rating Curve= 0 ,0
Exp/Cntr=0.3,0.1

Type RM Length L Ch R = 1 ,1910    ,222.43,541.77,316.37
XS GIS Cut Line= 2
2418522.89633608612400.9328841272419292.80403806611954.834238008
#Sta/Elev= 30
       0   47.68    6.18   47.83   21.53   42.91   27.34   41.27   50.45   39.55
   71.51   41.11   92.54   41.31  134.95   40.12   158.2    35.8  194.51   31.45
  245.36   28.22  280.65   24.06  294.02   21.93  300.48   19.07  307.33   21.39
   320.7   23.13  333.97   25.29   438.1    23.2  456.25   23.97  496.13   31.74
  530.85   34.74   562.5   36.17  658.67   37.57   713.4   35.97  728.18   36.74
  775.21    35.5  793.63   35.79  823.89   40.44  855.61   49.64  889.81   55.19
#Mann= 6 ,-1 , 0
       0    .055       0   21.53    .035       0   50.45     .05       0
  194.51     .09       0  280.65     .05       0   320.7     .09       0
#Block Obstruct= 1 ,-1
   97.17  124.48  51.181
Bank Sta=280.65,320.7
XS Rating Curve= 0 ,0
Exp/Cntr=0.3,0.1

Type RM Length L Ch R = 1 ,1368    ,8.88,110.89,116.25
XS GIS Cut Line= 4
 2418591.4164442612414.5169577152418851.64112537612427.668784782
2418914.54518759612380.0942838942419686.66171657612195.992712319
#Sta/Elev= 30
       0   39.94   74.22   36.72   129.5   34.46  151.31   32.11  175.47   32.66
  182.67   31.65  205.36   32.76  226.09   29.64  244.65   31.26  254.01   30.63
  258.68    28.5  284.92   25.21  294.57   26.34  310.49   25.19   341.6   28.35
   401.9   27.23  445.22   28.07  506.88   26.71  575.89   22.72  597.15   18.27
  612.83   23.85  626.06   26.42   645.4   32.66  767.79   32.19  821.81   35.47
  873.57   40.42  891.35   40.12  973.75   46.39 1096.95   53.66 1133.19    57.7
#Mann= 6 ,-1 , 0
       0    .035       0   74.22     .05       0  310.49     .09       0
  575.89     .05       0  612.83     .09       0  973.75     .07       0
#XS Ineff= 2 , 0
       0     270      34     645       0      34
Permanent Ineff=
       F       F
Bank Sta=575.89,612.83
XS Rating Curve= 0 ,0
Exp/Cntr=0.5,0.3

Type RM Length L Ch R = 1 ,1257    ,207.1,145.32,163.63
BEGIN DESCRIPTION:
Survyed Section
END DESCRIPTION:
XS GIS Cut Line= 6
2418595.44186351612422.3113597632418846.13014105 612436.48069717
    2418896.6248612396.6303000152419107.30070002612390.868699998
2419141.81322898612398.6275251062419845.74596103 612411.97989215
#Sta/Elev= 30
       0   40.21  125.93    34.9  148.57   32.56  191.61   34.44  201.72   33.23
  226.83   33.79  250.32   32.71  253.25   31.24  271.75   29.49  285.16    25.9
  294.53   27.14  308.92    25.5 315.495   28.27 440.212    26.5 526.538   24.12
 536.221   20.25 546.682   18.21 557.577   20.76 561.022   24.13 570.265   28.75
 613.071   30.13  766.34   30.18  859.82   32.48  942.16   37.32 1003.32   39.02
 1040.25   42.67 1057.93   43.25 1093.99   47.85 1117.05   49.45  1266.9   52.44
#Mann= 7 ,-1 , 0
       0    .035       0  125.93     .05       0 315.495     .05       0
 440.212     .09       0 526.538     .05       0 561.022     .09       0
 1040.25     .07       0
#XS Ineff= 2 , 0
       0  450.55   32.94  640.55       0   32.28
Permanent Ineff=
       F       F
Bank Sta=526.538,561.022
XS Rating Curve= 0 ,0
Exp/Cntr=0.5,0.3

Type RM Length L Ch R = 3 ,1153    ,,,
BEGIN DESCRIPTION:
SR 1438
END DESCRIPTION:
Bridge Culvert--1,0,-1,-1, 0
Deck Dist Width WeirC Skew NumUp NumDn MinLoCord MaxHiCord MaxSubmerge Is_Ogee
89.24,32.5,2.6,0, 67, 41, , , 0.98, 0, 1,1,,
       0  127.69  129.17  134.58  158.38  158.66  169.63 213.487 272.694 332.286
 391.811 451.593  462.55  462.55  465.55  465.55 499.063  499.09 546.804 589.546
 625.546 625.546 628.546 628.546 632.115 680.426 742.776 802.445 861.534 920.524
 1083.72 1090.96 1100.11 1101.49 1114.49  1120.5 1132.18  1137.8 1140.55 1156.68
    1159 1160.99 1170.96 1182.51 1183.09 1183.19 1183.31 1199.78 1203.06 1206.44
 1216.51 1229.35 1232.99 1242.61 1249.17 1251.94  1255.6 1264.82 1274.24 1282.05
 1285.96 1296.58 1301.43 1314.59 1318.68 1320.64  1323.2
   41.02   38.14   38.03   37.82   37.19   37.14   36.82   35.44    34.3   33.54
   33.03   32.94    32.9    36.2    36.2    36.2    36.1    36.1    36.1   35.88
   35.73   35.73   35.73   32.43    32.4   32.28   32.51   33.16    34.3   35.79
   40.16   40.42    40.6   40.64   41.52    41.5   42.21   42.51   42.54   43.35
   43.41   43.53   44.01    44.2   44.22   44.22   44.24   45.28    45.2   45.46
   46.24   47.07   47.24   47.51   47.81   47.95   48.23   48.68   48.92   49.12
    49.3   49.81   49.92   50.54   50.76   50.78   50.87
                                                                                
                       0       0       0    31.1    31.1    31.1    31.1    31.1
    31.1       0       0       0
                                                                                
                                                                                
                                                                                
                                                        
    3.61    8.17   10.72    25.8   27.28   32.69   56.49   56.77   67.74   80.82
   81.74   84.37  102.02  106.99 111.597 170.804 230.396 289.921 349.703  360.66
  360.66  363.66  363.66  397.19   397.2 444.914 487.656 523.656 523.656 526.656
 526.656 530.225 578.536 640.886 700.555 759.644 818.634  981.83  989.07  998.22
  1234.6
   39.43   39.24   39.09   38.14   38.03   37.82   37.19   37.14   36.82   36.36
   36.35   36.23   35.32   35.19   35.44    34.3   33.54   33.03   32.94    32.9
    36.2    36.2    36.2    36.1    36.1    36.1   35.88   35.73   35.73   35.73
   32.43    32.4   32.28   32.51   33.16    34.3   35.79   40.16   40.42    40.6
    47.4
                                                                                
                                                                               0
       0       0    31.1    31.1    31.1    31.1    31.1    31.1       0       0
       0
        
Pier Skew, UpSta & Num, DnSta & Num=  ,499.09, 4 ,397.2, 4 , 3 , 3 , 0 ,,
       1       1     2.8     2.8
      16   28.09    28.1    31.1
       1       1     2.8     2.8
      16   28.09    28.1    31.1
Pier Skew, UpSta & Num, DnSta & Num=  ,546.8, 4 ,444.91, 4 , 3 , 3 , 0 ,,
       1       1     2.8     2.8
      16   28.09    28.1    31.1
       1       1     2.8     2.8
      16   28.09    28.1    31.1
Pier Skew, UpSta & Num, DnSta & Num=  ,589.55, 4 ,487.66, 4 , 3 , 3 , 0 ,,
       1       1     2.8     2.8
      16   28.09    28.1    31.1
       1       1     2.8     2.8
      16   28.09    28.1    31.1
BR Coef=-1 , 1 , 0 ,1.25, 0 ,,,0.8,0,2,0,
WSPro=,,,, 1 ,,,, 0 ,,,, 0 ,,,,-1 ,-1 ,-1 , 0 , 0 , 0 , 0 , 0
BC Design=,, 0 ,, 0 ,,,,,,
BC Use User HTab Curves=0
BC User HTab FreeFlow(D)= 0

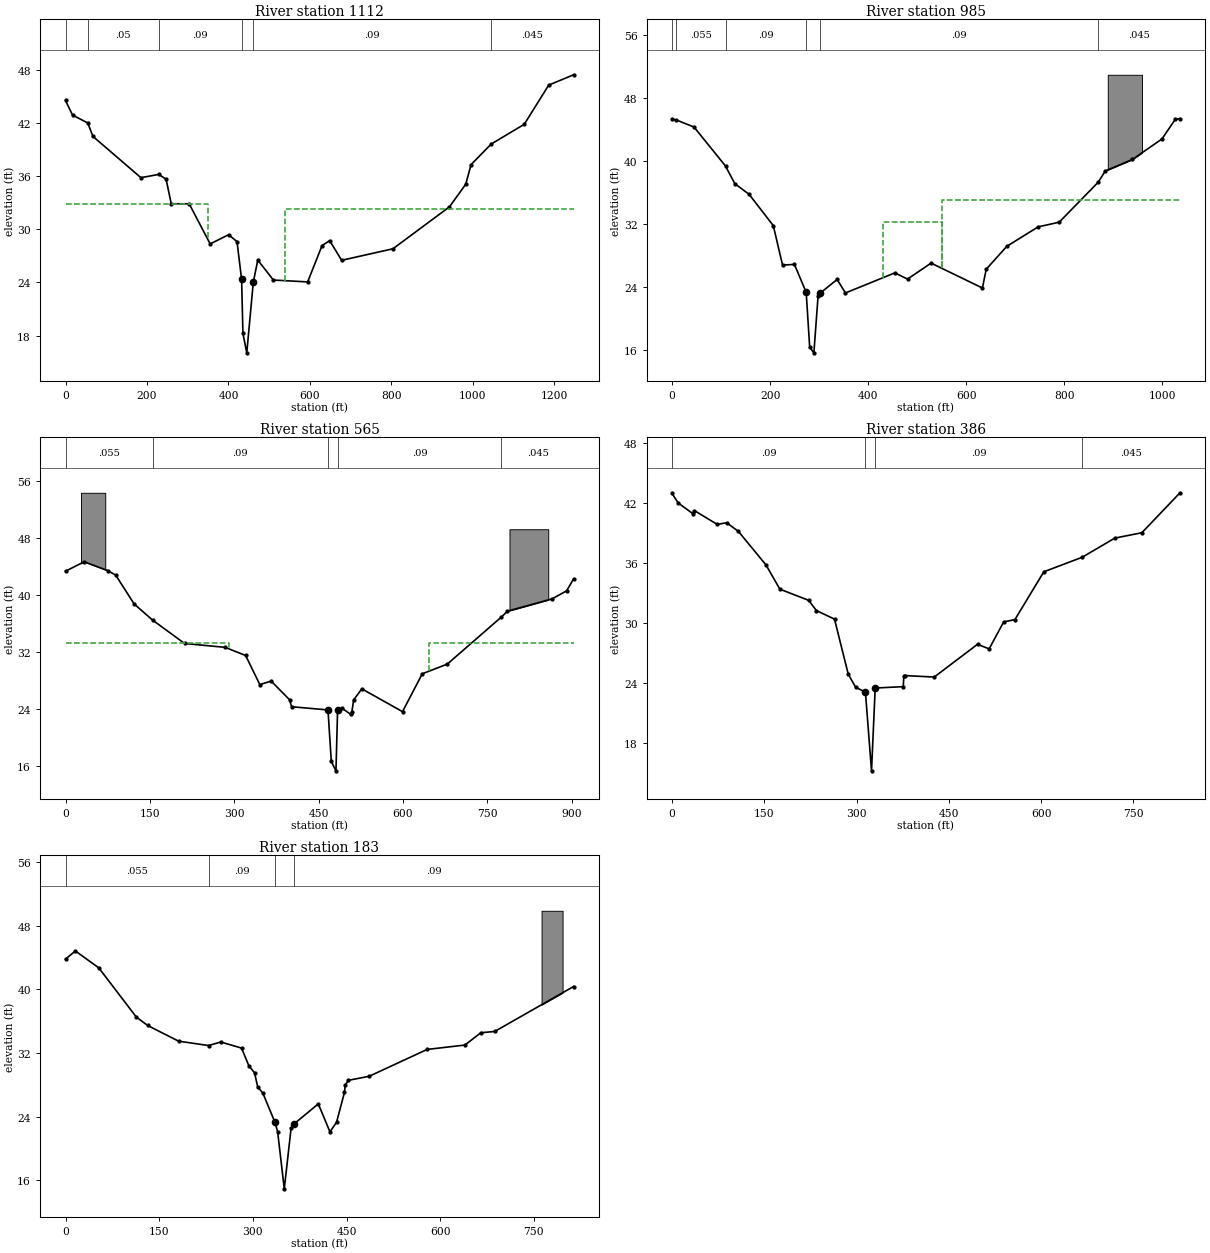
Type RM Length L Ch R = 1 ,1112    ,217.43,126.57,161.14
BEGIN DESCRIPTION:
Survyed Section
END DESCRIPTION:
XS GIS Cut Line= 6
 2418597.7922326 612501.342107492418952.82230005612496.025500014
2419018.60660002612493.6782000062419041.61160004612487.895200014
2419188.92839998612504.6709000022419841.58957887612506.537585124
#Sta/Elev= 30
       0   44.55   17.24    42.9   54.62   42.01   67.36   40.49  185.11   35.83
  228.82    36.2   246.9   35.66 259.517   32.89 303.529   32.88 355.107   28.35
   400.3   29.39 420.957   28.61 432.214   24.35 435.505   18.24 444.913   16.05
 460.869      24 471.888   26.53 510.248   24.27 594.321   24.06   629.7   28.16
  648.33   28.72  677.78    26.5  803.68    27.8  942.47   32.54  982.45    35.1
  995.39    37.3 1044.7139.62283 1126.03   41.86 1185.94   46.28 1246.97   47.45
#Mann= 6 ,-1 , 0
       0    .055       0   54.62     .05       0  228.82     .09       0
 432.214     .05       0 460.869     .09       0 1044.71    .045       0
#XS Ineff= 2 , 0
       0  348.66    32.9  538.66       0   32.28
Permanent Ineff=
       F       F
Bank Sta=432.214,460.869
XS Rating Curve= 0 ,0
Exp/Cntr=0.5,0.3

Type RM Length L Ch R = 1 ,985     ,247.45,420.04,206.23
XS GIS Cut Line= 3
2418858.76211208612788.4703180042419125.73234434 612568.00457783
2419814.68778233 612540.44636032
#Sta/Elev= 30
       0   45.26     8.8   45.18   44.95   44.28  109.17   39.33  128.02    37.1
  157.39   35.73  206.56   31.77  225.43   26.76  249.62   26.84  273.64    23.3
  280.76   16.32  289.31   15.62  297.88   22.86  302.15    23.2  336.68   24.93
  353.66   23.22   454.4   25.77  480.21   24.98  528.25   27.01  632.89   23.85
  640.65   26.23  682.62   29.14  746.56   31.61  789.41    32.2  868.99   37.28
  883.41   38.71  938.81   40.17  998.95   42.77 1025.91   45.24 1035.74   45.36
#Mann= 6 ,-1 , 0
       0    .055       0     8.8    .055       0  109.17     .09       0
  273.64     .05       0  302.15     .09       0  868.99    .045       0
#XS Ineff= 2 ,-1
     430     550    32.2     550    1100      35
Permanent Ineff=
       F       F
#Block Obstruct= 1 ,-1
  888.44  958.26  50.914
Bank Sta=273.64,302.15
XS Rating Curve= 0 ,0
Exp/Cntr=0.3,0.1

Type RM Length L Ch R = 1 ,565     ,149.08,179.16,145.24
XS GIS Cut Line= 3
2419011.79296991612978.7773950992419458.79585181612612.713306651
2419780.71150742612564.885837823
#Sta/Elev= 30
       0   43.31   33.28   44.63   74.81    43.4   89.21   42.76  122.09   38.71
  154.99   36.44  211.67   33.17  283.65   32.63  320.18   31.49  345.49   27.41
  365.69   27.89  398.24   25.29     402    24.3  466.64   23.85  472.55   16.63
  480.86   15.31   483.7   23.79   491.7   24.08  506.96   23.24  509.17   23.63
  512.31   25.26  526.82   26.81  599.15   23.61  634.26   28.92  678.78   30.28
  775.05   36.89  785.72    37.7  865.38   39.44  890.96   40.56  903.22   42.22
#Mann= 5 ,-1 , 0
       0    .055       0  154.99     .09       0  466.64     .05       0
   483.7     .09       0  775.05    .045       0
#XS Ineff= 2 , 0
       0     290    33.2  646.64       0    33.2
Permanent Ineff=
       F       F
#Block Obstruct= 2 ,-1
   27.52   70.66  54.306  789.32  858.24  49.193
Bank Sta=466.64,483.7
XS Rating Curve= 0 ,0
Exp/Cntr=0.3,0.1

Type RM Length L Ch R = 1 ,386     ,187.15,202.82,192.1
XS GIS Cut Line= 3
2419157.11489448613056.0371524542419661.14283533612616.392342702
2419815.66235007612588.799572244
#Sta/Elev= 30
       0   42.96    9.92      42   34.17   40.91   36.34   41.23   73.69   39.84
   88.86   40.01  107.89   39.15  152.88   35.78  175.35   33.36   222.2   32.24
  234.73   31.22  264.19   30.36  286.48   24.86  298.47   23.54  314.47   23.04
  324.36   15.17  330.33   23.46     376    23.6  376.85   24.67   378.1   24.71
   426.3   24.56  496.63   27.84  515.52   27.38  539.17   30.08   557.4   30.31
  604.42    35.1  666.66   36.55  719.73   38.47  763.75   39.01  825.79   43.01
#Mann= 4 ,-1 , 0
       0     .09       0  314.47     .05       0  330.33     .09       0
  666.66    .045       0
Bank Sta=314.47,330.33
XS Rating Curve= 0 ,0
Exp/Cntr=0.3,0.1

Type RM Length L Ch R = 1 ,183     ,275.1,183.21,218.61
XS GIS Cut Line= 2
2419248.02193458613220.789855361 2419859.7753486612684.404415771
#Sta/Elev= 30
       0   43.81   15.88   44.83   53.38    42.7   113.4   36.52   131.6   35.46
  181.07   33.49  229.03   32.94  248.72   33.38  281.94   32.62  293.76   30.37
  302.69   29.53  307.66   27.77  316.07   26.95  335.29   23.31  339.67   22.13
  350.36   14.92  361.23   22.53  366.69   23.13  404.84    25.6  423.47   22.09
  434.02   23.28  446.73   27.04  448.09      28  453.17   28.57  486.21   29.07
   579.1   32.45   639.7      33  665.11   34.55  687.31   34.71   813.6   40.36
#Mann= 4 ,-1 , 0
       0    .055       0  229.03     .09       0  335.29     .05       0
  366.69     .09       0
#Block Obstruct= 1 ,-1
  762.36  796.03  49.885
Bank Sta=335.29,366.69
XS Rating Curve= 0 ,0
Exp/Cntr=0.3,0.1

Chan Stop Cuts=-1
Use User Specified Reach Order=0

--- DTL_Rainbow_Creek.g02 (geometry) ---

Geom Title=DTL_Rainbow_Creeknewxs
Program Version=4.00

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
River Reach=Rainbow_Crk     ,Main