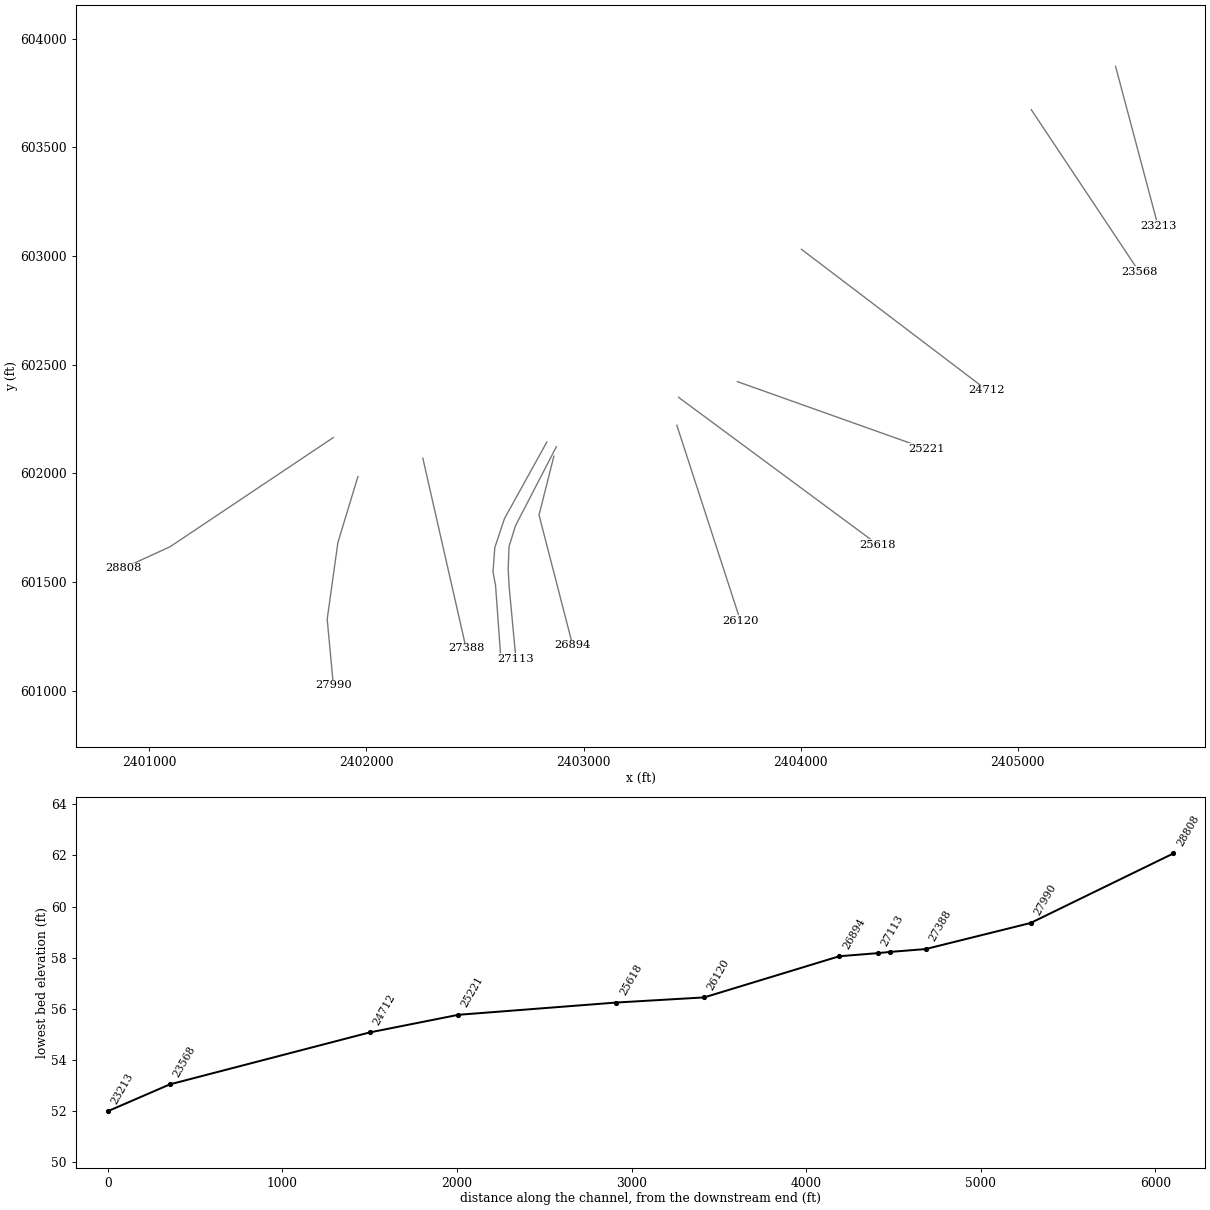
HEC-RAS study DTL_Rainbow_Creek.prj: DTL_Rainbow_Creek

--- DTL_Rainbow_Creek.g02 (geometry) --- (continued)

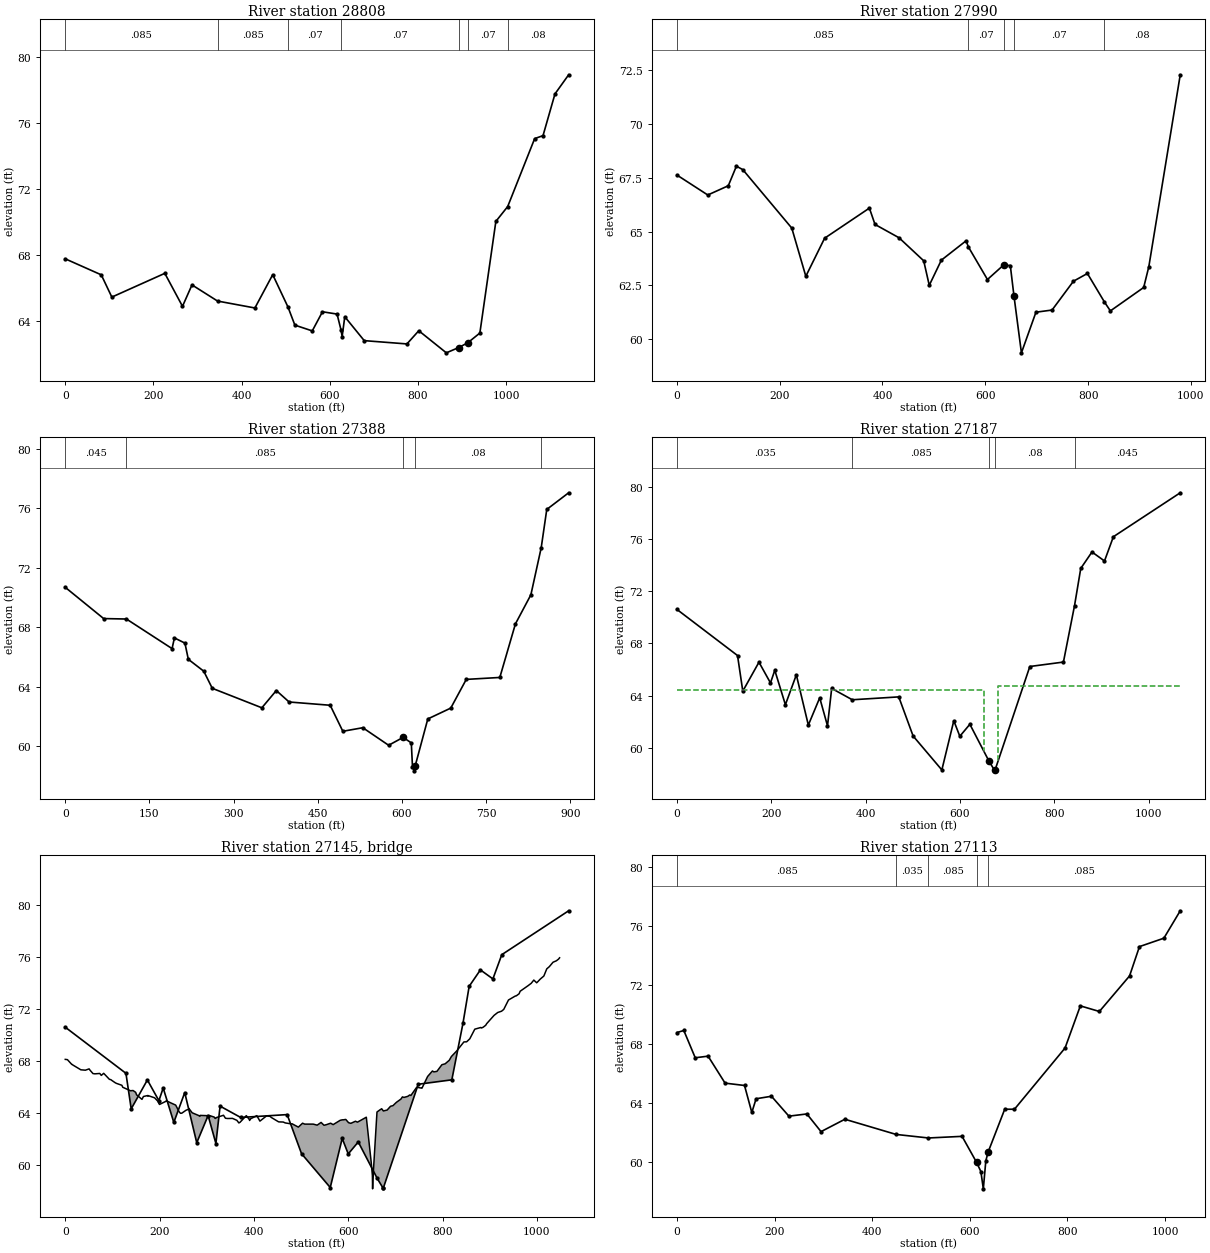
Type RM Length L Ch R = 1 ,28808   ,637.69,818.08,960.25
XS GIS Cut Line= 3
2401847.49999999      602164.6252401095.74999999601662.437500015
2400879.25000004     601563.5625
#Sta/Elev= 30
       0   67.78   81.65   66.81  105.65   65.46  225.82    66.9  265.96    64.9
  287.49    66.2  345.48   65.22  430.22    64.8  470.67   66.82  505.25   64.86
   520.9   63.76  560.37   63.41  583.52   64.57  616.66   64.43  625.74   63.45
  628.18   63.07  634.13   64.27  678.27   62.82  775.16   62.62  802.04   63.42
  864.58   62.08  892.53    62.4   913.2   62.69  940.62   63.28  976.92   70.05
 1003.76   70.95 1064.93   75.07 1083.91   75.25 1111.02   77.78 1142.07   78.94
#Mann= 7 ,-1 , 0
       0    .085       0  345.48    .085       0  505.25     .07       0
  625.74     .07       0  892.53     .05       0   913.2     .07       0
 1003.76     .08       0
Bank Sta=892.53,913.2
XS Rating Curve= 0 ,0
Exp/Cntr=0.3,0.1

Type RM Length L Ch R = 1 ,27990   ,542.37,601.76,614.74
XS GIS Cut Line= 4
      2401960.75         601985.2401868.50000003        601681.5
2401819.25000001     601329.0625      2401847.75601024.187500015
#Sta/Elev= 30
       0   67.63   60.15    66.7  100.06   67.13  115.81   68.04  128.25   67.88
  223.58   65.16  250.89   62.92  287.43   64.69  374.54   66.09  385.48   65.33
  432.27   64.71  480.21   63.64  491.01    62.5  514.52   63.67  562.67   64.57
     567   64.29  604.21   62.77  635.45   63.44  648.69   63.42  655.72   62.02
  670.31   59.36  698.57   61.25  729.89   61.35  771.48   62.69  798.66   63.05
   831.9   61.72  843.37   61.31  908.18    62.4  918.17   63.37  979.28   72.29
#Mann= 5 ,-1 , 0
       0    .085       0     567     .07       0  635.45     .05       0
  655.72     .07       0   831.9     .08       0
Bank Sta=635.45,655.72
XS Rating Curve= 0 ,0
Exp/Cntr=0.3,0.1

Type RM Length L Ch R = 1 ,27388   ,246.62,201.19,199.5
XS GIS Cut Line= 2
2402259.88664448602069.2541101132402459.29126643601194.499373451
#Sta/Elev= 30
       0   70.68    68.4   68.58  109.01   68.55  190.33   66.56  194.53   67.28
  213.25   66.93  219.32   65.84  246.86   65.04  261.99   63.89  350.37   62.58
  376.13   63.74  398.97   62.97  472.16   62.75  494.71      61   530.3   61.24
  576.33   60.06   602.2   60.59  616.74   60.22  618.85   58.61  621.84   58.34
  623.73   58.68  646.14   61.83  687.08   62.56   714.7   64.49   774.5   64.62
  802.28   68.22  829.87   70.18   848.3   73.35  858.18   75.92  897.19   77.04
#Mann= 5 ,-1 , 0
       0    .045       0  109.01    .085       0   602.2     .05       0
  623.73     .08       0   848.3    .045       0
Bank Sta=602.2,623.73
XS Rating Curve= 0 ,0
Exp/Cntr=0.5,0.3

Type RM Length L Ch R = 1 ,27187   ,82.78,73.47,65.4
BEGIN DESCRIPTION:
Survey Section
END DESCRIPTION:
XS GIS Cut Line= 6
2402831.40358599602144.6684958932402635.84499475601791.709087312
2402591.32759188 601658.156878652402583.14129998601547.404499993
2402594.87950002601483.3047000022402619.85276365601138.896898478
#Sta/Elev= 30
       0   70.61  128.64   67.07  139.78   64.34  174.07   66.56  198.49   64.97
  207.62   65.94  230.13    63.3  253.31   65.59  278.75   61.74  302.89   63.83
  319.38   61.68  328.24   64.55  371.95   63.68  470.49    63.9  500.92    60.9
  561.83    58.3  587.18   62.07  599.95   60.88  621.24    61.8   661.4      59
  673.68   58.26  674.08   58.23  748.38   66.23  819.61   66.57  843.17    70.9
  856.36   73.75  880.16   75.01  906.68   74.32  925.54   76.18  1067.3   79.55
#Mann= 5 ,-1 , 0
       0    .035       0  371.95    .085       0   661.4     .05       0
  673.68     .08       0  843.17    .045       0
#XS Ineff= 2 , 0
       0  651.18   64.45  681.44       0   64.74
Permanent Ineff=
       F       F
Bank Sta=661.4,673.68
XS Rating Curve= 0 ,0
Exp/Cntr=0.5,0.3

Type RM Length L Ch R = 3 ,27145   ,,,
Bridge Culvert--1,0,-1,-1, 0
Deck Dist Width WeirC Skew NumUp NumDn MinLoCord MaxHiCord MaxSubmerge Is_Ogee
,,2.6,0, 170, 170, , , 0.98, 0, 0,0,,
       0    4.52   13.87    14.7   15.98   33.01   42.58   50.57   52.47   58.73
   62.81   73.15   76.35   81.47   93.54   96.76   98.08  105.74  108.34  120.03
  121.85   128.1  138.25   143.7  149.26  151.14  162.63  165.71  174.35  175.04
  175.53  189.38   197.2  198.46  199.78  213.93   214.2  223.09   234.1  241.37
  244.23  247.08  256.24  261.62  262.13  269.06  282.85  285.43   286.2  294.59
  307.31  315.74  317.56  318.47  320.99  335.51  339.61  344.45  354.55  363.83
  368.08  370.51  383.86  390.49  390.79  392.03  406.15  412.72  426.67  428.14
  434.51  436.83     452  453.31     462  466.49  478.37   478.8  480.61  494.17
  503.13  507.59  524.68  525.24   525.5  526.82  534.04  542.42  548.57  553.86
  562.66  567.89   579.5  582.76  587.35  589.43  594.73  600.65  605.47   615.3
  619.47  634.81  636.26  638.29  648.54  651.15  651.63   652.2   660.9  667.39
  670.85  674.44  682.43  689.65  694.85  701.99  711.59  714.87  716.26  718.09
  726.07  730.36   732.8  745.12  748.26  755.96  756.36  756.73  768.29  778.48
  781.41     788  798.53  805.42  814.12  818.67  830.24  833.97  845.19  851.05
  857.68  868.28  881.15   882.5  886.07  891.43  893.42  909.17  916.95  925.08
  929.72  939.73  954.43  954.92  956.32  962.28  964.41  980.91  987.87  993.45
  999.48 1002.82 1006.93 1014.71 1020.91  1026.3 1034.18 1041.25 1045.91 1048.05
   68.14   68.12   67.75   67.75   67.71   67.34   67.31   67.41   67.31   67.05
   67.03   67.06   66.91   67.07   66.61   66.58   66.54   66.35    66.3   66.15
      66    65.9   65.73   65.75   65.61   65.42   65.07   65.29   65.36   65.32
   65.36   65.19   64.89   64.76   64.68   64.93   64.97   64.81   64.63   64.12
      64   64.01   64.24   64.31   64.37   64.04   63.83   63.77   63.84   63.83
   63.81   63.71   63.61   63.61   63.68   63.85   63.62    63.6   63.61   63.46
   63.26   63.31   63.82   63.51   63.45   63.56   63.82    63.4    63.8    63.8
   63.76   63.68   63.35   63.34   63.33   63.26   63.19   63.19    63.2   62.94
   63.24   63.17   63.17   63.17   63.17   63.16   63.09    63.3   63.08   63.13
   63.24   63.13   63.38   63.46    63.5    63.5   63.53   63.28   63.23   63.39
   63.32   63.63   63.66    63.7   60.29   59.23    58.2   58.91    64.1   64.27
   64.35   64.18   64.25   64.54   64.59   64.84   65.09   65.26   65.24   65.22
    65.3   65.41   65.37      66   65.98   65.93   65.96   65.96   66.83   67.25
   67.18   67.22   67.73    67.8   68.07   68.36    68.8   68.97   69.48   69.49
   69.72   70.46   70.59   70.55   70.61   70.76   70.88   71.52   71.74   71.84
   71.98    72.7   73.01   73.01   73.02   73.18   73.37   73.79   73.98   74.23
   74.02   74.14    74.3   74.54   75.09   75.26    75.6   75.71   75.84   75.94
                                                                                
                                                                                
                                                                                
                                                                                
                                                                                
                                                                                
                                                                                
                                                                                
                                                                                
                                                                                
                                                                                
                                                                                
                                                                                
                                                                                
                                                                                
                                                                                
                                                                                
       0    4.52   13.87    14.7   15.98   33.01   42.58   50.57   52.47   58.73
   62.81   73.15   76.35   81.47   93.54   96.76   98.08  105.74  108.34  120.03
  121.85   128.1  138.25   143.7  149.26  151.14  162.63  165.71  174.35  175.04
  175.53  189.38   197.2  198.46  199.78  213.93   214.2  223.09   234.1  241.37
  244.23  247.08  256.24  261.62  262.13  269.06  282.85  285.43   286.2  294.59
  307.31  315.74  317.56  318.47  320.99  335.51  339.61  344.45  354.55  363.83
  368.08  370.51  383.86  390.49  390.79  392.03  406.15  412.72  426.67  428.14
  434.51  436.83     452  453.31     462  466.49  478.37   478.8  480.61  494.17
  503.13  507.59  524.68  525.24   525.5  526.82  534.04  542.42  548.57  553.86
  562.66  567.89   579.5  582.76  587.35  589.43  594.73  600.65  605.47   615.3
  619.47  634.81  636.26  638.29  648.54  651.15  651.63   652.2   660.9  667.39
  670.85  674.44  682.43  689.65  694.85  701.99  711.59  714.87  716.26  718.09
  726.07  730.36   732.8  745.12  748.26  755.96  756.36  756.73  768.29  778.48
  781.41     788  798.53  805.42  814.12  818.67  830.24  833.97  845.19  851.05
  857.68  868.28  881.15   882.5  886.07  891.43  893.42  909.17  916.95  925.08
  929.72  939.73  954.43  954.92  956.32  962.28  964.41  980.91  987.87  993.45
  999.48 1002.82 1006.93 1014.71 1020.91  1026.3 1034.18 1041.25 1045.91 1048.05
   68.14   68.12   67.75   67.75   67.71   67.34   67.31   67.41   67.31   67.05
   67.03   67.06   66.91   67.07   66.61   66.58   66.54   66.35    66.3   66.15
      66    65.9   65.73   65.75   65.61   65.42   65.07   65.29   65.36   65.32
   65.36   65.19   64.89   64.76   64.68   64.93   64.97   64.81   64.63   64.12
      64   64.01   64.24   64.31   64.37   64.04   63.83   63.77   63.84   63.83
   63.81   63.71   63.61   63.61   63.68   63.85   63.62    63.6   63.61   63.46
   63.26   63.31   63.82   63.51   63.45   63.56   63.82    63.4    63.8    63.8
   63.76   63.68   63.35   63.34   63.33   63.26   63.19   63.19    63.2   62.94
   63.24   63.17   63.17   63.17   63.17   63.16   63.09    63.3   63.08   63.13
   63.24   63.13   63.38   63.46    63.5    63.5   63.53   63.28   63.23   63.39
   63.32   63.63   63.66    63.7   60.29   59.23    58.2   58.91    64.1   64.27
   64.35   64.18   64.25   64.54   64.59   64.84   65.09   65.26   65.24   65.22
    65.3   65.41   65.37      66   65.98   65.93   65.96   65.96   66.83   67.25
   67.18   67.22   67.73    67.8   68.07   68.36    68.8   68.97   69.48   69.49
   69.72   70.46   70.59   70.55   70.61   70.76   70.88   71.52   71.74   71.84
   71.98    72.7   73.01   73.01   73.02   73.18   73.37   73.79   73.98   74.23
   74.02   74.14    74.3   74.54   75.09   75.26    75.6   75.71   75.84   75.94
                                                                                
                                                                                
                                                                                
                                                                                
                                                                                
                                                                                
                                                                                
                                                                                
                                                                                
                                                                                
                                                                                
                                                                                
                                                                                
                                                                                
                                                                                
                                                                                
                                                                                
BR Coef=-1 , 0 , 0 ,, 0 ,,,0.8,-1,,0,
WSPro=,,,, 1 ,,,, 0 ,,,, 0 ,,,,-1 ,-1 ,-1 , 0 , 0 , 0 , 0 , 0
BC Design=,, 0 ,, 0 ,,,,,,
BC Use User HTab Curves=0
BC User HTab FreeFlow(D)= 0

Type RM Length L Ch R = 1 ,27113   ,145.68,219,209.67
BEGIN DESCRIPTION:
Survyed Section
END DESCRIPTION:
XS GIS Cut Line= 6
2402875.03287666602122.652006894  2402686.628868601758.960724384
2402656.81810716601662.3738591972402653.04349999601559.568399996
2402657.51389998601476.8875000182402688.75172023601145.697478309
#Sta/Elev= 30
       0   68.78   14.26   68.92   37.63   67.07   63.96   67.18   98.74   65.35
  138.57   65.19  153.52   63.36  162.28   64.29  193.78   64.46  229.48   63.11
  266.32   63.26  295.29   62.06  344.16    62.9  449.12   61.87  515.32   61.63
  584.17   61.74  613.99   59.97  622.72   59.35   627.7   58.18  632.82   60.08
   637.7   60.69  671.52   63.58  691.47   63.58  795.08   67.73  826.42   70.59
  865.39   70.21  927.22   72.62  947.49   74.61  997.51   75.18 1031.05   77.04
#Mann= 5 ,-1 , 0
       0    .085       0  449.12    .035       0  515.32    .085       0
  613.99     .05       0   637.7    .085       0
#XS Ineff= 2 , 0
       0  610.18   59.05  640.41       0   59.05
Permanent Ineff=
       F       F
Bank Sta=613.99,637.7
XS Rating Curve= 0 ,0
Exp/Cntr=0.5,0.3

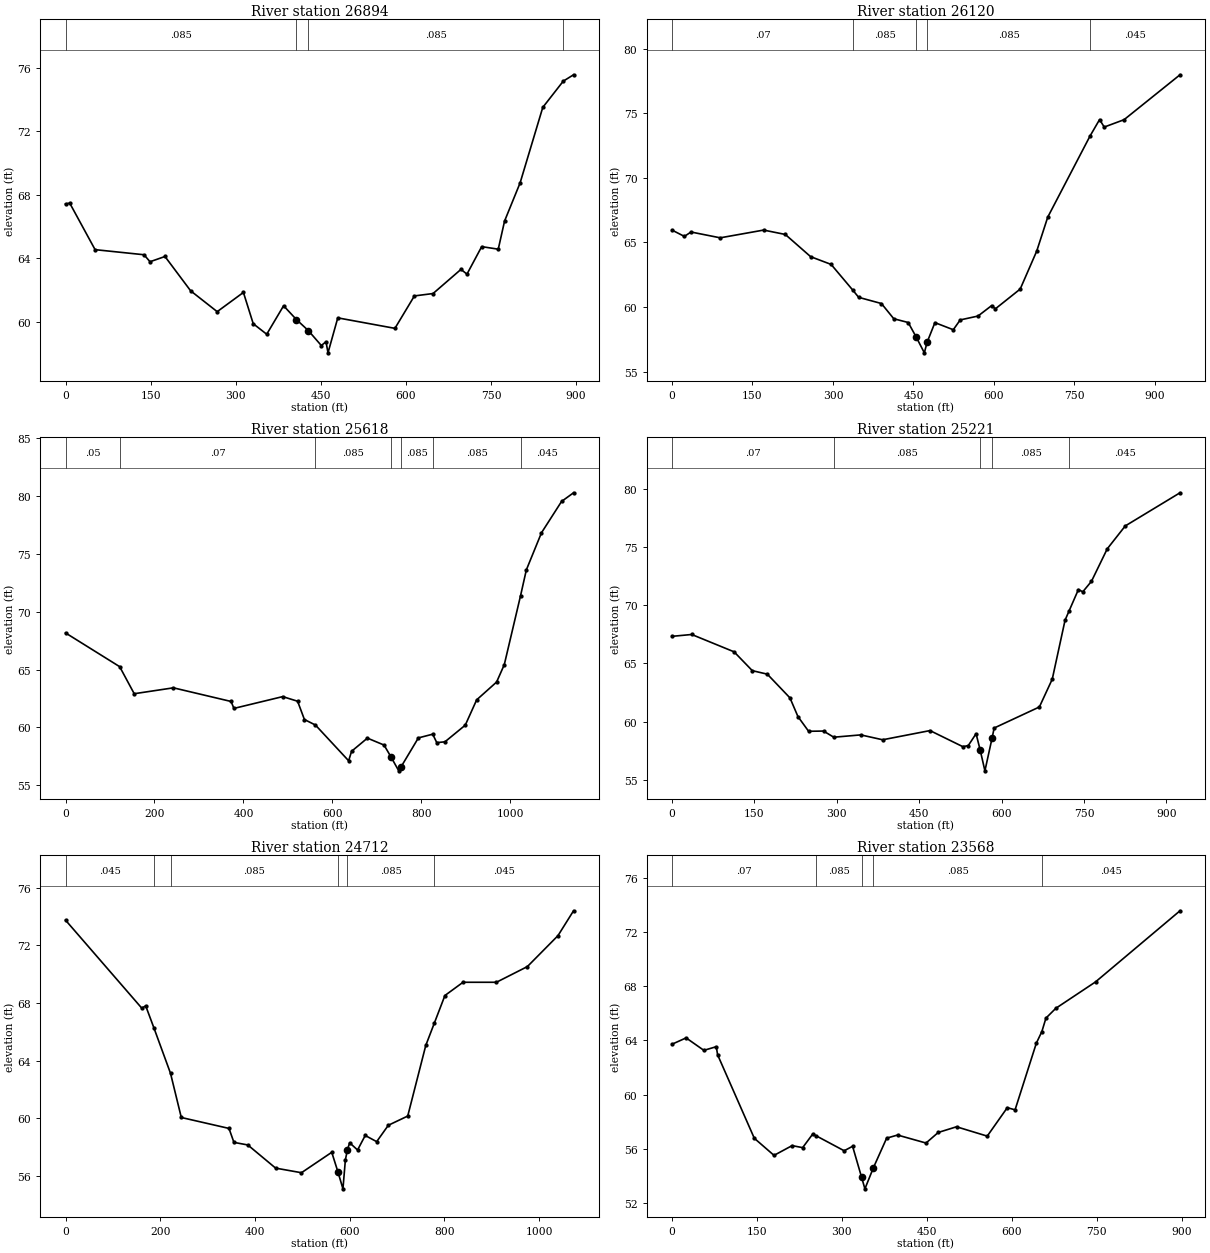
Type RM Length L Ch R = 1 ,26894   ,758.44,774.48,753.16
XS GIS Cut Line= 3
2402863.50802089602078.7527172272402795.02212751601808.233438537
2402949.85302062601209.863887176
#Sta/Elev= 30
       0   67.42     7.4   67.48   52.15   64.55  138.39   64.23  148.96   63.79
  175.33   64.12   220.6   61.96  267.37   60.65  313.59   61.86  330.91   59.89
  354.67   59.23   384.4   61.02  407.12   60.15  428.02   59.46  450.91   58.52
  459.18   58.76  462.67   58.06  479.92   60.26  580.65    59.6  614.97   61.64
  647.86   61.79  697.07   63.31  707.63   63.01  733.57   64.74  762.78   64.58
  773.91   66.35  801.29   68.75  841.27    73.5  877.39   75.15  895.49   75.55
#Mann= 4 ,-1 , 0
       0    .085       0  407.12     .05       0  428.02    .085       0
  877.39    .045       0
Bank Sta=407.12,428.02
XS Rating Curve= 0 ,0
Exp/Cntr=0.3,0.1

Type RM Length L Ch R = 1 ,26120   ,392.7,502.34,536.57
XS GIS Cut Line= 2
2403429.83366296602221.4796081782403722.98785119601321.372382373
#Sta/Elev= 30
       0   65.96   23.13   65.47   35.48   65.81   89.92   65.36  170.82   65.96
   211.2   65.62  258.35    63.9  296.51    63.3  337.48   61.28  347.83   60.75
  390.26   60.27  413.33   59.09  440.19    58.8  455.24   57.66  470.26   56.45
   475.4   57.27  489.93   58.79  524.16   58.24  537.11      59  570.23    59.3
  595.65   60.11  602.63   59.86  648.84   61.39  679.63   64.33  700.16   66.96
   778.9   73.24  796.76   74.52  805.44   73.94  842.37   74.51  946.64   77.99
#Mann= 5 ,-1 , 0
       0     .07       0  337.48    .085       0  455.24     .05       0
   475.4    .085       0   778.9    .045       0
Bank Sta=455.24,475.4
XS Rating Curve= 0 ,0
Exp/Cntr=0.3,0.1

Type RM Length L Ch R = 1 ,25618   ,885.2,905.47,886.61
XS GIS Cut Line= 2
2403437.82575417602349.7306472962404356.43882959 601671.37022239
#Sta/Elev= 30
       0   68.18  121.73   65.26  154.43   62.92  242.54   63.43  372.15   62.25
  378.59   61.65  488.22   62.67  521.68   62.27  536.98   60.69  561.83   60.21
  636.42   57.12  642.99   57.94  678.58   59.08  715.96   58.48  731.64   57.45
  749.06   56.25  754.48   56.61  793.17    59.1  825.39   59.42  834.47   58.69
  852.87   58.76  898.55    60.2  924.18   62.39  968.98   63.93  986.24   65.43
 1022.83    71.4 1035.84   73.63 1069.86   76.84 1115.01   79.55 1141.94    80.3
#Mann= 7 ,-1 , 0
       0     .05       0  121.73     .07       0  561.83    .085       0
  731.64     .05       0  754.48    .085       0  825.39    .085       0
 1022.83    .045       0
Bank Sta=731.64,754.48
XS Rating Curve= 0 ,0
Exp/Cntr=0.3,0.1

Type RM Length L Ch R = 1 ,25221   ,543.66,508.5,483.05
XS GIS Cut Line= 2
2403708.80392537602421.8717917952404580.00862552602112.201874688
#Sta/Elev= 30
       0   67.33   35.93   67.49  113.03      66  146.21   64.38  173.52   64.08
  214.73   62.04   229.3   60.43  248.68   59.17  275.77   59.19  294.49   58.66
  343.58   58.86  383.43   58.44  469.62   59.23  529.25   57.85  539.25   57.94
  553.44   58.96  561.05   57.53  569.53   55.77  582.59   58.59  586.35   59.45
  668.66   61.26  692.09   63.65  715.39   68.72  722.76   69.52  739.65   71.35
  747.69   71.16  763.44   72.06  792.14   74.85  824.95   76.82   924.6   79.67
#Mann= 5 ,-1 , 0
       0     .07       0  294.49    .085       0  561.05     .05       0
  582.59    .085       0  722.76    .045       0
Bank Sta=561.05,582.59
XS Rating Curve= 0 ,0
Exp/Cntr=0.3,0.1

Type RM Length L Ch R = 1 ,24712   ,1095.85,1143.88,1031.37
XS GIS Cut Line= 2
2404003.75524269603030.7503249352404858.44421399602382.507965073
#Sta/Elev= 30
       0   73.76  161.05   67.64  169.34    67.8  186.65   66.27  221.73   63.11
  244.49   60.04  345.19   59.28  355.61   58.31  384.92   58.13  443.67   56.52
  498.19    56.2  562.17   57.62   575.3   56.25  585.81   55.08  590.96    57.1
  595.36   57.81  599.98   58.28  616.69   57.78  632.83   58.79  657.01   58.36
  681.66    59.5  722.58   60.14  760.71   65.05  779.11   66.63  801.14   68.52
  839.33   69.44  909.85   69.44  975.19   70.53 1039.81   72.68 1072.71   74.41
#Mann= 6 ,-1 , 0
       0    .045       0  186.65     .07       0  221.73    .085       0
   575.3     .05       0  595.36    .085       0  779.11    .045       0
Bank Sta=575.3,595.36
XS Rating Curve= 0 ,0
Exp/Cntr=0.3,0.1

Type RM Length L Ch R = 1 ,23568   ,357.57,355.58,285.16
XS GIS Cut Line= 2
 2405062.5931886603673.0045595472405560.05750018602926.808092117
#Sta/Elev= 30
       0   63.72   24.94   64.19   56.31   63.27   78.21   63.54   80.57   62.94
  145.37   56.78  180.14   55.52  212.08   56.24  230.65   56.09  248.22   57.08
   253.8   56.98  303.98   55.86  318.84   56.19  334.69   53.91  340.58   53.05
  355.59   54.61  378.95   56.79  398.23   57.02  448.46   56.43  469.99   57.21
   502.3   57.63  556.53   56.94  591.93   59.04  605.65   58.88  643.21    63.8
  652.97   64.66  660.17   65.65   677.5   66.37  747.66   68.32  896.82   73.57
#Mann= 5 ,-1 , 0
       0     .07       0   253.8    .085       0  334.69     .05       0
  355.59    .085       0  652.97    .045       0
Bank Sta=334.69,355.59
XS Rating Curve= 0 ,0
Exp/Cntr=0.3,0.1

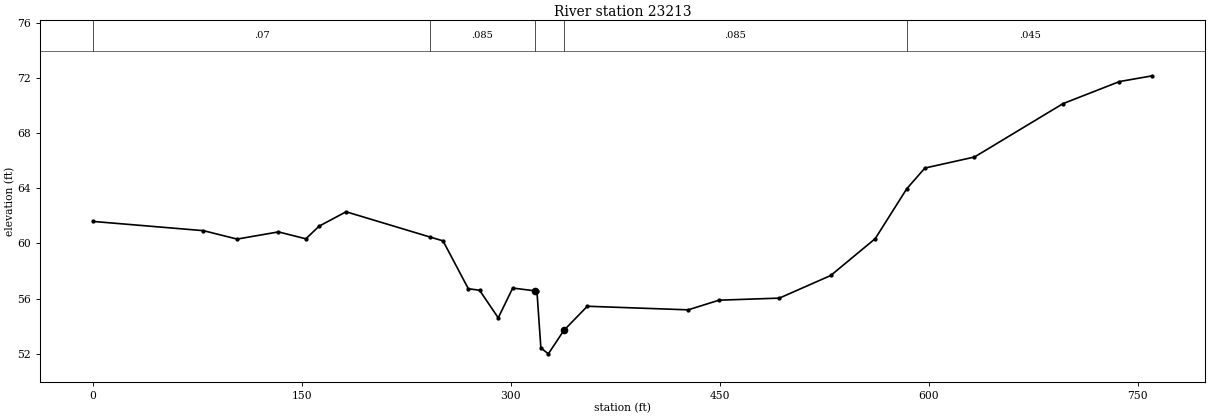
Type RM Length L Ch R = 1 ,23213   ,352.31,397.01,431.13
XS GIS Cut Line= 2
2405450.76609841603872.7440180182405646.73688781603137.853557676
#Sta/Elev= 30
       0    61.6   79.24   60.93  103.39   60.32   133.1   60.84  152.75   60.34
  162.34   61.26  181.66    62.3  241.86   60.47  251.24   60.19  269.41   56.72
  277.49   56.61  290.89   54.61  301.29   56.77  317.01   56.57  318.66   56.55
  321.49   52.43  326.86      52     338    53.7  354.85   55.45  427.28   55.19
  449.37   55.89   492.7   56.04   529.6   57.68  561.53   60.35  584.19   63.97
   597.2   65.47   632.8   66.27  696.36   70.14  736.87   71.74  760.57   72.16
#Mann= 5 ,-1 , 0
       0     .07       0  241.86    .085       0  317.01     .05       0
     338    .085       0  584.19    .045       0
Bank Sta=317.01,338
XS Rating Curve= 0 ,0
Exp/Cntr=0.3,0.1