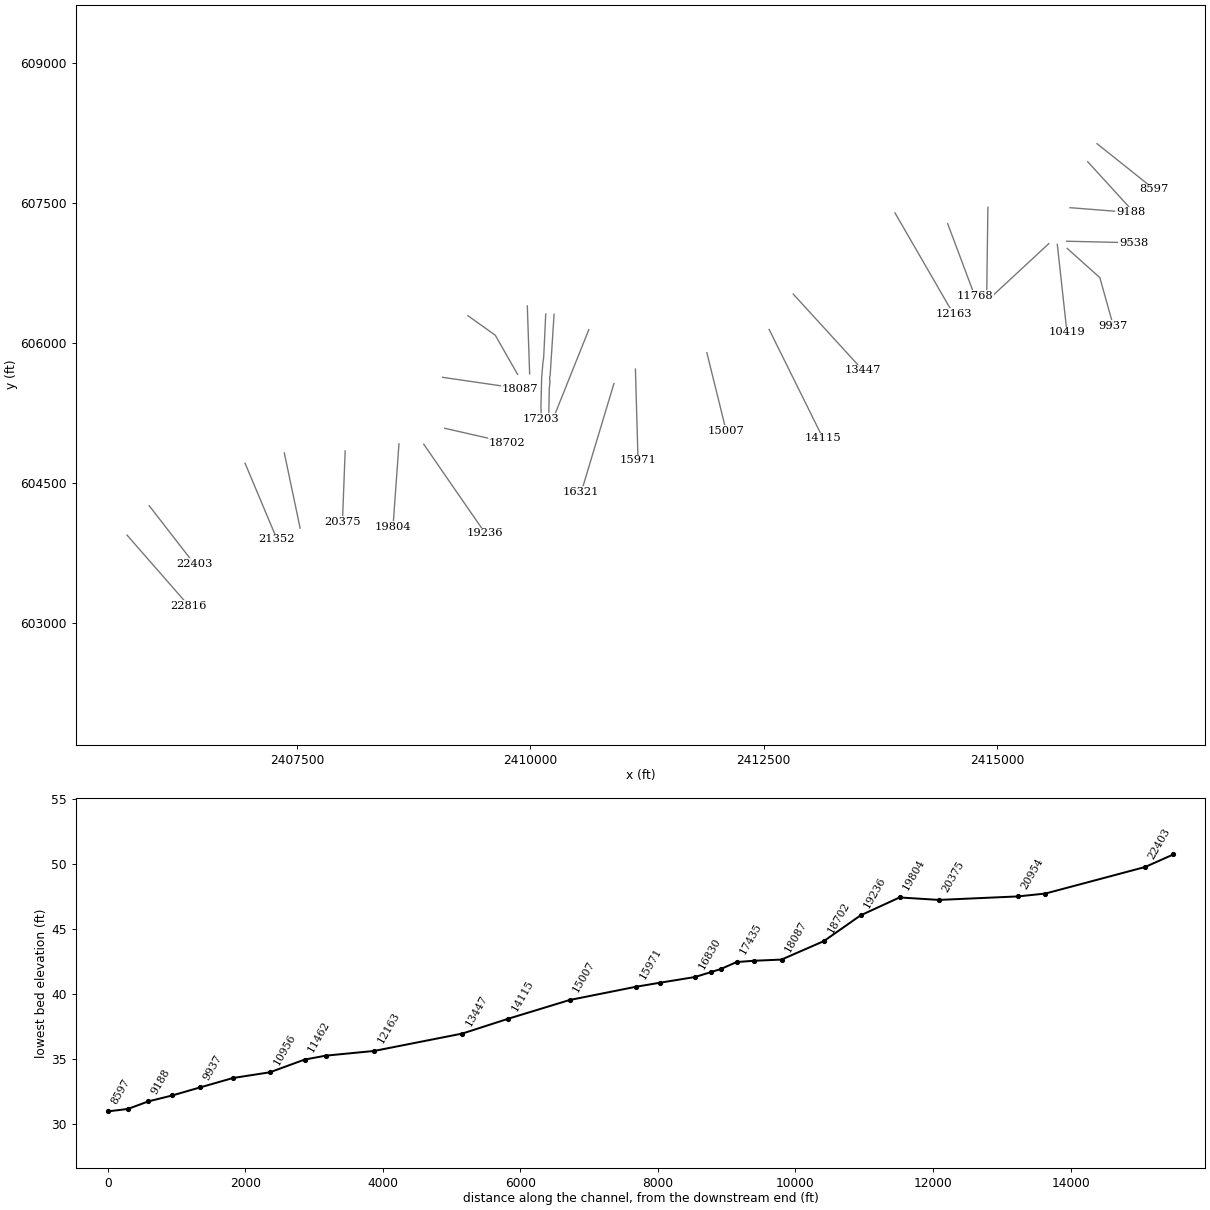
HEC-RAS study DTL_Rainbow_Creek.prj: DTL_Rainbow_Creek

--- DTL_Rainbow_Creek.g02 (geometry) --- (continued)

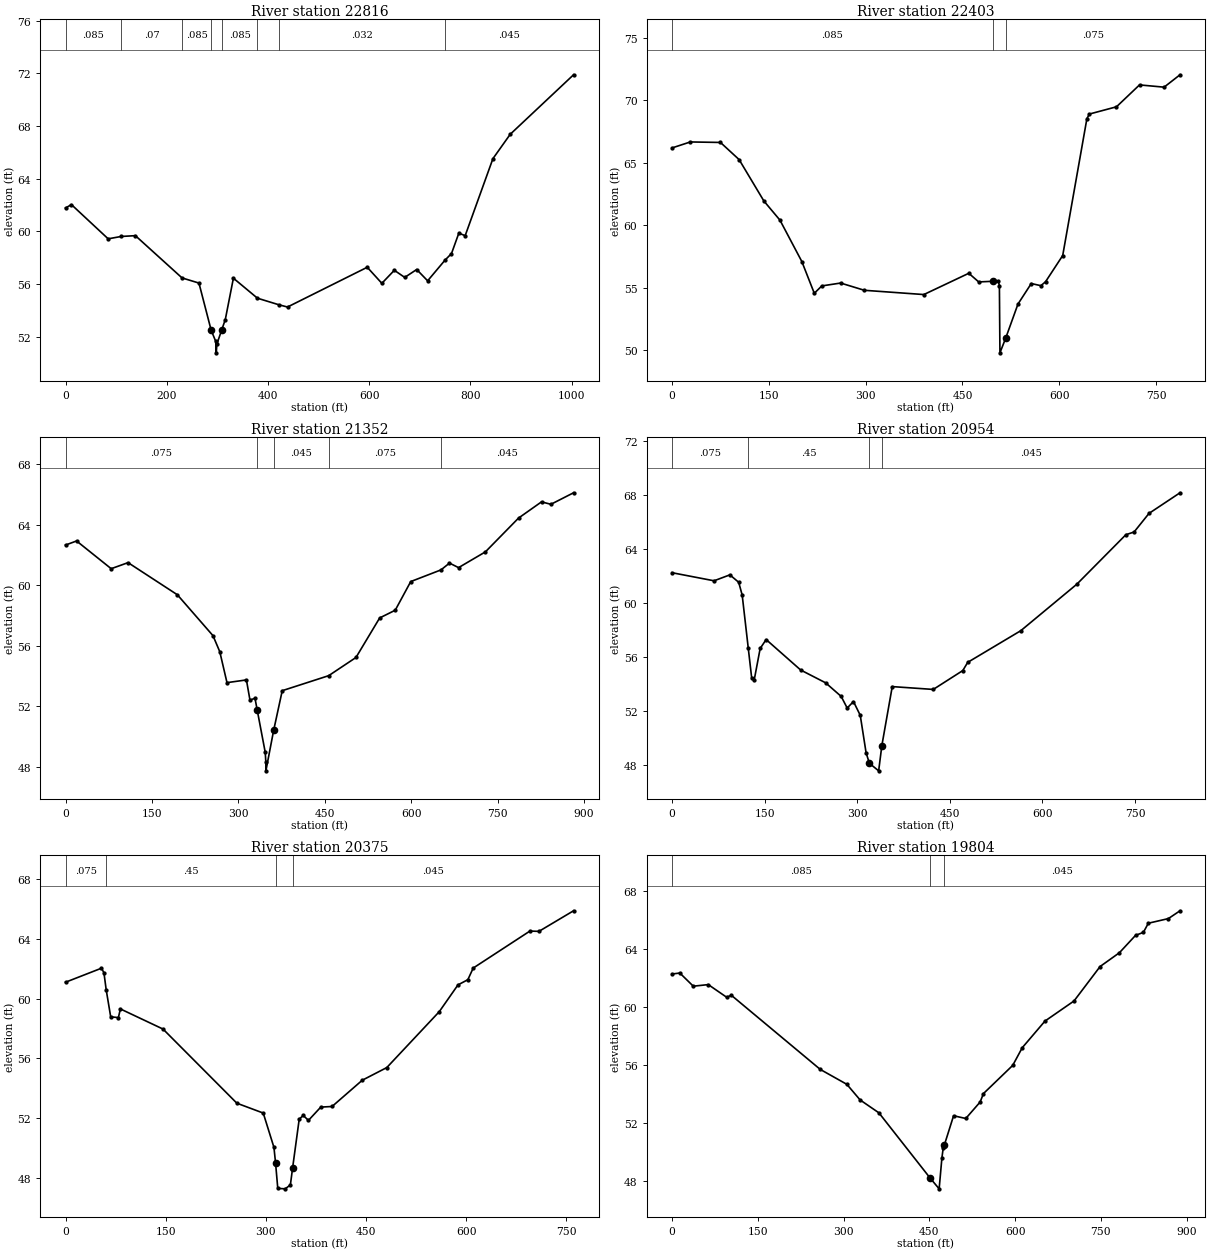
Type RM Length L Ch R = 1 ,22816   ,367.97,412.9,366.32
XS GIS Cut Line= 2
2405680.10172741603943.2443474082406340.73088397603187.649749622
#Sta/Elev= 30
       0   61.76   11.68   62.02   84.27   59.42   110.1    59.6  138.07   59.66
  230.24   56.45  263.63   56.06  287.65   52.49  296.75   51.63  297.84   50.76
  299.06   51.43  308.53   52.49  315.69   53.29  331.68   56.43  379.19   54.91
  421.64   54.41  438.57   54.24  596.11   57.26  624.96   56.04   649.6   57.03
  670.15   56.49  693.81   57.09  715.41   56.23  749.94   57.81  762.54    58.3
  777.04   59.85  789.57   59.66  844.39   65.51  878.57   67.36 1003.67   71.88
#Mann= 8 ,-1 , 0
       0    .085       0   110.1     .07       0  230.24    .085       0
  287.65     .05       0  308.53    .085       0  379.19    .045       0
  421.64    .032       0  749.94    .045       0
Bank Sta=287.65,308.53
XS Rating Curve= 0 ,0
Exp/Cntr=0.3,0.1

Type RM Length L Ch R = 1 ,22403   ,1435.87,1448.58,1372.31
XS GIS Cut Line= 2
 2405918.0810578604257.1482588052406400.47069328603635.317869291
#Sta/Elev= 30
       0   66.17   28.47   66.65   75.13   66.61     104   65.24  142.37   61.93
  167.25    60.4  201.16   57.09  220.48   54.55  232.08   55.14  261.28   55.37
  298.05   54.79  390.18   54.45  459.79   56.15  475.16   55.46  497.15   55.51
  505.47   55.53  507.21   55.16  508.04   49.79  517.14   50.99  535.98   53.69
  556.58   55.33  571.45   55.16  578.65   55.47  605.29   57.57  642.72    68.5
  646.56   68.88  688.59   69.46  724.26   71.21  762.36   71.03     787   72.02
#Mann= 3 ,-1 , 0
       0    .085       0  497.15     .05       0  517.14    .075       0
Bank Sta=497.15,517.14
XS Rating Curve= 0 ,0
Exp/Cntr=0.3,0.1

Type RM Length L Ch R = 1 ,21352   ,387.78,397.68,355.75
XS GIS Cut Line= 2
2406944.42583422604712.1192834972407286.10791473603899.124701187
#Sta/Elev= 30
       0   62.65    19.2   62.92    79.3   61.09  108.58   61.49  194.14   59.37
     256   56.67  267.82   55.61  280.31   53.57  314.04   53.75  320.19   52.42
  328.91   52.54  332.82   51.75   346.7   48.97  347.76   48.32  347.84   47.75
   361.3   50.42  376.22   53.04  456.81   54.03  504.19   55.23  545.34   57.84
  572.37   58.35  599.26   60.24  651.71   61.01  666.55   61.46  682.27   61.16
  728.86    62.2  786.38   64.43  826.25    65.5  842.61   65.34  881.88    66.1
#Mann= 5 ,-1 , 0
       0    .075       0  332.82     .05       0   361.3    .045       0
  456.81    .075       0  651.71    .045       0
Bank Sta=332.82,361.3
XS Rating Curve= 0 ,0
Exp/Cntr=0.3,0.1

Type RM Length L Ch R = 1 ,20954   ,1162.38,1150.52,1108.14
XS GIS Cut Line= 2
2407364.70607662604822.7069120852407533.99229802604017.565127537
#Sta/Elev= 30
       0   62.23   68.13   61.63   93.77   62.07  108.06   61.52  113.71   60.57
  123.58   56.62  129.11   54.41  133.09   54.25  142.83   56.61  152.51   57.27
  208.44   55.01  248.87   54.06  274.06   53.05  283.73   52.19  293.93   52.67
  304.91   51.65  314.37   48.87  319.7248.08851  334.72   47.53  339.88    49.4
  356.72   53.78  423.14   53.57  470.96   54.97  478.97   55.58  564.97   57.93
  655.73   61.38  735.09   65.05  748.37   65.25  772.53   66.63  822.75   68.16
#Mann= 4 ,-1 , 0
       0    .075       0  123.58     .45       0  319.72     .05       0
  339.88    .045       0
Bank Sta=319.72,339.88
XS Rating Curve= 0 ,0
Exp/Cntr=0.3,0.1

Type RM Length L Ch R = 1 ,20375   ,562.53,571.76,556.6
XS GIS Cut Line= 2
2408016.57748406604844.1379567682407987.08035386604083.789483532
#Sta/Elev= 30
       0   61.11   53.82   62.05   57.55   61.75   60.95    60.6   67.69   58.79
   79.19   58.74    82.2   59.32  146.07   57.97  256.68      53  296.16   52.34
  312.18   50.04  314.56   49.02  317.93   47.29  328.98   47.26   336.8   47.52
  340.13   48.66  350.03   51.93  356.02   52.18  363.88   51.85  382.35   52.74
  399.22   52.78  444.44   54.54  481.23   55.39  559.86   59.14   587.8   60.93
   602.6   61.28  610.64   62.06  695.58   64.54  709.09   64.52  760.92    65.9
#Mann= 4 ,-1 , 0
       0    .075       0   60.95     .45       0  314.56     .05       0
  340.13    .045       0
Bank Sta=314.56,340.13
XS Rating Curve= 0 ,0
Exp/Cntr=0.3,0.1

Type RM Length L Ch R = 1 ,19804   ,491.08,567.3,665.2
XS GIS Cut Line= 2
2408592.65896751 604920.148708062408529.06496504604034.080856442
#Sta/Elev= 30
       0   62.29   13.71   62.36   37.27   61.45    63.5   61.56   95.48   60.69
  103.92   60.82  259.32    55.7  305.81   54.67  329.01   53.59  361.86    52.7
   451.9   48.17  467.18   47.45  471.98   49.58  474.39    50.3  476.15   50.46
  492.41    52.5  513.74   52.31  538.89   53.45  544.61   54.03  595.85   55.98
  612.49    57.2  652.22   59.04  703.04   60.43  748.63   62.81  782.34   63.76
  810.55   64.96  824.31   65.17  832.97    65.8     868   66.12  888.35   66.66
#Mann= 3 ,-1 , 0
       0    .085       0   451.9     .05       0  476.15    .045       0
Bank Sta=451.9,476.15
XS Rating Curve= 0 ,0
Exp/Cntr=0.3,0.1

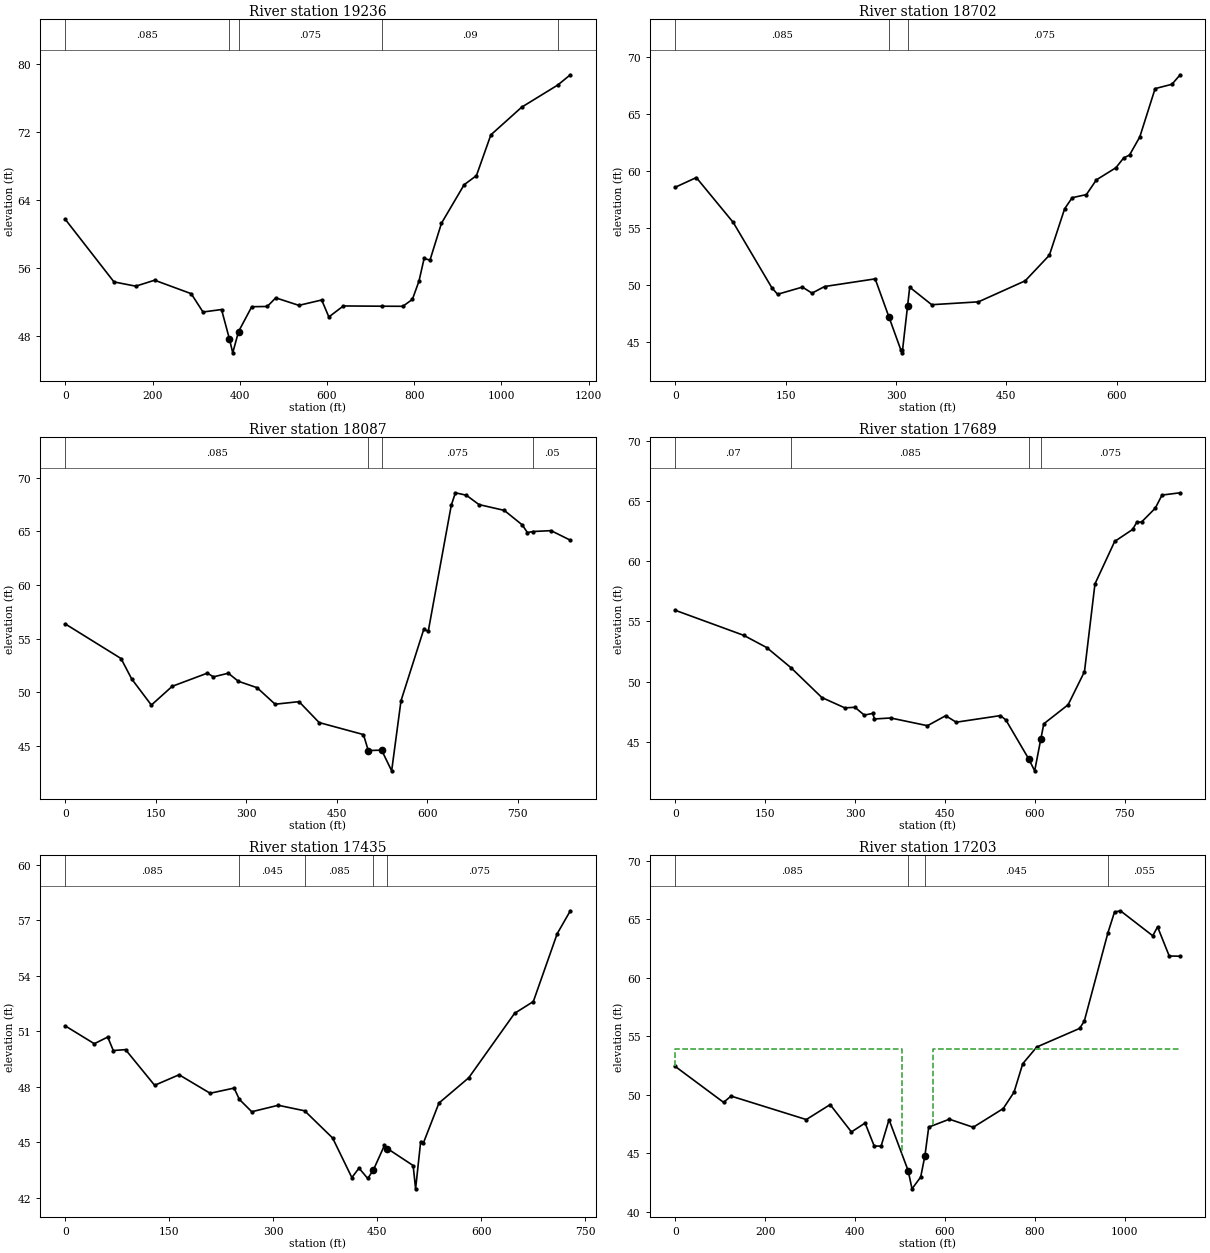
Type RM Length L Ch R = 1 ,19236   ,479.6,533.9,675.32
XS GIS Cut Line= 3
2408857.64289917604916.6653385912409181.43625712604446.974079296
2409515.87976764603963.889008552
#Sta/Elev= 30
       0   61.72  111.52   54.39  161.43   53.89  204.73   54.59  288.58   53.01
  315.64   50.86  358.16   51.15  376.25    47.7  383.88   46.07  397.21   48.57
  427.48   51.48  463.02   51.51  482.52   52.52  535.54   51.64  587.84   52.27
  604.28   50.28  637.56   51.57  726.44   51.54   773.9   51.53  795.84   52.34
     811   54.49  822.72   57.14  836.22   56.95  862.49   61.27   914.5   65.79
  942.71   66.86   975.8   71.64 1046.52   74.89 1129.32   77.49 1158.04   78.69
#Mann= 5 ,-1 , 0
       0    .085       0  376.25     .05       0  397.21    .075       0
  726.44     .09       0 1129.32    .045       0
Bank Sta=376.25,397.21
XS Rating Curve= 0 ,0
Exp/Cntr=0.3,0.1

Type RM Length L Ch R = 1 ,18702   ,554.8,615.19,582.18
XS GIS Cut Line= 2
2409082.34188363605086.9585746822409751.22890466604934.188082233
#Sta/Elev= 30
       0   58.57   28.68   59.42   78.93   55.49  131.16    49.8   139.1   49.21
  172.84   49.84  185.94   49.31  202.94   49.89  271.71   50.56  290.57    47.2
  306.57   44.35  308.38   44.34  308.47   44.09  315.68   48.16  318.65   49.83
  348.51    48.3  412.03   48.55  475.58   50.39   508.4   52.63  529.13   56.69
  539.39   57.66  558.67   57.93   572.3   59.22  598.82   60.28  609.24   61.13
  617.29   61.39  631.22   62.97  652.07    67.2  674.93   67.58  686.11   68.41
#Mann= 3 ,-1 , 0
       0    .085       0  290.57     .05       0  315.68    .075       0
Bank Sta=290.57,315.68
XS Rating Curve= 0 ,0
Exp/Cntr=0.3,0.1

Type RM Length L Ch R = 1 ,18087   ,547.77,397.95,335.13
XS GIS Cut Line= 2
2409060.72517282605632.249430686  2409888.845349605511.673312232
#Sta/Elev= 30
       0   56.36   92.25   53.14   109.9   51.24  142.52    48.8   177.1   50.55
  235.46   51.78  245.35   51.43   270.1   51.77  286.65   51.02  317.76   50.42
  347.64   48.88  387.24   49.12   420.6   47.17  494.03   46.05  502.03   44.56
  524.12    44.6  540.75   42.67  556.23    49.2  593.95   55.86   601.4   55.68
  639.52   67.42  646.41   68.59  664.54   68.36  685.49   67.49  727.31   66.95
  757.09    65.6  765.78   64.88  775.01   64.98  804.91   65.06  836.85   64.17
#Mann= 4 ,-1 , 0
       0    .085       0  502.03     .05       0  524.12    .075       0
  775.01     .05       0
Bank Sta=502.03,524.12
XS Rating Curve= 0 ,0
Exp/Cntr=0.3,0.1

Type RM Length L Ch R = 1 ,17689   ,386.28,254.55,237.33
XS GIS Cut Line= 3
2409330.07781738606292.6067854022409623.89825925 606083.38984862
2409862.71007483605665.009086683
#Sta/Elev= 30
       0   55.92  114.19   53.84  152.74   52.82  193.09   51.15  244.66   48.67
  283.05   47.81  299.82   47.86  315.45   47.21   329.5   47.35  332.39   46.89
  359.52   46.97   420.9   46.33  451.27   47.16  468.79   46.62   542.7   47.17
  551.74    46.8  589.45    43.6  599.74   42.58  610.01   45.24  614.99   46.49
  655.52   48.07  682.79   50.82   700.3   58.11  733.23   61.64  763.02   62.63
  770.17   63.24  778.01   63.25  800.91    64.4  812.16   65.49  842.44   65.68
#Mann= 4 ,-1 , 0
       0     .07       0  193.09    .085       0  589.45     .05       0
  610.01    .075       0
Bank Sta=589.45,610.01
XS Rating Curve= 0 ,0
Exp/Cntr=0.3,0.1

Type RM Length L Ch R = 1 ,17435   ,419.17,231.94,192.41
XS GIS Cut Line= 2
2409967.13026378606396.7778408532409992.15234438605668.961669162
#Sta/Elev= 30
       0   51.29   41.75   50.33   61.12   50.69   69.12   49.96   86.79   50.01
  128.76   48.08     164   48.65  208.79   47.65  243.34   47.93  250.95   47.32
  268.82   46.65  307.01      47  345.12    46.7  385.43   45.23  413.17   43.09
   423.5    43.6   436.1   43.04  444.08   43.49  460.19   44.83  464.33   44.66
  501.57   43.74   505.1   42.48  512.45   45.04  516.46   44.97  538.77   47.12
  581.82   48.49   647.8   51.97  674.88   52.61  709.31   56.28  728.25   57.52
#Mann= 5 ,-1 , 0
       0    .085       0  250.95    .045       0  345.12    .085       0
  444.08     .05       0  464.33    .075       0
Bank Sta=444.08,464.33
XS Rating Curve= 0 ,0
Exp/Cntr=0.5,0.5

Type RM Length L Ch R = 1 ,17203   ,120.97,134.08,123.8
BEGIN DESCRIPTION:
Survyed Section
END DESCRIPTION:
XS GIS Cut Line= 6
2410164.35109229606310.4311983292410142.99310005605854.376800016
2410134.27040003605785.4819000072410120.75940001605629.336800009
2410113.28228657605330.1455883092410116.37022449605189.335620135
#Sta/Elev= 30
       0   52.42  107.72   49.34  124.22   49.88  291.68   47.87  344.71   49.15
  392.06   46.81  422.48   47.57  442.81    45.6  458.15    45.6  475.76   47.86
  518.24    43.5  526.88   41.94  546.19   42.95  555.65   44.79  564.01   47.22
  609.94    47.9  663.04   47.21  729.78   48.81  753.78   50.21  773.22   52.65
  804.45   54.08  899.72   55.67  910.09   56.29   962.9   63.88  977.38   65.63
  990.55   65.74 1062.44    63.6 1073.17   64.36  1099.1   61.87 1123.44   61.85
#Mann= 4 ,-1 , 0
       0    .085       0  518.24     .05       0  555.65    .045       0
   962.9    .055       0
#XS Ineff= 2 , 0
       0  504.09   53.89  574.09       0   53.91
Permanent Ineff=
       F       F
Bank Sta=518.24,555.65
XS Rating Curve= 0 ,0
Exp/Cntr=0.5,0.3

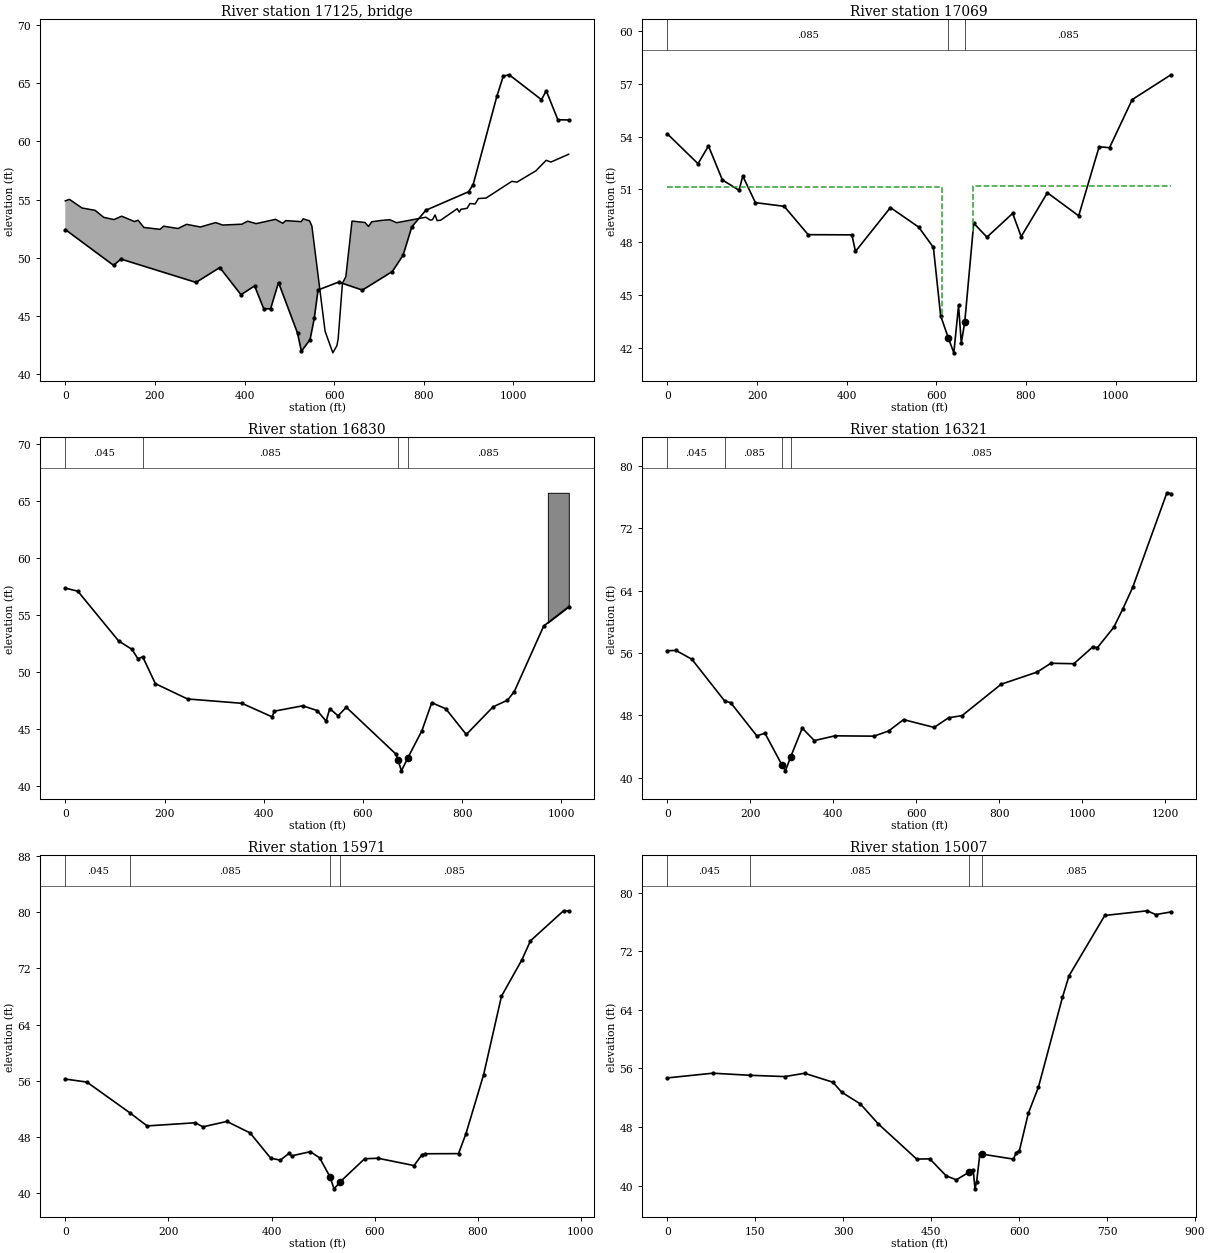
Type RM Length L Ch R = 3 ,17125   ,,,
Bridge Culvert--1,0,-1,-1, 0
Deck Dist Width WeirC Skew NumUp NumDn MinLoCord MaxHiCord MaxSubmerge Is_Ogee
,,2.6,0, 60, 60, , , 0.98, 0, 0,0,,
       0    9.22   37.16    66.7   85.85  108.55  125.83  154.34   162.5  175.44
   211.5  219.33  251.49  270.55  301.57  335.43  351.09  393.75  406.89  425.83
   469.2  485.12  492.07  526.28   530.8  545.02  550.27  579.67  597.02  606.08
  608.87  618.42  626.03  639.78  668.63  676.52  683.84  704.03  723.94  739.12
  804.66  814.36  819.41  825.08  829.72  837.33  874.43  879.13   882.6  896.56
  902.93  914.43  921.78  938.86  996.38 1007.78 1050.22 1072.99 1083.67 1123.17
   54.89   55.02   54.28   54.07   53.47   53.28   53.57   53.11   53.22    52.6
   52.44   52.71   52.51   52.87   52.64   53.02   52.81   52.88   53.14   52.93
    53.3   52.96   53.19    53.1   53.34   53.17   52.72   43.67   41.81   42.43
   43.01    47.8   48.37   53.15   53.03   52.69   53.09    53.2   53.27   53.01
   53.48   53.23   53.27   53.68   53.19   53.22   54.21   53.92   54.16   54.25
   54.66   54.62   55.09   55.13   56.57    56.5   57.48   58.38   58.23    58.9
                                                                                
                                                                                
                                                                                
                                                                                
                                                                                
                                                                                
       0    9.22   37.16    66.7   85.85  108.55  125.83  154.34   162.5  175.44
   211.5  219.33  251.49  270.55  301.57  335.43  351.09  393.75  406.89  425.83
   469.2  485.12  492.07  526.28   530.8  545.02  550.27  579.67  597.02  606.08
  608.87  618.42  626.03  639.78  668.63  676.52  683.84  704.03  723.94  739.12
  804.66  814.36  819.41  825.08  829.72  837.33  874.43  879.13   882.6  896.56
  902.93  914.43  921.78  938.86  996.38 1007.78 1050.22 1072.99 1083.67 1123.17
   54.89   55.02   54.28   54.07   53.47   53.28   53.57   53.11   53.22    52.6
   52.44   52.71   52.51   52.87   52.64   53.02   52.81   52.88   53.14   52.93
    53.3   52.96   53.19    53.1   53.34   53.17   52.72   43.67   41.81   42.43
   43.01    47.8   48.37   53.15   53.03   52.69   53.09    53.2   53.27   53.01
   53.48   53.23   53.27   53.68   53.19   53.22   54.21   53.92   54.16   54.25
   54.66   54.62   55.09   55.13   56.57    56.5   57.48   58.38   58.23    58.9
                                                                                
                                                                                
                                                                                
                                                                                
                                                                                
                                                                                
BR Coef=-1 , 0 , 0 ,, 0 ,,,0.8,-1,,0,
WSPro=,,,, 1 ,,,, 0 ,,,, 0 ,,,,-1 ,-1 ,-1 , 0 , 0 , 0 , 0 , 0
BC Design=,, 0 ,, 0 ,,,,,,
BC Use User HTab Curves=0
BC User HTab FreeFlow(D)= 0

Type RM Length L Ch R = 1 ,17069   ,234.94,238.43,249.66
BEGIN DESCRIPTION:
Survyed Section
END DESCRIPTION:
XS GIS Cut Line= 6
2410253.74533829606308.2708852592410211.50350001605650.969400018
2410206.09010002605636.659300014    2410209.4505605580.657700017
2410202.61889999605514.9722999932410195.86747016605188.500733241
#Sta/Elev= 30
       0   54.15   68.21   52.46   91.51   53.47  122.48   51.54  159.84   50.95
  168.05   51.76  196.22   50.25   260.5   50.04  313.98   48.43  411.45   48.42
  419.56   47.48   497.5   49.97  560.54   48.86  593.35   47.71   609.6   43.82
  626.66   42.57  638.98   41.72  649.52   44.41  655.65   42.27   663.4   43.48
  683.38   49.08  712.85   48.29  770.22   49.64  789.24   48.32  847.73   50.81
  917.56    49.5  963.15   53.42  986.36   53.37  1036.9    56.1 1123.45   57.51
#Mann= 3 ,-1 , 0
       0    .085       0  626.66     .05       0   663.4    .085       0
#XS Ineff= 2 , 0
       0  611.59   51.14  681.59       0   51.18
Permanent Ineff=
       F       F
Bank Sta=626.66,663.4
XS Rating Curve= 0 ,0
Exp/Cntr=0.5,0.3

Type RM Length L Ch R = 1 ,16830   ,485,509.26,513.78
XS GIS Cut Line= 2
2410625.87616551606142.5896740562410248.51236367605200.481423974
#Sta/Elev= 30
       0   57.37   25.24    57.1  107.58   52.73   134.6   51.99  146.37   51.17
  156.09   51.34  181.61   48.98  246.36   47.64  355.84   47.26  416.89   46.07
  421.48   46.57  478.65   47.04   507.8   46.62  525.78   45.69  533.14   46.79
  549.85   46.16   566.4   46.91  666.96   42.78  670.33    42.3  677.64   41.33
  690.72   42.49  719.02   44.87  738.65   47.31  766.95   46.78   808.3   44.52
  862.43   46.95  891.33   47.53  904.97   48.28  964.42   54.05 1014.88   55.74
#Mann= 4 ,-1 , 0
       0    .045       0  156.09    .085       0  670.33     .05       0
  690.72    .085       0
#Block Obstruct= 1 ,-1
  972.69 1014.88  65.739
Bank Sta=670.33,690.72
XS Rating Curve= 0 ,0
Exp/Cntr=0.3,0.1

Type RM Length L Ch R = 1 ,16321   ,312.13,350.02,378.92
XS GIS Cut Line= 2
2410894.94313195605565.9147131892410544.93510592604404.075712442
#Sta/Elev= 30
       0    56.3   20.59   56.33   58.73   55.21  138.21   49.83  152.41   49.64
   215.4   45.37   234.9   45.72  276.54   41.58  284.28   40.89  296.92   42.68
  324.79   46.37  354.08   44.77  403.43   45.38  497.57   45.34  532.94      46
  568.91   47.46  642.68   46.46  677.56    47.7  709.94   47.97  804.22      52
  890.86   53.56  923.99   54.69   979.5   54.63 1025.24    56.8 1036.12   56.69
 1075.69   59.31 1097.37   61.65 1121.37   64.45 1203.65   76.56 1213.42   76.46
#Mann= 4 ,-1 , 0
       0    .045       0  138.21    .085       0  276.54     .05       0
  296.92    .085       0
Bank Sta=276.54,296.92
XS Rating Curve= 0 ,0
Exp/Cntr=0.3,0.1

Type RM Length L Ch R = 1 ,15971   ,892.63,964.09,933.81
XS GIS Cut Line= 2
2411125.01715527605720.2618795482411153.02111627604744.123810321
#Sta/Elev= 30
       0   56.23   41.87    55.8  125.39   51.41  158.76   49.55  252.16      50
  266.95   49.42  313.38   50.19  358.46   48.55  398.42   44.95  417.13   44.67
   434.1   45.65  439.01   45.28  475.34   45.88  493.29      45  513.17   42.33
  521.34   40.58  533.19   41.58  580.65   44.87  606.53   44.94   676.4    43.9
  691.58   45.42  697.88   45.58   762.7    45.6  777.01   48.42  811.43   56.87
     846   68.04  885.61   73.23  902.25   75.94   966.4   80.22  976.54   80.19
#Mann= 4 ,-1 , 0
       0    .045       0  125.39    .085       0  513.17     .05       0
  533.19    .085       0
Bank Sta=513.17,533.19
XS Rating Curve= 0 ,0
Exp/Cntr=0.3,0.1

Type RM Length L Ch R = 1 ,15007   ,830.97,892.41,872.59
XS GIS Cut Line= 2
2411890.01579897605896.2292914542412096.29373817605062.548448116
#Sta/Elev= 30
       0   54.71    77.2   55.35  141.5355.06309  200.01   54.89  233.85   55.34
  282.15   54.12  297.27   52.75  329.09   51.15  359.73   48.42  425.03   43.63
  447.55   43.65  475.31   41.34  492.63   40.79  514.61   41.84   521.5   42.17
  524.54   39.56  527.38   40.56  532.88   44.32  535.73   44.31  590.14   43.62
  594.93   44.51  600.26   44.76  615.57   49.89  632.75   53.44  673.69   65.69
  684.94   68.65  745.96   76.89  818.41   77.53  832.72   77.01  858.82   77.37
#Mann= 4 ,-1 , 0
       0    .045       0  141.53    .085       0  514.61     .05       0
  535.73    .085       0
Bank Sta=514.61,535.73
XS Rating Curve= 0 ,0
Exp/Cntr=0.3,0.1

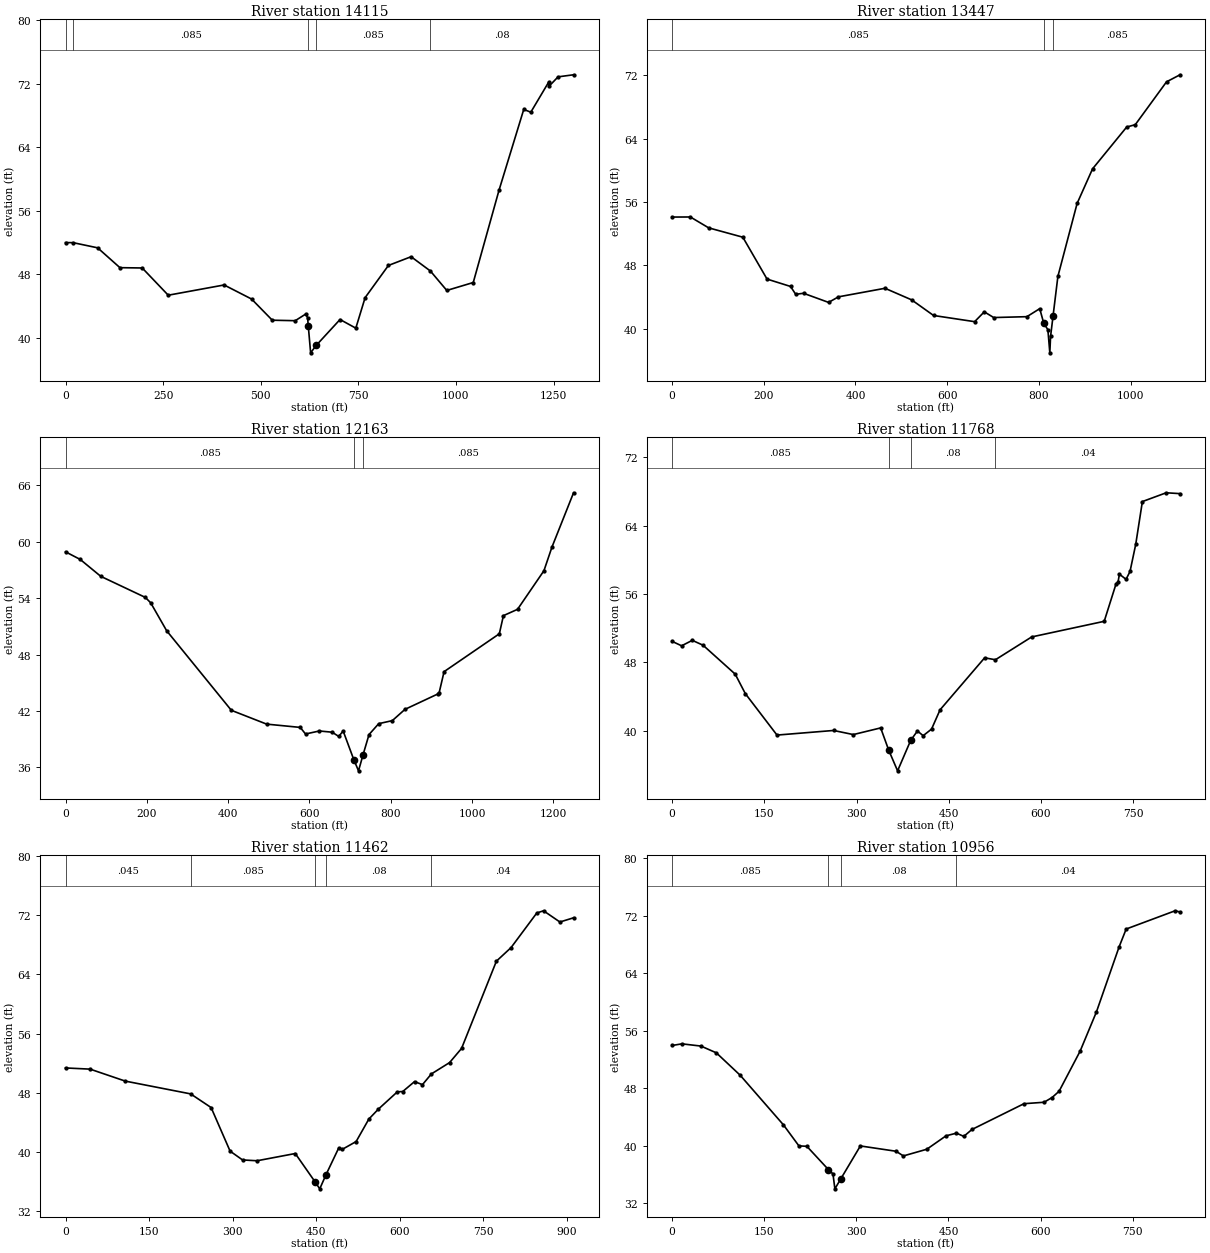
Type RM Length L Ch R = 1 ,14115   ,621.14,667.26,666.91
XS GIS Cut Line= 2
2412556.93782727606145.1921830182413134.69482045 604979.26816085
#Sta/Elev= 30
       0   52.01   19.52      52   82.26   51.35   139.4   48.85  196.55   48.81
  263.13   45.38  406.22   46.67  476.53    44.9  529.63   42.23  588.38   42.17
  615.36   43.01  620.06   42.54  621.72   41.56  627.81   38.12  642.15   39.06
  703.13   42.32  743.56   41.23  767.33   45.07  827.08   49.13  885.14   50.23
  934.54   48.43  976.58   45.98 1044.35   46.98 1110.29    58.6 1173.63   68.78
 1191.82   68.44 1237.47   72.22 1238.86   71.73 1261.59   72.89 1301.22   73.15
#Mann= 5 ,-1 , 0
       0    .045       0   19.52    .085       0  621.72     .05       0
  642.15    .085       0  934.54     .08       0
Bank Sta=621.72,642.15
XS Rating Curve= 0 ,0
Exp/Cntr=0.3,0.1

Type RM Length L Ch R = 1 ,13447   ,1285.39,1284.56,1228.22
XS GIS Cut Line= 2
2412814.89661813606523.8269901872413562.23335151605706.298408955
#Sta/Elev= 30
       0    54.1   40.15   54.11   79.95   52.74  154.48   51.56  207.27   46.28
  258.52   45.35  269.73   44.36  286.78   44.49  341.41   43.34  362.92   44.04
  464.42   45.12  522.53   43.66  570.31   41.69  659.87   40.91   680.9   42.15
  701.43   41.43  773.84   41.54  801.79   42.55  810.68   40.69  819.56    39.9
   823.8   36.98  825.45   39.06  830.84   41.62  841.39   46.62   883.3   55.82
  916.97   60.18  991.36   65.45 1010.12   65.75 1078.22   71.15 1107.64   72.04
#Mann= 3 ,-1 , 0
       0    .085       0  810.68     .05       0  830.84    .085       0
Bank Sta=810.68,830.84
XS Rating Curve= 0 ,0
Exp/Cntr=0.3,0.1

Type RM Length L Ch R = 1 ,12163   ,739.61,700.96,647.57
XS GIS Cut Line= 2
2413904.81728354607393.2063632312414530.16570377606311.142804652
#Sta/Elev= 30
       0   58.94   36.15   58.13   86.77   56.33  196.36   54.09  209.48   53.52
  248.87   50.54  407.92   42.08  494.76   40.61  577.44   40.26  590.43   39.56
  624.51   39.88  655.98   39.75  672.18    39.3  683.01   39.88  709.12   36.84
  720.79   35.64  732.11   37.37  746.65    39.5  770.51   40.66  803.93   40.98
  835.05   42.18  915.55   43.81  919.21   43.96  931.24   46.19 1067.21   50.22
 1077.26   52.15 1111.95   52.82 1176.94   56.93 1196.62   59.44 1249.77   65.22
#Mann= 3 ,-1 , 0
       0    .085       0  709.12     .05       0  732.11    .085       0
Bank Sta=709.12,732.11
XS Rating Curve= 0 ,0
Exp/Cntr=0.3,0.1

Type RM Length L Ch R = 1 ,11768   ,342.41,306.26,285.68
XS GIS Cut Line= 2
2414469.49021208607276.4819980862414759.62369774606503.182329044
#Sta/Elev= 30
       0   50.46   15.64   49.93   33.05   50.57    50.5      50  102.81   46.61
  119.22   44.33  170.73   39.47  262.76   40.01  294.82   39.53  339.29   40.31
  352.42   37.69  366.79   35.28  388.11   38.85  399.04   39.95  408.37    39.4
     422   40.17  435.85   42.43  508.27   48.52  525.8748.29815   584.8   50.97
   702.7    52.8  722.14   57.23   725.1   57.38  727.47   58.32  738.21   57.72
  744.66   58.64  753.95   61.82  764.75   66.83  803.47   67.86  825.94   67.76
#Mann= 4 ,-1 , 0
       0    .085       0  352.42     .05       0  388.11     .08       0
  525.87     .04       0
Bank Sta=352.42,388.11
XS Rating Curve= 0 ,0
Exp/Cntr=0.3,0.1

Type RM Length L Ch R = 1 ,11462   ,538.08,506.13,417.57
XS GIS Cut Line= 2
2414900.00739348607452.8367415672414887.62059681606540.342719093
#Sta/Elev= 30
       0   51.34   44.16   51.18  107.29   49.56  224.68   47.83  261.46   45.98
  295.55   40.08  317.93   38.89  343.99   38.78  412.57   39.76  447.71   35.97
  456.52   34.98  467.79    36.9  490.27   40.46  496.88   40.32  521.86   41.38
  544.67   44.42  561.41   45.74  595.89   48.11  605.55   48.15  626.67   49.49
  640.94   49.08  656.97   50.53  689.71   52.07  711.15   53.98  773.71   65.79
  800.05   67.63  846.24   72.31  858.34   72.61  887.74   71.09  912.24   71.66
#Mann= 5 ,-1 , 0
       0    .045       0  224.68    .085       0  447.71     .05       0
  467.79     .08       0  656.97     .04       0
Bank Sta=447.71,467.79
XS Rating Curve= 0 ,0
Exp/Cntr=0.3,0.1

Type RM Length L Ch R = 1 ,10956   ,359.6,536.95,572.17
XS GIS Cut Line= 2
2415552.42566112607063.8778522912414946.04106921606501.735913038
#Sta/Elev= 30
       0   53.95   16.23   54.18   47.15   53.87   72.18   52.93  111.02   49.81
  181.46    42.9  206.58   39.98  219.53   39.92  254.51   36.69  262.02   36.08
  265.14      34  274.77   35.39  306.62   39.97  364.75   39.23  376.62   38.58
  414.75   39.51  446.06   41.38  463.04   41.75  474.97    41.3  488.18   42.26
   572.9   45.85   605.6   46.05  618.66   46.71  630.05   47.58  664.27   53.16
  690.83   58.62  727.67   67.66  739.23   70.16  818.89    72.7  826.87   72.53
#Mann= 4 ,-1 , 0
       0    .085       0  254.51     .05       0  274.77     .08       0
  463.04     .04       0
Bank Sta=254.51,274.77
XS Rating Curve= 0 ,0
Exp/Cntr=0.3,0.1

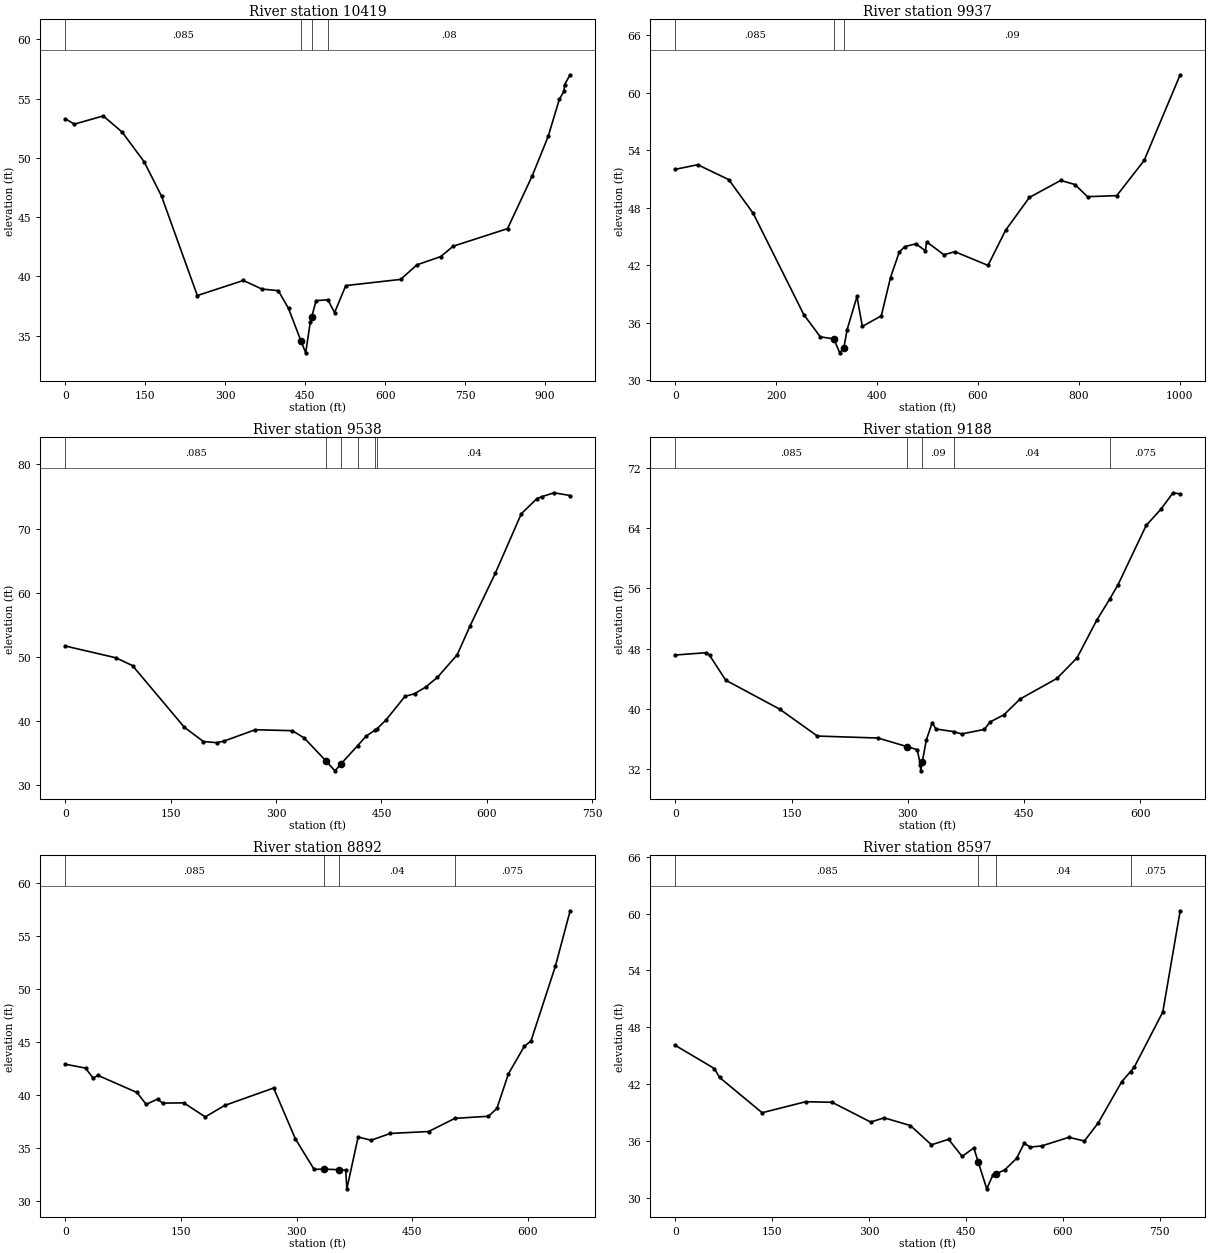
Type RM Length L Ch R = 1 ,10419   ,287.93,481.67,426.92
XS GIS Cut Line= 2
2415643.21519461607056.4592476342415746.43850029606115.062699571
#Sta/Elev= 30
       0   53.29   16.97   52.84   71.11   53.53  106.54   52.17  147.81   49.67
  180.41   46.77  247.59   38.39     334   39.66  368.62   38.94  399.54    38.8
  418.68    37.3  441.98   34.57  450.88   33.56  459.43   36.13  462.34   36.61
  470.44   37.96  492.55   38.03  505.09   36.95  526.12   39.23  628.96   39.75
  659.67   40.98  704.09   41.67  727.67   42.55  829.55   44.03  875.69   48.46
  905.78    51.8  926.88   54.95  935.45    55.6  936.63   56.18  947.04      57
#Mann= 4 ,-1 , 0
       0    .085       0  441.98     .05       0  462.34     .09       0
  492.55     .08       0
Bank Sta=441.98,462.34
XS Rating Curve= 0 ,0
Exp/Cntr=0.3,0.1

Type RM Length L Ch R = 1 ,9937    ,247.9,399.21,392.98
XS GIS Cut Line= 3
 2415750.2163434607011.8276727352416098.95254652606699.526595354
2416242.45888054606186.361044154
#Sta/Elev= 30
       0   52.01   44.29   52.49  105.96   50.93  154.31   47.41  254.71   36.82
  287.47    34.5  314.21   34.29  325.91   32.83  334.23   33.38   340.5   35.24
  360.07   38.72  370.72   35.59  408.34    36.7   426.6    40.7  443.82   43.34
  454.51   43.93  476.89   44.22  495.86    43.5  498.14   44.43  532.55   43.08
  554.15    43.4  619.92   41.97  654.96   45.65  701.97   49.07  764.14   50.85
  792.21   50.42  817.29   49.15  875.25   49.26  929.59   52.94 1000.99   61.89
#Mann= 3 ,-1 , 0
       0    .085       0  314.21     .05       0  334.23     .09       0
Bank Sta=314.21,334.23
XS Rating Curve= 0 ,0
Exp/Cntr=0.3,0.1

Type RM Length L Ch R = 1 ,9538    ,348.87,350.24,340.84
XS GIS Cut Line= 2
2415742.30956811607089.490705475 2416460.7437758607072.974976569
#Sta/Elev= 30
       0   51.68   72.12   49.84   95.65   48.62  169.41   39.01  196.56   36.79
  215.51   36.61  225.63   36.85  270.37   38.63  323.18   38.48  340.12   37.33
  371.74   33.68  383.75   32.22   392.3   33.29  416.01   36.14  428.12   37.62
  440.52   38.54  443.53   38.76  456.37   40.14   483.5   43.83  497.06   44.24
  512.82   45.27  529.73    46.8  557.86   50.32  576.23   54.84  612.01   63.01
  649.14   72.31  671.41   74.67  678.73   74.98  695.65   75.57  718.62   75.14
#Mann= 6 ,-1 , 0
       0    .085       0  371.74     .05       0   392.3     .09       0
  416.01     .04       0  440.52     .09       0  443.53     .04       0
Bank Sta=371.74,392.3
XS Rating Curve= 0 ,0
Exp/Cntr=0.3,0.1

Type RM Length L Ch R = 1 ,9188    ,396.01,296.01,232.31
XS GIS Cut Line= 2
2415779.46995816607448.7078093442416428.69527425607397.536272913
#Sta/Elev= 30
       0   47.15   39.56   47.45   44.16    47.1      65    43.8  134.65   39.95
   183.2   36.38  261.24   36.12  298.53   34.99     312   34.57  316.11   32.56
  316.46   31.76  318.65      33  323.64   35.82  331.34   38.16  336.14   37.32
  359.61   36.96  369.24   36.66  398.58   37.26  405.81   38.24  423.95   39.21
  444.69    41.3   492.3   44.04  518.15   46.77  543.69   51.79   560.2   54.55
  571.18   56.51  607.35   64.36  626.14   66.49  642.04    68.7  651.24   68.55
#Mann= 5 ,-1 , 0
       0    .085       0  298.53     .05       0  318.65     .09       0
  359.61     .04       0   560.2    .075       0
Bank Sta=298.53,318.65
XS Rating Curve= 0 ,0
Exp/Cntr=0.3,0.1

Type RM Length L Ch R = 1 ,8892    ,250.99,294.74,307.23
XS GIS Cut Line= 2
2415969.40084066607940.0507445342416411.19658908607456.965673804
#Sta/Elev= 30
       0   42.92   26.14   42.56   35.95   41.62    42.3   41.87   92.83   40.26
  104.86   39.14   119.6   39.64  126.13   39.26  153.64   39.28  181.38   37.96
  206.73   39.04   270.1   40.68  298.37   35.88  322.65   33.01  334.85   33.04
  354.88   32.98   363.6   32.95  365.06   31.18  379.68   36.06  396.58   35.76
   421.5    36.4  471.11   36.58  505.12   37.82  548.74   38.02   559.6   38.75
  574.63   42.02   595.3   44.62  603.83   45.11   635.5   52.16  654.64   57.38
#Mann= 4 ,-1 , 0
       0    .085       0  334.85     .05       0  354.88     .04       0
  505.12    .075       0
Bank Sta=334.85,354.88
XS Rating Curve= 0 ,0
Exp/Cntr=0.3,0.1

Type RM Length L Ch R = 1 ,8597    ,217.03,502.4,458.39
XS GIS Cut Line= 2
2416068.49521413 608134.110559272416679.57718393607646.896556303
#Sta/Elev= 30
       0    46.1   60.37   43.67   68.37   42.73  134.31   39.01  201.74   40.17
  242.52   40.11  302.36   38.03  323.28   38.47  363.85   37.66  396.47   35.63
  423.02   36.21  443.88   34.41  462.06    35.3  468.84   33.83  482.09   30.99
  491.37   32.42  496.12   32.56   509.9   32.98  528.37   34.21  539.98   35.79
  549.43   35.39  567.08   35.51  609.28   36.42  633.25   36.03  654.64   37.93
  691.13   42.29  704.79   43.35  710.64   43.84  754.62   49.62  781.54   60.29
#Mann= 4 ,-1 , 0
       0    .085       0  468.84     .05       0  496.12     .04       0
  704.79    .075       0
Bank Sta=468.84,496.12
XS Rating Curve= 0 ,0
Exp/Cntr=0.3,0.1