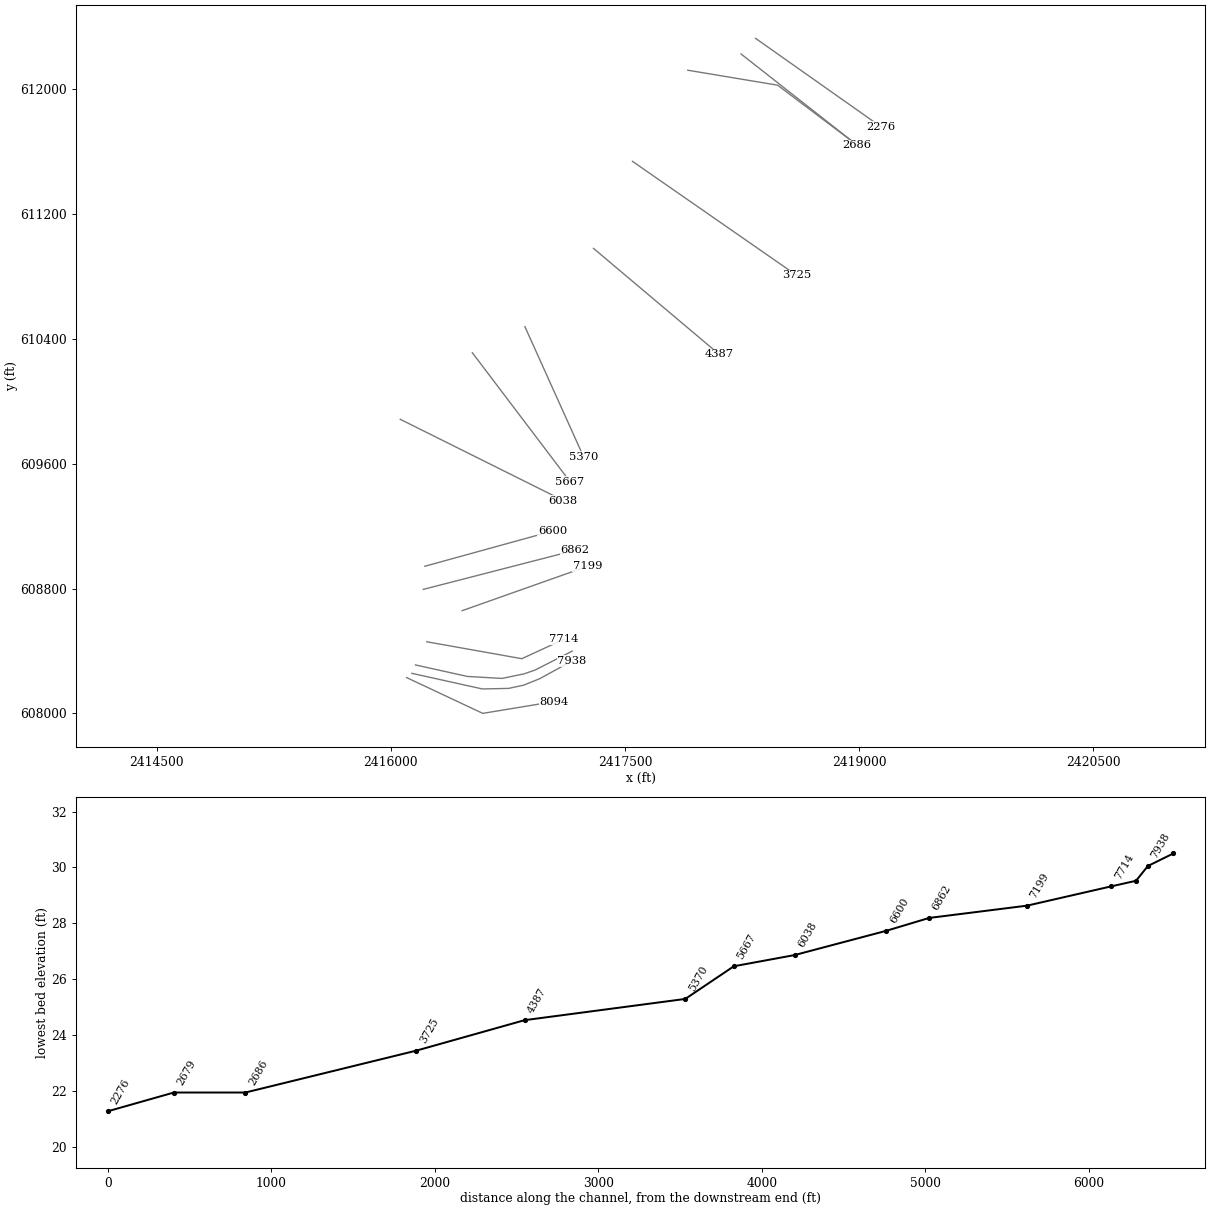
HEC-RAS study DTL_Rainbow_Creek.prj: DTL_Rainbow_Creek

--- DTL_Rainbow_Creek.g02 (geometry) --- (continued)

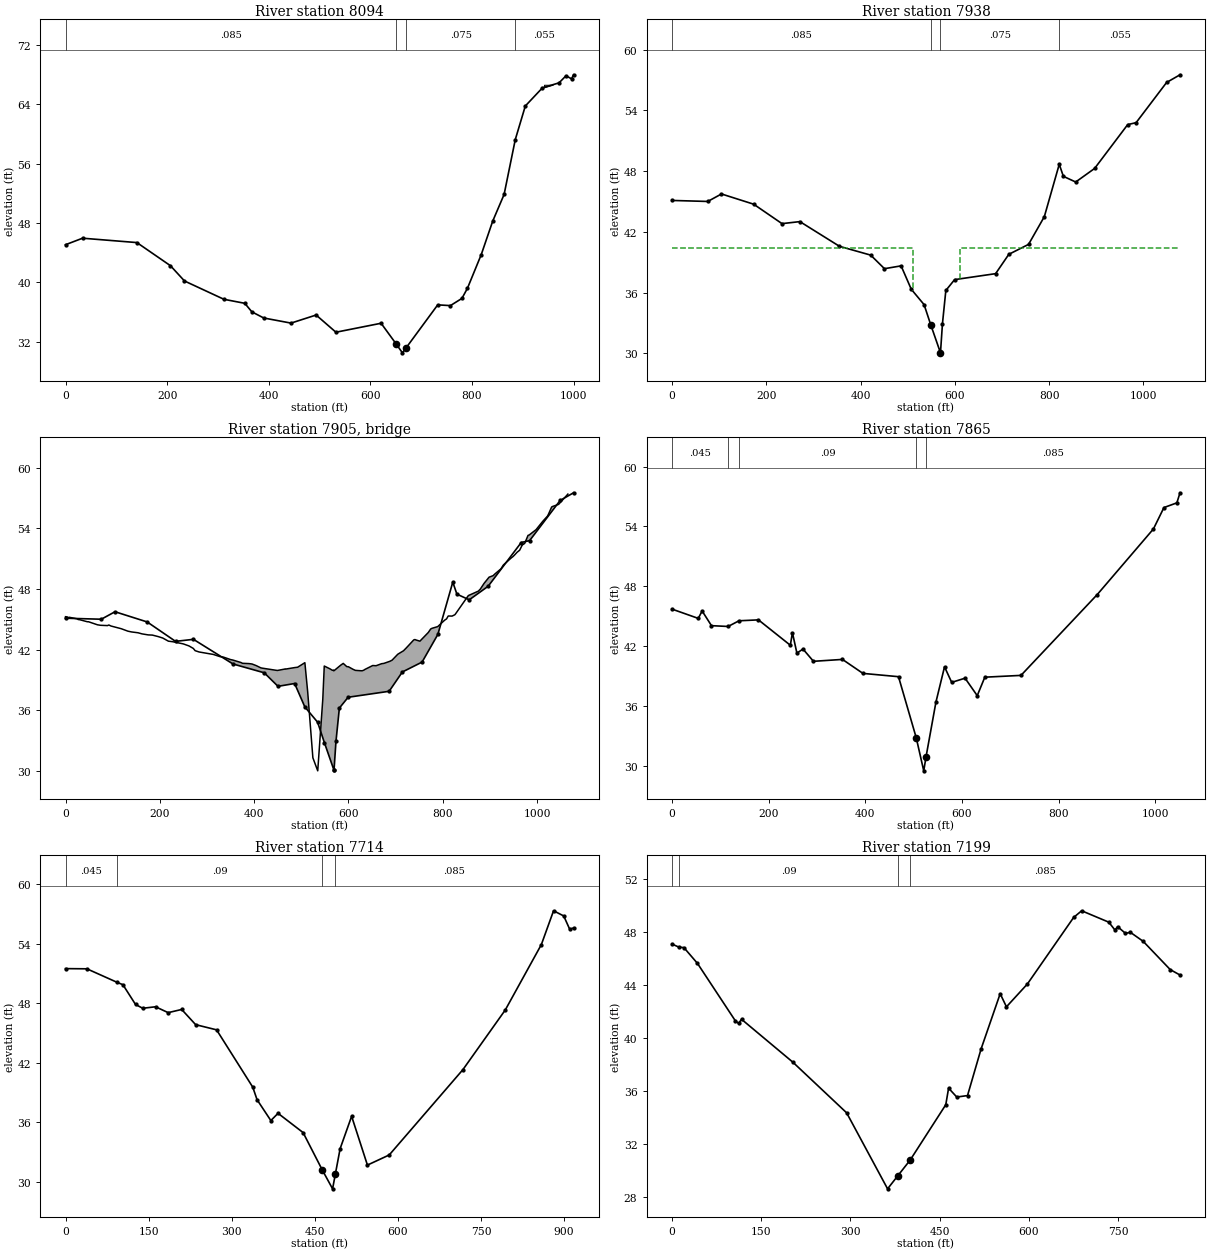
Type RM Length L Ch R = 1 ,8094    ,183.94,156.21,142.54
XS GIS Cut Line= 3
 2416100.8672124608229.9643011392416588.87755938608000.557727769
2417043.51967753608075.636242688
#Sta/Elev= 30
       0   45.08   33.54   45.96   140.5   45.37   206.6   42.25  234.22   40.19
  311.86   37.72   352.9   37.18   366.8   36.03  390.21    35.2   443.9   34.51
  493.32    35.6   532.3   33.28   621.2   34.49  650.33   31.75  663.16    30.5
  670.43   31.17  732.68   36.97  757.66   36.87   780.3   37.84   791.2   39.21
  818.36   43.75   840.9   48.26  863.34   51.86  885.34   59.26  905.11   63.79
  938.81   66.24  971.45   66.91  985.25   67.87  996.09   67.45 1000.04      68
#Mann= 4 ,-1 , 0
       0    .085       0  650.33     .05       0  670.43    .075       0
  885.34    .055       0
#Block Obstruct= 1 ,-1
  941.81  959.3866.66013
Bank Sta=650.33,670.43
XS Rating Curve= 0 ,0
Exp/Cntr=0.5,0.3

Type RM Length L Ch R = 1 ,7938    ,71.74,72.77,66.54
BEGIN DESCRIPTION:
Survyed Section
END DESCRIPTION:
XS GIS Cut Line= 6
2416134.06479475608257.171257079    2416586.1776608157.058500022
2416753.92560001608160.5377000122416851.17364818 608181.32526882
2416953.32416432608222.5783618542417160.68378025608336.086082697
#Sta/Elev= 30
       0    45.1   75.89      45  105.01   45.74  173.25   44.73  233.37   42.81
  271.31   43.01  355.27   40.57  421.48    39.7  450.68   38.36  485.95   38.64
  507.51   36.33  534.71   34.81  548.98    32.8  569.24   30.08  569.46   30.05
  573.68   32.94  580.84   36.21  599.44   37.28  686.39   37.87  714.42   39.78
  756.25   40.76  789.75    43.5  821.37   48.67  830.12   47.48  856.27   46.92
  896.37   48.26  966.54   52.59  984.35   52.78 1049.03   56.75 1077.49   57.51
#Mann= 4 ,-1 , 0
       0    .085       0  548.98     .05       0  569.24    .075       0
  821.37    .055       0
#XS Ineff= 2 , 0
       0  510.77   40.39  609.84       0   40.43
Permanent Ineff=
       F       F
Bank Sta=548.98,569.24
XS Rating Curve= 0 ,0
Exp/Cntr=0.5,0.3

Type RM Length L Ch R = 3 ,7905    ,,,
Bridge Culvert--1,0,-1,-1, 0
Deck Dist Width WeirC Skew NumUp NumDn MinLoCord MaxHiCord MaxSubmerge Is_Ogee
,,2.6,0, 150, 150, , , 0.98, 0, 0,0,,
       0    3.03    5.29    8.27   24.55   26.91   30.23   46.23   48.77   52.44
   67.67   74.25   89.14   91.89   96.33  110.79  118.32  132.19  140.28  153.81
  162.28  175.24  184.25  196.79  206.19  218.18  228.05  232.01  239.96  249.74
  261.78  271.06  274.89  283.32  287.26  296.59  305.59   313.3  327.58  334.22
   338.2  349.91  355.01     372  375.39  389.24  394.35  395.64  404.49  414.27
  417.25   432.1  440.54  440.87  449.31  465.28  465.87  467.05   486.7  492.18
  492.27  507.67  509.81  513.62  524.64  526.67  534.94  544.05  545.63  548.79
  561.35  566.27  568.17  568.72  569.54  584.08  589.03  596.12  596.58  599.92
  609.62  614.76  627.52  630.04  633.39  634.84  651.59  658.64  670.37  675.17
  686.36  688.03  692.62  704.57   706.9  716.85  723.14  736.48  737.87  738.48
  740.92  743.85  751.61  769.45  774.42  777.18   785.3  789.44  804.19   808.1
  811.42  811.73  819.87  825.62  827.06  854.34  875.63  877.55  879.74  887.78
  898.32  906.92  910.74  923.45  927.85  928.76  944.98  949.33  952.52  957.64
  963.21  968.64  973.87  979.45  980.99  983.27  996.23  997.98 1011.77 1012.09
 1018.03 1020.14 1022.02 1024.08 1031.02 1032.71 1045.11 1045.58 1046.14 1065.51
   45.25   45.23   45.17   45.19   45.04   44.97   44.95   44.75   44.75   44.69
   44.45    44.4   44.37   44.43   44.33   44.15   44.06   43.82   43.74   43.66
   43.55   43.45   43.43   43.28   43.14   42.83   42.77   42.73   42.64   42.56
   42.36   42.11   41.89   41.76   41.73   41.66   41.58   41.52    41.3   41.26
    41.2   41.01   40.96   40.72   40.64   40.61   40.58   40.57   40.41   40.19
   40.16   40.05   39.99   39.99   39.93   40.07   40.09   40.07   40.22   40.25
   40.25    40.7   39.67   37.83   31.29   31.04      30   36.03   37.07   40.37
   40.08   39.94   39.97    39.9   39.91   40.47   40.63   40.33   40.31    40.3
   40.05   39.94    39.9   39.91   39.98   40.03   40.42    40.4    40.6   40.63
   40.82   40.84   40.95   41.53    41.6   41.88   42.18   42.86   42.93   42.95
   42.99   42.94   42.83   43.69   44.03    44.1   44.22   44.27   44.91   45.03
   45.31   45.32   45.31   45.44   45.52   47.34   47.78   47.87   47.98   48.55
   49.16   49.31   49.48   49.98   50.32   50.37   51.05   51.21   51.36   51.62
   51.83   52.34    52.5   53.14    53.3   53.33    53.8   53.86   54.66   54.68
   54.98   55.09   55.19   55.37    56.1   56.15   56.35   56.36   56.38   57.38
                                                                                
                                                                                
                                                                                
                                                                                
                                                                                
                                                                                
                                                                                
                                                                                
                                                                                
                                                                                
                                                                                
                                                                                
                                                                                
                                                                                
                                                                                
       0    3.03    5.29    8.27   24.55   26.91   30.23   46.23   48.77   52.44
   67.67   74.25   89.14   91.89   96.33  110.79  118.32  132.19  140.28  153.81
  162.28  175.24  184.25  196.79  206.19  218.18  228.05  232.01  239.96  249.74
  261.78  271.06  274.89  283.32  287.26  296.59  305.59   313.3  327.58  334.22
   338.2  349.91  355.01     372  375.39  389.24  394.35  395.64  404.49  414.27
  417.25   432.1  440.54  440.87  449.31  465.28  465.87  467.05   486.7  492.18
  492.27  507.67  509.81  513.62  524.64  526.67  534.94  544.05  545.63  548.79
  561.35  566.27  568.17  568.72  569.54  584.08  589.03  596.12  596.58  599.92
  609.62  614.76  627.52  630.04  633.39  634.84  651.59  658.64  670.37  675.17
  686.36  688.03  692.62  704.57   706.9  716.85  723.14  736.48  737.87  738.48
  740.92  743.85  751.61  769.45  774.42  777.18   785.3  789.44  804.19   808.1
  811.42  811.73  819.87  825.62  827.06  854.34  875.63  877.55  879.74  887.78
  898.32  906.92  910.74  923.45  927.85  928.76  944.98  949.33  952.52  957.64
  963.21  968.64  973.87  979.45  980.99  983.27  996.23  997.98 1011.77 1012.09
 1018.03 1020.14 1022.02 1024.08 1031.02 1032.71 1045.11 1045.58 1046.14 1065.51
   45.25   45.23   45.17   45.19   45.04   44.97   44.95   44.75   44.75   44.69
   44.45    44.4   44.37   44.43   44.33   44.15   44.06   43.82   43.74   43.66
   43.55   43.45   43.43   43.28   43.14   42.83   42.77   42.73   42.64   42.56
   42.36   42.11   41.89   41.76   41.73   41.66   41.58   41.52    41.3   41.26
    41.2   41.01   40.96   40.72   40.64   40.61   40.58   40.57   40.41   40.19
   40.16   40.05   39.99   39.99   39.93   40.07   40.09   40.07   40.22   40.25
   40.25    40.7   39.67   37.83   31.29   31.04      30   36.03   37.07   40.37
   40.08   39.94   39.97    39.9   39.91   40.47   40.63   40.33   40.31    40.3
   40.05   39.94    39.9   39.91   39.98   40.03   40.42    40.4    40.6   40.63
   40.82   40.84   40.95   41.53    41.6   41.88   42.18   42.86   42.93   42.95
   42.99   42.94   42.83   43.69   44.03    44.1   44.22   44.27   44.91   45.03
   45.31   45.32   45.31   45.44   45.52   47.34   47.78   47.87   47.98   48.55
   49.16   49.31   49.48   49.98   50.32   50.37   51.05   51.21   51.36   51.62
   51.83   52.34    52.5   53.14    53.3   53.33    53.8   53.86   54.66   54.68
   54.98   55.09   55.19   55.37    56.1   56.15   56.35   56.36   56.38   57.38
                                                                                
                                                                                
                                                                                
                                                                                
                                                                                
                                                                                
                                                                                
                                                                                
                                                                                
                                                                                
                                                                                
                                                                                
                                                                                
                                                                                
                                                                                
BR Coef=-1 , 0 , 0 ,, 0 ,,,0.8,-1,,0,
WSPro=,,,, 1 ,,,, 0 ,,,, 0 ,,,,-1 ,-1 ,-1 , 0 , 0 , 0 , 0 , 0
BC Design=,, 0 ,, 0 ,,,,,,
BC Use User HTab Curves=0
BC User HTab FreeFlow(D)= 0

Type RM Length L Ch R = 1 ,7865    ,161.49,151.95,157.29
BEGIN DESCRIPTION:
Survyed Section
END DESCRIPTION:
XS GIS Cut Line= 6
2416157.72879829608310.9778469652416489.71797575608237.311609387
    2416712.2403608224.4977000062416853.69409998608253.835400015
2416923.95952538608278.1577057842417161.81332022608399.340322167
#Sta/Elev= 30
       0   45.72   54.35   44.79   62.41   45.53   81.72   44.06  116.13   43.98
  138.72   44.55  178.88   44.64  244.81    42.1  249.18   43.35  258.44   41.31
  271.03   41.72  292.66   40.49  352.63   40.68  395.04   39.28   468.6   38.95
  505.28   32.83  520.79   29.52  525.57   30.93  546.09   36.42  563.78   39.94
  578.61   38.38  606.26    38.8  631.47   37.05  647.13    38.9  721.94   39.08
  879.77   47.18  995.97   53.75 1017.66   55.89 1044.41   56.36 1050.92   57.37
#Mann= 5 ,-1 , 0
       0    .045       0  116.13    .035       0  138.72     .09       0
  505.28     .05       0  525.57    .085       0
#XS Ineff= 2 , 0
       0  464.76   38.69  563.83       0   38.69
Permanent Ineff=
       F       F
Bank Sta=505.28,525.57
XS Rating Curve= 0 ,0
Exp/Cntr=0.5,0.3

Type RM Length L Ch R = 1 ,7714    ,355.29,514.33,452.64
XS GIS Cut Line= 3
2416230.16909926608459.3708745092416839.13927579608350.924130753
2417110.25613526 608476.05498895
#Sta/Elev= 30
       0   51.48   38.63   51.46   92.72   50.11  103.65   49.86  126.45   47.87
   139.4   47.49  162.49   47.64  185.35   47.05  209.75   47.37  234.96   45.84
  272.71   45.32  338.07   39.55   345.8   38.29  370.71   36.19  383.66   36.92
  428.94   34.98  463.62   31.21  482.16   29.32   487.1   30.79  495.75   33.36
  516.53   36.62  545.04   31.71  584.44   32.73  717.49   41.32  793.93   47.32
  859.04    53.9  881.06    57.3  899.43   56.78  910.29   55.43  917.15   55.57
#Mann= 4 ,-1 , 0
       0    .045       0   92.72     .09       0  463.62     .05       0
   487.1    .085       0
Bank Sta=463.62,487.1
XS Rating Curve= 0 ,0
Exp/Cntr=0.3,0.1

Type RM Length L Ch R = 1 ,7199    ,374.11,599.02,316.28
XS GIS Cut Line= 2
2416456.61484362608658.4849522862417261.75662814608943.381276026
#Sta/Elev= 30
       0   47.11   11.87   46.87   20.07   46.84   42.84   45.65  106.58   41.31
  112.07   41.12  116.94   41.43  203.24   38.19  293.59   34.37  362.46   28.63
  379.89   29.63  400.55   30.81  460.29   34.98  465.02   36.23  478.76   35.56
  496.82   35.67  519.65   39.19  551.73   43.36  562.28   42.37  597.43   44.09
   675.3   49.12  688.73   49.62  734.32   48.76  744.62   48.17  749.23   48.42
  762.28   47.92  770.73   47.99  792.23   47.31   837.6   45.18  854.06   44.77
#Mann= 4 ,-1 , 0
       0    .045       0   11.87     .09       0  379.89     .05       0
  400.55    .085       0
Bank Sta=379.89,400.55
XS Rating Curve= 0 ,0
Exp/Cntr=0.3,0.1

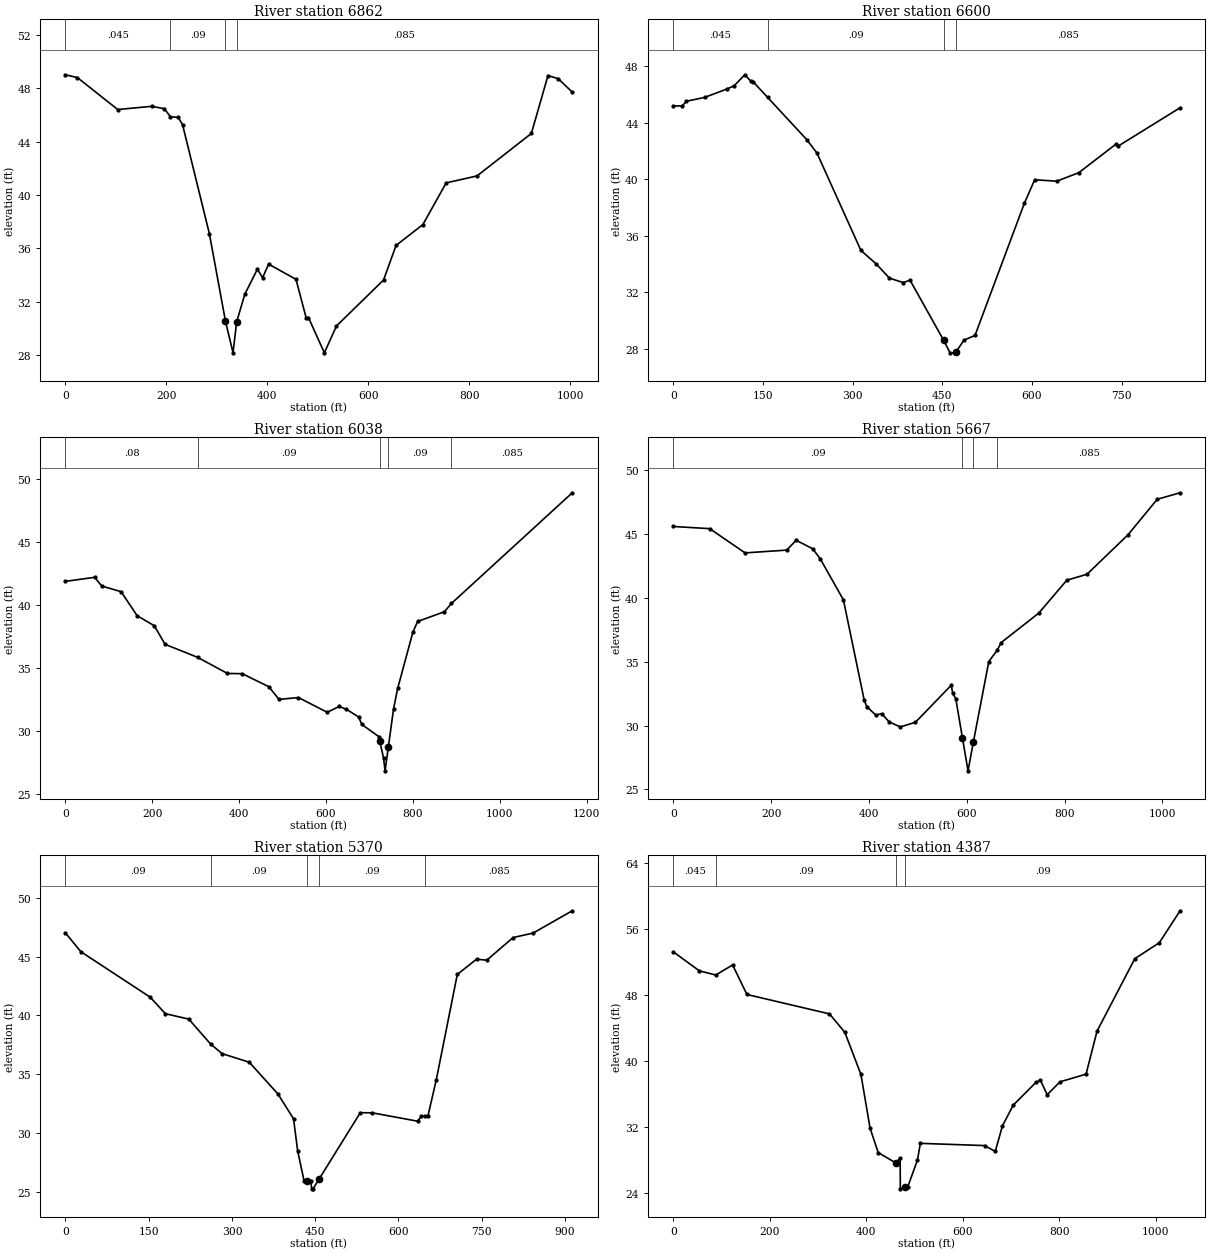
Type RM Length L Ch R = 1 ,6862    ,151.51,261.98,155.39
XS GIS Cut Line= 2
2416207.43213448608794.9301204532417179.91711341609045.340714678
#Sta/Elev= 30
       0      49   23.72   48.79  103.57    46.4  171.14   46.64  196.01   46.46
  208.07   45.86  223.56   45.81  232.02   45.27  285.12   37.12  317.12   30.55
  332.03    28.2  339.31   30.52  355.45   32.58  380.35   34.45  390.63   33.81
  402.56   34.83  456.81   33.69  476.94   30.81  481.53   30.83     513   28.19
  537.04    30.2  630.26   33.64  655.12   36.23  708.25   37.79  754.43   40.91
  815.56   41.43  923.22   44.61   956.1   48.94  976.34   48.71 1004.21    47.7
#Mann= 4 ,-1 , 0
       0    .045       0  208.07     .09       0  317.12     .05       0
  339.31    .085       0
Bank Sta=317.12,339.31
XS Rating Curve= 0 ,0
Exp/Cntr=0.3,0.1

Type RM Length L Ch R = 1 ,6600    ,726.16,561.86,499.35
XS GIS Cut Line= 2
2416217.65601343608943.2101928892417035.17762029609168.445737645
#Sta/Elev= 30
       0   45.19   14.67   45.17   21.96   45.51    52.5   45.78   90.15   46.38
  101.95   46.61  119.75   47.38  129.44   46.94  133.53   46.89  157.72   45.79
  223.25    42.8   240.4   41.85  313.94   34.97  339.63   34.01  361.68   33.01
   385.1   32.69  396.09   32.87  452.48   28.61  463.16   27.73  472.06   27.74
  473.26   27.81  486.48   28.63  504.86   28.96  587.37   38.29  604.71   39.96
  641.59   39.86  678.48   40.46  741.09   42.49  744.46   42.34  847.98   45.05
#Mann= 4 ,-1 , 0
       0    .045       0  157.72     .09       0  452.48     .05       0
  473.26    .085       0
Bank Sta=452.48,473.26
XS Rating Curve= 0 ,0
Exp/Cntr=0.3,0.1

Type RM Length L Ch R = 1 ,6038    ,488.76,371.07,301.18
XS GIS Cut Line= 2
2416060.23734966609884.7778241192417104.85720345 609364.53236334
#Sta/Elev= 30
       0   41.88   67.27    42.2   83.59   41.51  128.13   41.06  165.24   39.15
  204.72   38.36  229.28   36.89  304.12   35.86  372.99   34.58  407.18   34.56
   468.2   33.53  491.86   32.52  536.61   32.67  602.74    31.5  629.97   31.96
  646.98   31.74  675.31   31.12  682.24   30.54  721.34   29.58  723.54   29.24
  732.39   27.89  736.01   26.86  743.61   28.77  755.57   31.78  765.06    33.4
  799.92   37.84  810.91    38.7  872.52   39.47   888.9   40.13    1167    48.9
#Mann= 5 ,-1 , 0
       0     .08       0  304.12     .09       0  723.54     .05       0
  743.61     .09       0   888.9    .085       0
Bank Sta=723.54,743.61
XS Rating Curve= 0 ,0
Exp/Cntr=0.3,0.1

Type RM Length L Ch R = 1 ,5667    ,283.99,297.21,233.39
XS GIS Cut Line= 2
2416522.14110172610311.3075758812417147.79539274609485.443911746
#Sta/Elev= 30
       0    45.6   74.54   45.43  146.83   43.53  231.96   43.75  251.23   44.52
   284.8   43.86  300.14   43.09  347.85   39.85  390.53   31.97  395.78   31.48
  413.77   30.84  426.23   30.93   441.8   30.28  464.23    29.9  494.98   30.26
  568.49   33.17  571.15   32.54  577.57   32.11   591.2   29.03   602.6   26.46
  613.58   28.73  645.08   35.02  662.17    35.9  670.44   36.51  747.13   38.81
  804.53   41.39   845.9   41.86  929.68   44.95  989.34   47.73  1036.1   48.24
#Mann= 4 ,-1 , 0
       0     .09       0   591.2     .05       0  613.58     .09       0
  662.17    .085       0
Bank Sta=591.2,613.58
XS Rating Curve= 0 ,0
Exp/Cntr=0.3,0.1

Type RM Length L Ch R = 1 ,5370    ,848.76,982.8,952.41
XS GIS Cut Line= 2
2416858.92407827610478.3064871132417234.23209807609645.841358185
#Sta/Elev= 30
       0      47   27.73   45.41  152.69   41.55  180.01   40.15   222.2   39.69
  261.62   37.57   282.3   36.76  331.22   36.03  382.81   33.34  411.01   31.23
  418.41   28.51  429.88   25.98  436.03   25.96  442.24   25.94  443.61   25.29
  446.29   25.31  457.13   26.13  531.31   31.75  552.69   31.74  634.34   31.03
  641.25   31.43  647.98   31.47  653.27    31.5  668.17   34.54  706.04   43.48
  740.63   44.77  759.11   44.69  806.65   46.61   842.7   46.99  913.16   48.88
#Mann= 5 ,-1 , 0
       0     .09       0  261.62     .09       0  436.03     .05       0
  457.13     .09       0  647.98    .085       0
Bank Sta=436.03,457.13
XS Rating Curve= 0 ,0
Exp/Cntr=0.3,0.1

Type RM Length L Ch R = 1 ,4387    ,648.57,662.17,663.2
XS GIS Cut Line= 2
2417298.44531548610979.844578058 2418101.9561588610302.697684303
#Sta/Elev= 30
       0   53.24    54.2   50.93   88.27   50.43  123.04   51.65  152.74   48.07
  323.93   45.72  355.82   43.48  389.13   38.38     408   31.89  424.93   28.92
  461.19   27.68  470.41   28.26  470.82   24.53  481.37   24.74   486.3    24.8
  506.21   27.99   512.3   30.04  645.33   29.77  667.59   29.06   682.4   32.14
  704.94   34.67  751.98   37.43   761.3   37.68  775.23   35.93   801.8   37.49
  855.82   38.42  878.68   43.64  956.95   52.41 1007.79   54.34 1050.79   58.21
#Mann= 4 ,-1 , 0
       0    .045       0   88.27     .09       0  461.19     .05       0
  481.37     .09       0
Bank Sta=461.19,481.37
XS Rating Curve= 0 ,0
Exp/Cntr=0.3,0.1

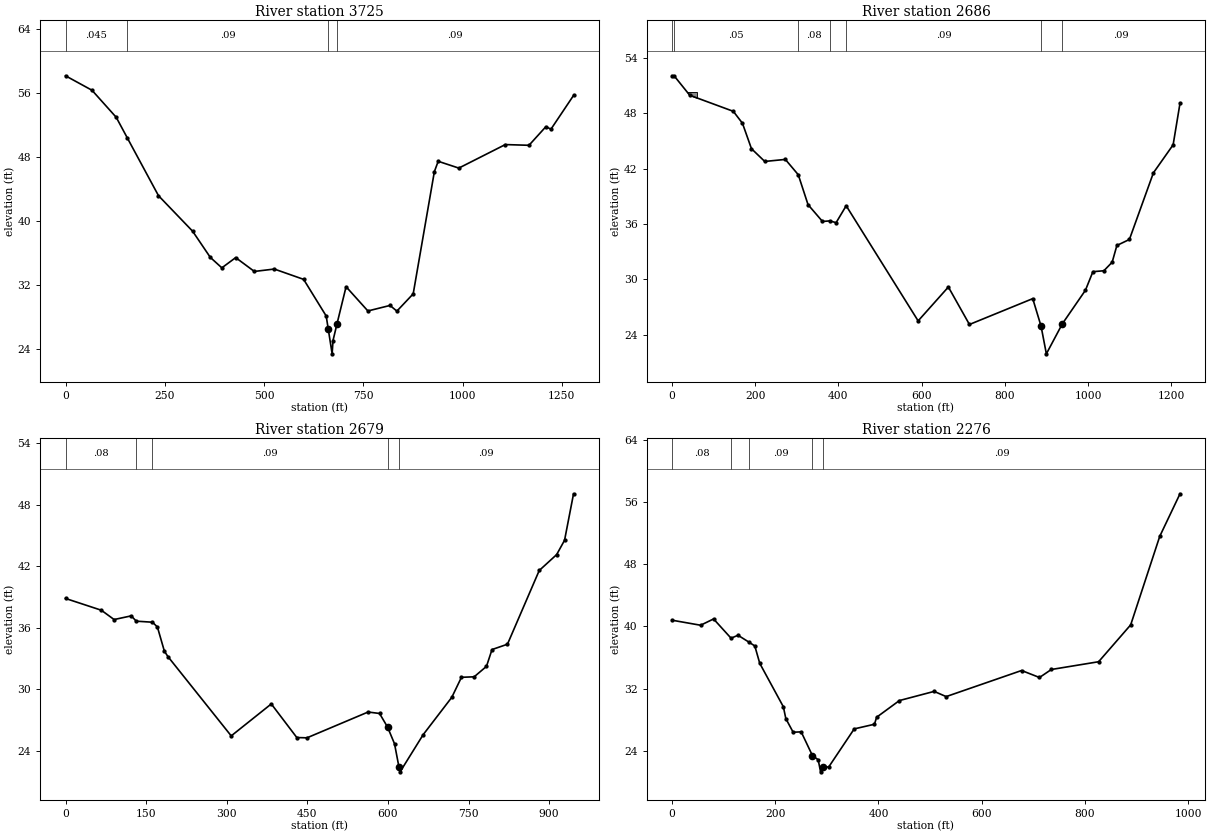
Type RM Length L Ch R = 1 ,3725    ,971.46,1045.77,948.86
XS GIS Cut Line= 2
2417548.21413893611537.5899862352418599.31334785610807.659980088
#Sta/Elev= 30
       0    58.2   66.72   56.39  127.73   53.01  155.48   50.45  234.22   43.21
  320.16   38.77  364.71    35.5  393.82   34.19  428.66   35.47  475.68   33.74
  525.96   34.04  599.77   32.75  656.65   28.17  661.73   26.57  671.62   23.44
   673.8    25.1  683.74   27.17  706.72   31.83  761.69    28.8  817.44   29.49
   834.7   28.78  875.79   30.94  929.14   46.22  938.78   47.51  990.68   46.66
 1107.78    49.6 1167.46   49.51 1210.03   51.84 1222.72   51.52 1279.69   55.74
#Mann= 4 ,-1 , 0
       0    .045       0  155.48     .09       0  661.73     .05       0
  683.74     .09       0
Bank Sta=661.73,683.74
XS Rating Curve= 0 ,0
Exp/Cntr=0.3,0.1

Type RM Length L Ch R = 1 ,2686    ,244.82,437.57,151.66
XS GIS Cut Line= 3
2417902.75157052612121.5339911732418478.35351823612025.600333214
2418987.21900828611641.865701407
#Sta/Elev= 30
       0   52.06    5.98   52.01   42.71   49.95  147.37   48.21  169.35   46.92
  191.02   44.16  222.97   42.78  272.46      43  303.51   41.34  326.97    38.1
  361.72   36.28  379.33   36.34  394.44   36.15  418.64   37.98  591.56   25.51
  664.22   29.18  714.84   25.12  866.96   27.92  886.96   24.94   899.7   21.94
  938.07   25.19  993.64   28.83 1011.56   30.84 1037.95   30.94 1057.87   31.87
 1069.17   33.68 1099.26   34.33 1156.96   41.55 1204.34   44.58 1220.88   49.09
#Mann= 7 ,-1 , 0
       0    .045       0    5.98     .05       0  303.51     .08       0
  379.33    .035       0  418.64     .09       0  886.96     .05       0
  938.07     .09       0
#Block Obstruct= 1 ,-1
   34.18   59.9950.30313
Bank Sta=886.96,938.07
XS Rating Curve= 0 ,0
Exp/Cntr=0.3,0.1

Type RM Length L Ch R = 1 ,2679    ,158.67,403.71,172.86
XS GIS Cut Line= 2
2418243.58569941612225.7961439042418987.21900828611641.865701407
#Sta/Elev= 30
       0   38.87   66.66   37.72   90.45   36.81  122.34   37.17  131.71   36.65
  161.87   36.55  171.05   36.08  184.01   33.72  190.82   33.18   308.4   25.45
  382.99   28.57  430.47   25.29  449.34   25.26  563.12   27.78  584.43   27.64
  599.35   26.31  612.33   24.68  620.53   22.42  622.67   21.94  665.65   25.57
  718.97   29.22  736.86   31.17   760.6   31.22  783.47   32.24  793.75   33.88
   822.5    34.4  881.64    41.6  914.03   43.15  928.76   44.55   945.5   49.09
#Mann= 5 ,-1 , 0
       0     .08       0  131.71    .035       0  161.87     .09       0
  599.35     .05       0  620.53     .09       0
Bank Sta=599.35,620.53
XS Rating Curve= 0 ,0
Exp/Cntr=0.3,0.1

Type RM Length L Ch R = 1 ,2276    ,192.54,365.77,231.63
XS GIS Cut Line= 2
2418336.61550865612325.8031888312419141.06847377611758.683278546
#Sta/Elev= 30
       0    40.8   55.47   40.15   80.58   40.96  114.47   38.48   127.9   38.86
  148.9237.98348   160.5   37.48  170.08   35.24  215.79   29.65  220.61   28.12
  234.77   26.37  250.32   26.42  272.15   23.36  283.27   22.83  287.88   21.27
  292.7221.92212   303.6   21.89  353.07    26.8  392.32    27.4  396.46    28.3
  440.61   30.45  507.92   31.63  531.24   30.96  677.34   34.32  711.99   33.42
  734.95   34.45  826.58   35.45  888.71    40.2     945    51.6  984.26   57.08
#Mann= 5 ,-1 , 0
       0     .08       0  114.47    .035       0  148.92     .09       0
  272.15     .05       0  292.72     .09       0
Bank Sta=272.15,292.72
XS Rating Curve= 0 ,0
Exp/Cntr=0.3,0.1