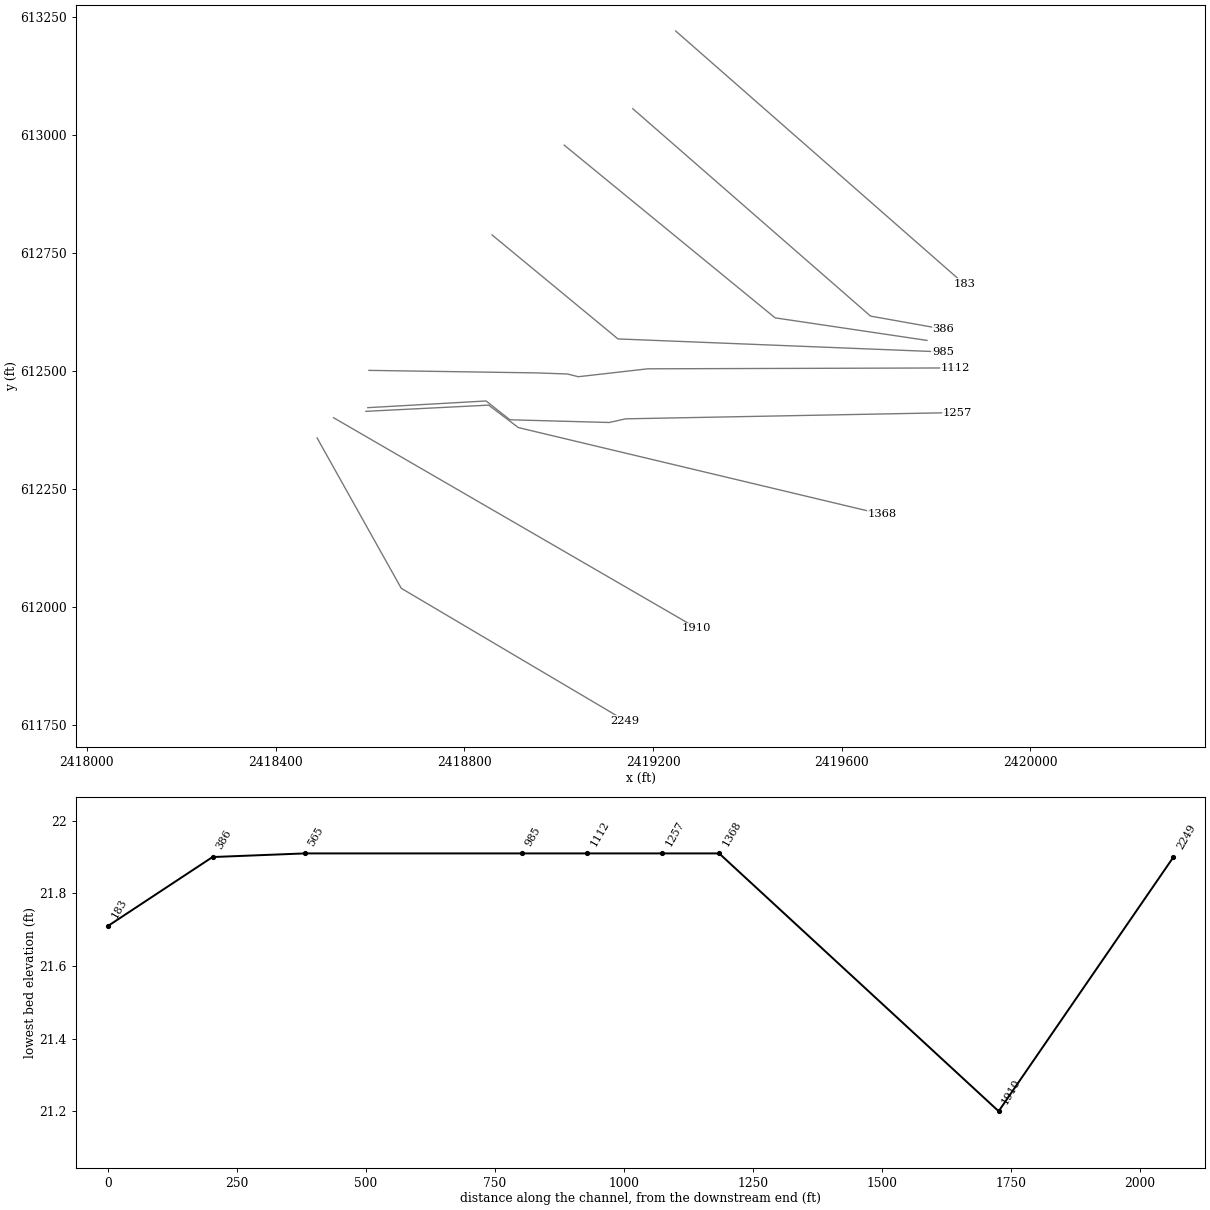
HEC-RAS study DTL_Rainbow_Creek.prj: DTL_Rainbow_Creek

--- DTL_Rainbow_Creek.g02 (geometry) --- (continued)

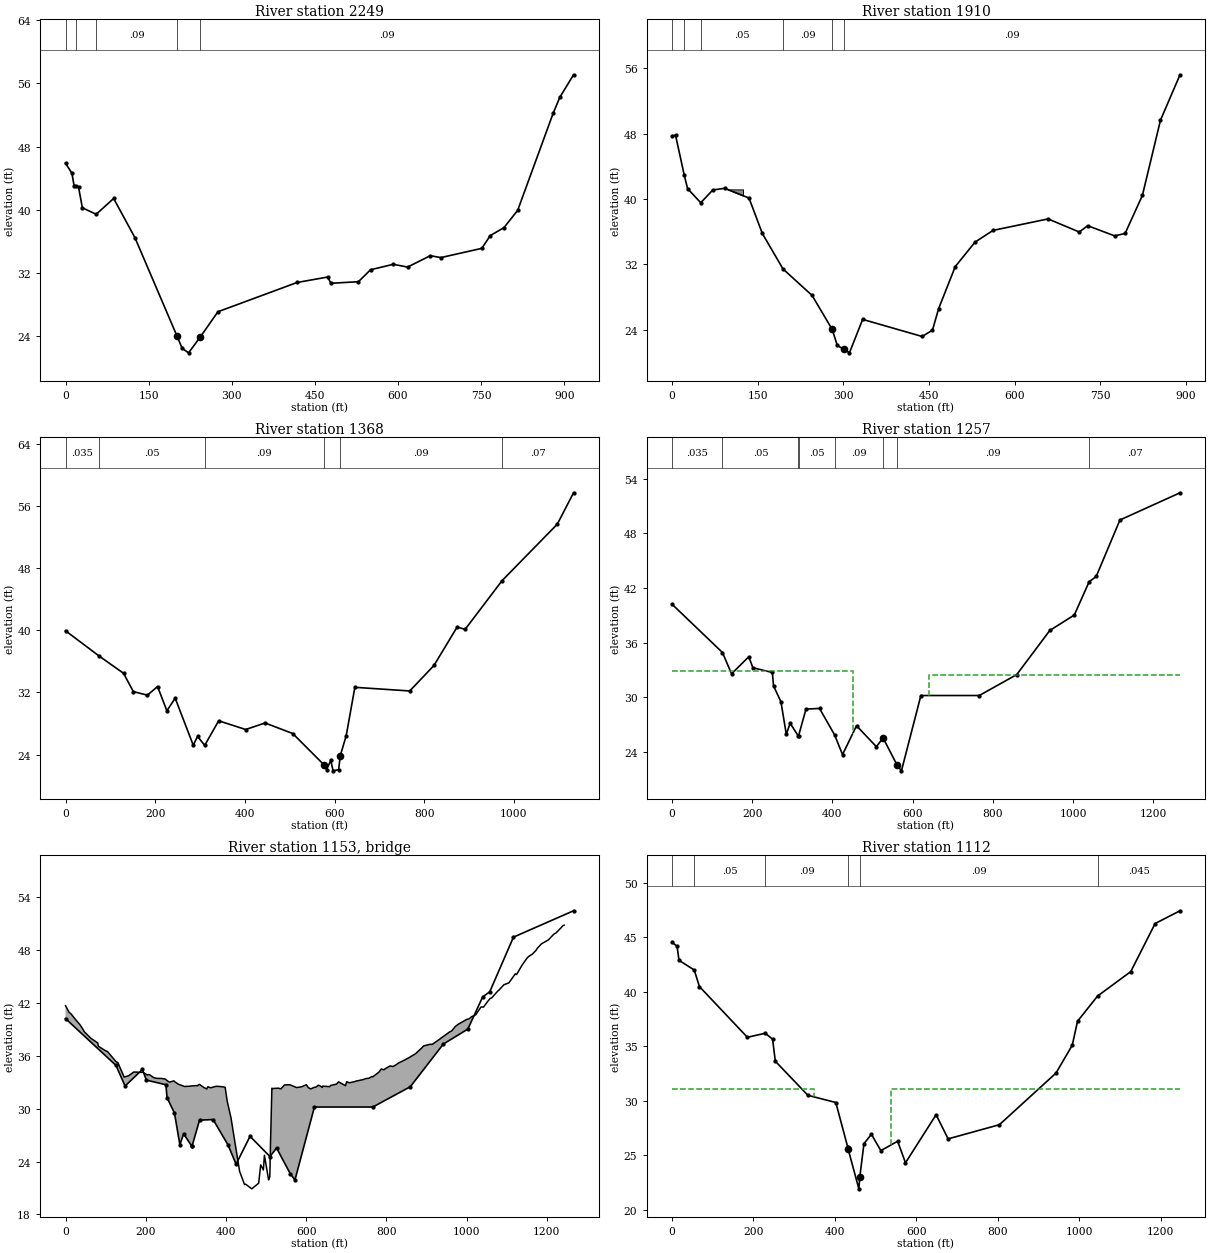
Type RM Length L Ch R = 1 ,2249    ,145.41,338.81,258.34
XS GIS Cut Line= 3
2418487.86782539612358.1724678282418666.32847995612039.368968323
2419141.06847377611758.683278546
#Sta/Elev= 30
       0   45.89   11.56   44.63   15.45   43.06   18.25   42.99    23.5   42.86
   30.45   40.25   55.38   39.43   86.89   41.43  125.37   36.46  200.98   24.06
  210.57   22.46  222.16    21.9  243.17    23.9   275.1    27.1  417.88    30.8
  473.06   31.49  478.93    30.7  528.67    30.9  550.47   32.41  591.47    33.1
  617.41   32.75  658.27   34.19  677.36   33.95  751.29   35.12  766.61   36.74
  791.16   37.73  816.05   39.93  880.06   52.21  892.16   54.24  916.86   57.08
#Mann= 5 ,-1 , 0
       0    .055       0   18.25    .035       0   55.38     .09       0
  200.98     .05       0  243.17     .09       0
Bank Sta=200.98,243.17
XS Rating Curve= 0 ,0
Exp/Cntr=0.3,0.1

Type RM Length L Ch R = 1 ,1910    ,222.43,541.77,316.37
XS GIS Cut Line= 2
2418522.89633608612400.9328841272419292.80403806611954.834238008
#Sta/Elev= 30
       0   47.68    6.18   47.83   21.53   42.91   27.34   41.27   50.45   39.55
   71.51   41.11   92.54   41.31  134.95   40.12   158.2    35.8  194.51   31.45
  245.36   28.22  280.65   24.06  289.56    22.1  301.11   21.64  310.81    21.2
  333.97   25.29   438.1    23.2  456.25   23.97  467.06   26.61  496.13   31.74
  530.85   34.74   562.5   36.17  658.67   37.57   713.4   35.97  728.18   36.74
  775.21    35.5  793.63   35.79  823.89   40.44  855.61   49.64  889.81   55.19
#Mann= 6 ,-1 , 0
       0    .055       0   21.53    .035       0   50.45     .05       0
  194.51     .09       0  280.65     .05       0  301.11     .09       0
#Block Obstruct= 1 ,-1
   97.17  124.4841.18141
Bank Sta=280.65,301.11
XS Rating Curve= 0 ,0
Exp/Cntr=0.3,0.1

Type RM Length L Ch R = 1 ,1368    ,8.88,110.89,116.25
XS GIS Cut Line= 4
 2418591.4164442612414.5169577152418851.64112537612427.668784782
2418914.54518759612380.0942838942419686.66171657612195.992712319
#Sta/Elev= 30
       0   39.94   74.22   36.72   129.5   34.46  151.31   32.11  182.67   31.65
  205.36   32.76  226.09   29.64  244.65   31.26  284.92   25.21  294.57   26.34
  310.49   25.19   341.6   28.35   401.9   27.23  445.22   28.07  506.88   26.71
  575.89   22.72  582.32   22.07  591.75   23.26  596.75   21.91  609.31   22.07
  612.83   23.85  626.06   26.42   645.4   32.66  767.79   32.19  821.81   35.47
  873.57   40.42  891.35   40.12  973.75   46.39 1096.95   53.66 1133.19    57.7
#Mann= 6 ,-1 , 0
       0    .035       0   74.22     .05       0  310.49     .09       0
  575.89     .05       0  612.83     .09       0  973.75     .07       0
Bank Sta=575.89,612.83
XS Rating Curve= 0 ,0
Exp/Cntr=0.5,0.3

Type RM Length L Ch R = 1 ,1257    ,207.1,145.32,163.63
BEGIN DESCRIPTION:
Survyed Section
END DESCRIPTION:
XS GIS Cut Line= 6
2418595.44186351612422.3113597632418846.13014105 612436.48069717
    2418896.6248612396.6303000152419107.30070002612390.868699998
2419141.81322898612398.6275251062419845.74596103 612411.97989215
#Sta/Elev= 30
       0   40.21  125.93    34.9  148.57   32.56  191.61   34.44  201.72   33.23
  250.32   32.71  253.25   31.24  271.75   29.49  285.16    25.9  294.53   27.14
  315.21   25.72  315.84   25.78  334.21   28.69     368   28.76  405.66   25.85
  425.33   23.69  460.16   26.86   509.8   24.56   526.4   25.53  560.86   22.58
  572.21   21.91   620.7   30.18  766.34   30.18  859.82   32.48  942.16   37.32
 1003.32   39.02 1040.25   42.67 1057.93   43.25 1117.05   49.45  1266.9   52.44
#Mann= 8 ,-1 , 0
       0    .035       0  125.93     .05       0  315.21     .09       0
  315.84     .05       0  405.66     .09       0   526.4     .05       0
  560.86     .09       0 1040.25     .07       0
#XS Ineff= 2 , 0
       0  450.55    32.9  640.55       0   32.43
Permanent Ineff=
       F       F
Bank Sta=526.4,560.86
XS Rating Curve= 0 ,0
Exp/Cntr=0.5,0.3

Type RM Length L Ch R = 3 ,1153    ,,,
Bridge Culvert--1,0,-1,-1, 0
Deck Dist Width WeirC Skew NumUp NumDn MinLoCord MaxHiCord MaxSubmerge Is_Ogee
,,2.6,0, 195, 195, , , 0.98, 0, 0,0,,
       0     8.8    8.91    8.94   13.64   25.49   34.08   36.17   41.96   47.25
   63.45    80.3   82.16   98.34   104.2  105.74   125.5  130.86  135.19  146.32
  157.06  170.21  179.35  180.55  193.58  194.39  204.14  206.14  209.29  219.54
  224.44  226.76   229.6  239.19  248.42  253.97  255.57  259.77  269.93  274.14
  281.39  296.74  310.18  312.66  313.48  327.61  328.82  329.08  333.86  345.56
  352.21  355.14  362.08  373.25   375.4  378.22  385.05  393.33  398.15  403.17
  412.61  420.71  434.23  446.46   449.1  464.48  466.55  468.44  481.66  486.72
  493.37  496.02  506.48  508.87  509.52  511.17  511.25  514.41  514.64  516.89
  530.62  537.04  546.19  553.73  559.79  561.76  565.98  575.94  580.68  584.41
  589.48  600.56  602.03  605.78  608.37  610.93  620.75  623.78  630.74   637.4
   640.5  641.49  653.41  658.94  660.73  664.37  675.54  675.67   675.7  680.87
  691.71  698.17   701.1  707.63  720.19  721.11   723.3  724.02  731.03  737.28
  742.73  749.47  757.17  763.77  765.41  767.16  781.59   783.1   787.5  793.74
  799.11  809.54  816.76  822.79  831.47  834.44  842.08  847.22  853.07  856.54
  873.21   888.5  893.15     901  909.18  914.58  922.47  934.47   936.1  936.41
  936.86  954.15  957.88  963.02  971.87   979.1  988.87  989.72 1000.56 1005.64
 1012.57 1021.85 1022.77 1036.08 1042.24 1053.41 1059.37  1062.3 1079.57 1081.22
 1082.61  1093.2 1104.89 1105.18 1105.52 1121.76 1124.82 1127.98  1138.5 1150.89
 1154.99 1164.38 1171.27  1173.5 1176.44 1186.93 1195.79 1203.85 1206.93 1218.12
 1223.24 1235.53 1240.21 1242.46 1243.38
   41.67   40.94   40.93   40.93   40.75   40.08   39.63   39.51   39.11    38.7
   37.97   37.45   37.07    36.6   36.48   36.42   35.35    35.2   34.73   33.58
   33.72   34.15   34.14   34.12   34.11   34.09   33.81   33.85   33.85   33.53
   33.46   33.44   33.43   33.42   33.36   33.16    33.1      33   33.15   32.99
   32.77   32.51   32.54   32.57   32.57   32.61   32.58   32.61   32.75   32.38
   32.23   32.48   32.36   32.51   32.53   32.53    32.5   32.47   32.41   30.86
   28.97   26.69   22.87   21.39   21.43    20.9   20.97   21.05   21.54   23.62
   23.04    24.7   21.91   22.19   22.32      26   26.18   31.75   32.31   32.28
   32.32   32.24   32.69    32.7   32.71   32.66   32.59   32.39   32.42   32.44
   32.49   32.71   32.61   32.36   32.32   32.23   32.42   32.42   32.66   32.51
    32.4   32.55   32.51   32.49   32.62   32.66   32.78   32.78   32.78   33.04
   32.77    32.6   33.05   32.93   33.06   33.06   33.11   33.12   33.18   33.25
    33.3   33.41   33.45   33.64   33.61   33.64   34.14   34.23    34.5    34.4
   34.58   34.84   34.78   34.93    35.2   35.26   35.43   35.55    35.7   35.78
   36.24   36.89   37.12    37.2    37.3   37.29   37.54   37.92   38.01   38.01
   38.01   38.59    38.7   38.81   39.31   39.56   39.83   39.84   40.12   40.17
   40.42    40.6   40.63   41.53   41.51   42.19   42.51   42.54   43.41   43.45
   43.53   44.05   44.24   44.25   44.26   45.29   45.21   45.46   46.27   47.07
   47.26   47.53   47.85   47.96   48.18   48.69   48.92   49.13   49.27    49.8
   49.93    50.5   50.75   50.78   50.81
                                                                                
                                                                                
                                                                                
                                                                                
                                                                                
                                                                                
                                                                                
                                                                                
                                                                                
                                                                                
                                                                                
                                                                                
                                                                                
                                                                                
                                                                                
                                                                                
                                                                                
                                                                                
                                                                                
                                        
       0     8.8    8.91    8.94   13.64   25.49   34.08   36.17   41.96   47.25
   63.45    80.3   82.16   98.34   104.2  105.74   125.5  130.86  135.19  146.32
  157.06  170.21  179.35  180.55  193.58  194.39  204.14  206.14  209.29  219.54
  224.44  226.76   229.6  239.19  248.42  253.97  255.57  259.77  269.93  274.14
  281.39  296.74  310.18  312.66  313.48  327.61  328.82  329.08  333.86  345.56
  352.21  355.14  362.08  373.25   375.4  378.22  385.05  393.33  398.15  403.17
  412.61  420.71  434.23  446.46   449.1  464.48  466.55  468.44  481.66  486.72
  493.37  496.02  506.48  508.87  509.52  511.17  511.25  514.41  514.64  516.89
  530.62  537.04  546.19  553.73  559.79  561.76  565.98  575.94  580.68  584.41
  589.48  600.56  602.03  605.78  608.37  610.93  620.75  623.78  630.74   637.4
   640.5  641.49  653.41  658.94  660.73  664.37  675.54  675.67   675.7  680.87
  691.71  698.17   701.1  707.63  720.19  721.11   723.3  724.02  731.03  737.28
  742.73  749.47  757.17  763.77  765.41  767.16  781.59   783.1   787.5  793.74
  799.11  809.54  816.76  822.79  831.47  834.44  842.08  847.22  853.07  856.54
  873.21   888.5  893.15     901  909.18  914.58  922.47  934.47   936.1  936.41
  936.86  954.15  957.88  963.02  971.87   979.1  988.87  989.72 1000.56 1005.64
 1012.57 1021.85 1022.77 1036.08 1042.24 1053.41 1059.37  1062.3 1079.57 1081.22
 1082.61  1093.2 1104.89 1105.18 1105.52 1121.76 1124.82 1127.98  1138.5 1150.89
 1154.99 1164.38 1171.27  1173.5 1176.44 1186.93 1195.79 1203.85 1206.93 1218.12
 1223.24 1235.53 1240.21 1242.46 1243.38
   41.67   40.94   40.93   40.93   40.75   40.08   39.63   39.51   39.11    38.7
   37.97   37.45   37.07    36.6   36.48   36.42   35.35    35.2   34.73   33.58
   33.72   34.15   34.14   34.12   34.11   34.09   33.81   33.85   33.85   33.53
   33.46   33.44   33.43   33.42   33.36   33.16    33.1      33   33.15   32.99
   32.77   32.51   32.54   32.57   32.57   32.61   32.58   32.61   32.75   32.38
   32.23   32.48   32.36   32.51   32.53   32.53    32.5   32.47   32.41   30.86
   28.97   26.69   22.87   21.39   21.43    20.9   20.97   21.05   21.54   23.62
   23.04    24.7   21.91   22.19   22.32      26   26.18   31.75   32.31   32.28
   32.32   32.24   32.69    32.7   32.71   32.66   32.59   32.39   32.42   32.44
   32.49   32.71   32.61   32.36   32.32   32.23   32.42   32.42   32.66   32.51
    32.4   32.55   32.51   32.49   32.62   32.66   32.78   32.78   32.78   33.04
   32.77    32.6   33.05   32.93   33.06   33.06   33.11   33.12   33.18   33.25
    33.3   33.41   33.45   33.64   33.61   33.64   34.14   34.23    34.5    34.4
   34.58   34.84   34.78   34.93    35.2   35.26   35.43   35.55    35.7   35.78
   36.24   36.89   37.12    37.2    37.3   37.29   37.54   37.92   38.01   38.01
   38.01   38.59    38.7   38.81   39.31   39.56   39.83   39.84   40.12   40.17
   40.42    40.6   40.63   41.53   41.51   42.19   42.51   42.54   43.41   43.45
   43.53   44.05   44.24   44.25   44.26   45.29   45.21   45.46   46.27   47.07
   47.26   47.53   47.85   47.96   48.18   48.69   48.92   49.13   49.27    49.8
   49.93    50.5   50.75   50.78   50.81
                                                                                
                                                                                
                                                                                
                                                                                
                                                                                
                                                                                
                                                                                
                                                                                
                                                                                
                                                                                
                                                                                
                                                                                
                                                                                
                                                                                
                                                                                
                                                                                
                                                                                
                                                                                
                                                                                
                                        
BR Coef=-1 , 0 , 0 ,, 0 ,,,0.8,-1,,0,
WSPro=,,,, 1 ,,,, 0 ,,,, 0 ,,,,-1 ,-1 ,-1 , 0 , 0 , 0 , 0 , 0
BC Design=,, 0 ,, 0 ,,,,,,
BC Use User HTab Curves=0
BC User HTab FreeFlow(D)= 0

Type RM Length L Ch R = 1 ,1112    ,217.43,126.57,161.14
BEGIN DESCRIPTION:
Survyed Section
END DESCRIPTION:
XS GIS Cut Line= 6
 2418597.7922326 612501.342107492418952.82230005612496.025500014
2419018.60660002612493.6782000062419041.61160004612487.895200014
2419188.92839998612504.6709000022419841.58957887612506.537585124
#Sta/Elev= 30
       0   44.55   12.53    44.2   17.24    42.9   54.62   42.01   67.36   40.49
  185.11   35.83  228.82    36.2   246.9   35.66  253.69   33.63  333.63    30.5
  402.16   29.84  431.45   25.73   432.2   25.59  458.71   21.91  460.88   22.96
  471.26   26.06  489.53   26.92  512.67   25.42  553.85   26.28  573.17    24.3
  648.33   28.72  677.78    26.5  803.68    27.8  942.47   32.54  982.45    35.1
  995.39    37.3 1044.7139.62283 1126.03   41.86 1185.94   46.28 1246.97   47.45
#Mann= 6 ,-1 , 0
       0    .055       0   54.62     .05       0  228.82     .09       0
  431.45     .05       0  460.88     .09       0 1044.71    .045       0
#XS Ineff= 2 , 0
       0  348.66    31.1  538.66       0    31.1
Permanent Ineff=
       F       F
Bank Sta=432.2,460.88
XS Rating Curve= 0 ,0
Exp/Cntr=0.5,0.3

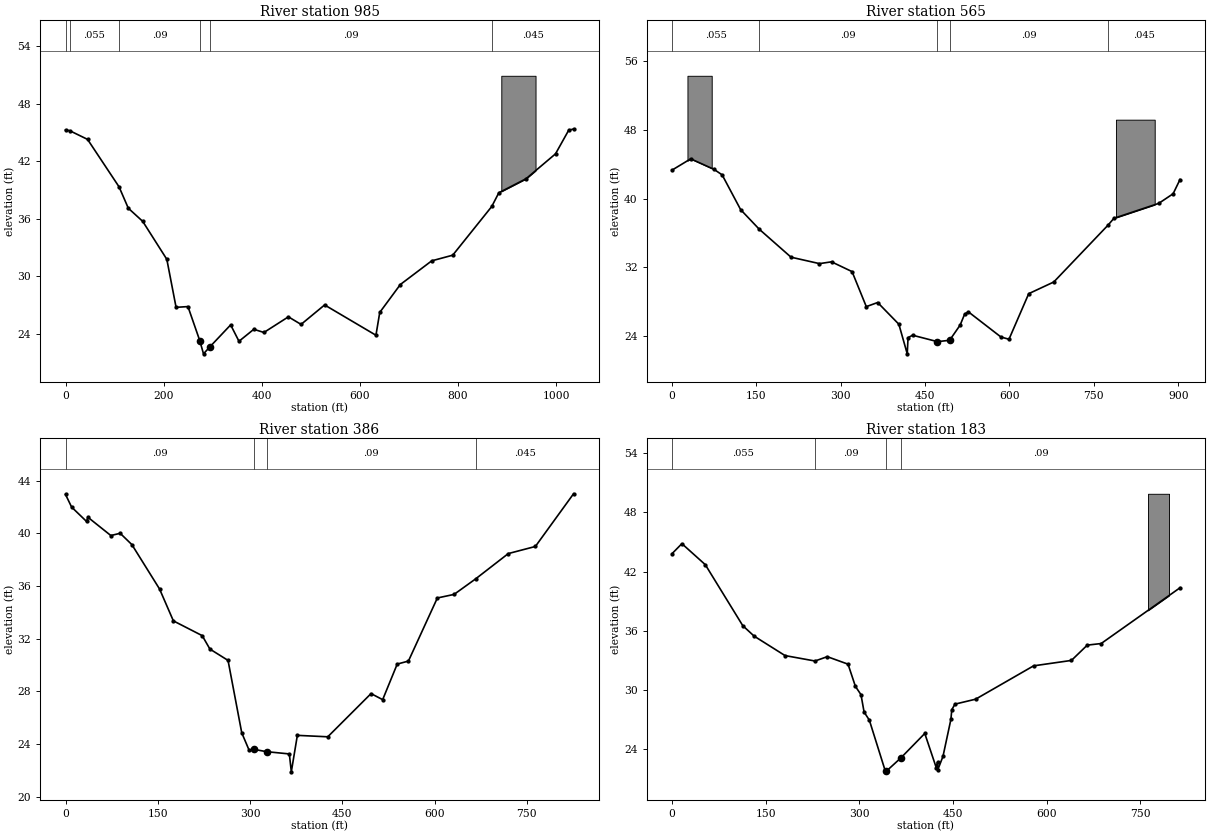
Type RM Length L Ch R = 1 ,985     ,247.45,420.04,206.23
XS GIS Cut Line= 3
2418858.76211208612788.4703180042419125.73234434 612568.00457783
2419814.68778233 612540.44636032
#Sta/Elev= 30
       0   45.26     8.8   45.18   44.95   44.28  109.17   39.33  128.02    37.1
  157.39   35.73  206.56   31.77  225.43   26.76  249.62   26.84  273.64    23.3
  281.33   21.91  294.15   22.63  336.68   24.93  353.66   23.22  383.87   24.47
  404.54   24.14   454.4   25.77  480.21   24.98  528.25   27.01  632.89   23.85
  640.65   26.23  682.62   29.14  746.56   31.61  789.41    32.2  868.99   37.28
  883.41   38.71  938.81   40.17  998.95   42.77 1025.91   45.24 1035.74   45.36
#Mann= 6 ,-1 , 0
       0    .055       0     8.8    .055       0  109.17     .09       0
  273.64     .05       0  294.15     .09       0  868.99    .045       0
#Block Obstruct= 1 ,-1
  888.44  958.26  50.914
Bank Sta=273.64,294.15
XS Rating Curve= 0 ,0
Exp/Cntr=0.3,0.1

Type RM Length L Ch R = 1 ,565     ,149.08,179.16,145.24
XS GIS Cut Line= 3
2419011.79296991612978.7773950992419458.79585181612612.713306651
2419780.71150742612564.885837823
#Sta/Elev= 30
       0   43.31   33.28   44.63   74.81    43.4   89.21   42.76  122.09   38.71
  154.99   36.44  211.67   33.17  262.26   32.42  283.65   32.63  320.18   31.49
  345.49   27.41  365.69   27.89  403.37   25.36  418.28   21.91   419.7   23.79
   427.7   24.08  472.02   23.33  493.61   23.49  512.31   25.26  520.29   26.53
  526.82   26.81  584.89   23.87  599.15   23.61  634.26   28.92  678.78   30.28
  775.05   36.89  785.72    37.7  865.38   39.44  890.96   40.56  903.22   42.22
#Mann= 5 ,-1 , 0
       0    .055       0  154.99     .09       0  472.02     .05       0
  493.61     .09       0  775.05    .045       0
#Block Obstruct= 2 ,-1
   27.52   70.66  54.306  789.32  858.24  49.193
Bank Sta=472.02,493.61
XS Rating Curve= 0 ,0
Exp/Cntr=0.3,0.1

Type RM Length L Ch R = 1 ,386     ,187.15,202.82,192.1
XS GIS Cut Line= 3
2419157.11489448613056.0371524542419661.14283533612616.392342702
2419815.66235007612588.799572244
#Sta/Elev= 30
       0   42.96    9.92      42   34.17   40.91   36.34   41.23   73.69   39.84
   88.86   40.01  107.89   39.15  152.88   35.78  175.35   33.36   222.2   32.24
  234.73   31.22  264.19   30.36  286.48   24.86  298.47   23.54  305.87   23.61
  326.93   23.43  363.84   23.26  367.04    21.9  376.85   24.67   426.3   24.56
  496.63   27.84  515.52   27.38  539.17   30.08   557.4   30.31  604.42    35.1
  631.56   35.37  666.66   36.55  719.73   38.47  763.75   39.01  825.79   43.01
#Mann= 4 ,-1 , 0
       0     .09       0  305.87     .05       0  326.93     .09       0
  666.66    .045       0
Bank Sta=305.87,326.93
XS Rating Curve= 0 ,0
Exp/Cntr=0.3,0.1

Type RM Length L Ch R = 1 ,183     ,275.1,183.21,218.61
XS GIS Cut Line= 2
2419248.02193458613220.789855361 2419859.7753486612684.404415771
#Sta/Elev= 30
       0   43.81   15.88   44.83   53.38    42.7   113.4   36.52   131.6   35.46
  181.07   33.49  229.03   32.94  248.72   33.38  281.94   32.62  293.76   30.37
  302.69   29.53  307.66   27.77  316.07   26.95  342.04   21.71  343.02   21.76
  366.69   23.13  404.84    25.6  423.47   22.09  425.35   22.69  425.58    21.9
  434.02   23.28  446.73   27.04  448.09      28  453.17   28.57  486.21   29.07
   579.1   32.45   639.7      33  665.11   34.55  687.31   34.71   813.6   40.36
#Mann= 4 ,-1 , 0
       0    .055       0  229.03     .09       0  343.02     .05       0
  366.69     .09       0
#Block Obstruct= 1 ,-1
  762.36  796.03  49.885
Bank Sta=343.02,366.69
XS Rating Curve= 0 ,0
Exp/Cntr=0.3,0.1