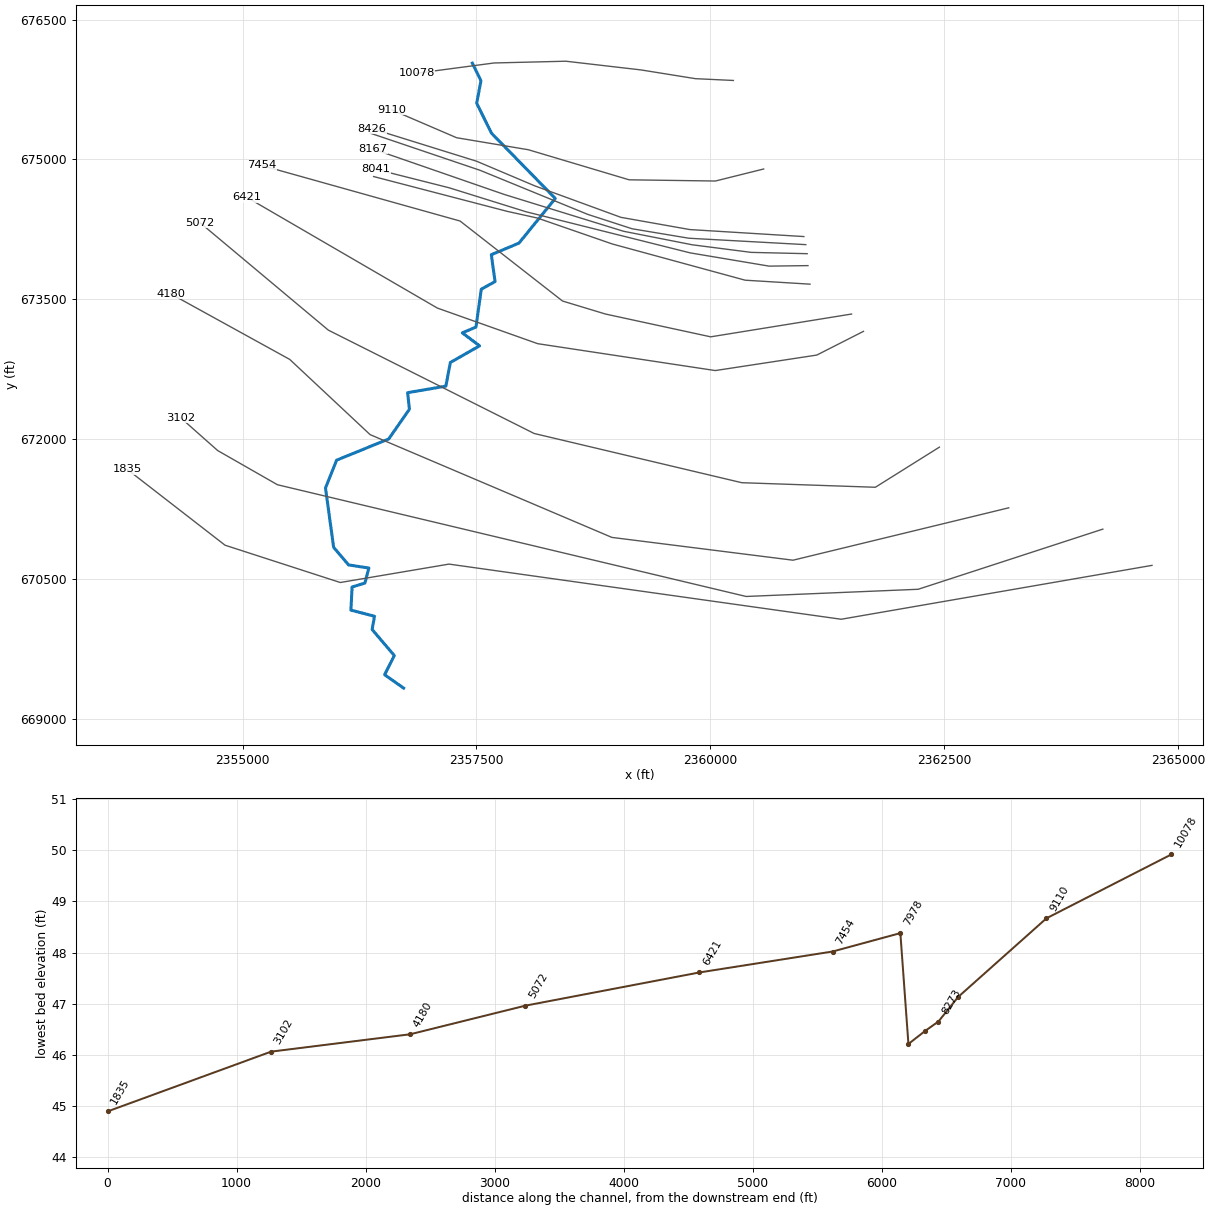
--- DTL_Toinsnot_Swamp_DS.prj (project) ---

Proj Title=DTL_Toisnot_Swamp_DS
Current Plan=p01
Default Exp/Contr=0.3,0.1
English Units
Geom File=g01
Flow File=f01
Flow File=f02
Plan File=p01
Plan File=p02
Y Axis Title=Elevation
X Axis Title(PF)=Main Channel Distance
X Axis Title(XS)=Station
BEGIN DESCRIPTION:
END DESCRIPTION:
DSS Export Rating Curves= 0
DSS Export Rating Curve Sorted= 0
DSS Export Volume Flow Curves= 0
DXF OffsetX= 0
DXF OffsetY= 0
DXF ScaleX= 1
DXF ScaleY= 10

--- DTL_Toinsnot_Swamp_DS.p01 (plan) ---

Plan Title=DTL_Toisnot_Swamp_DS
Program Version=4.00
Short Identifier=Multi Profile
Geom File=g01
Flow File=f01
Subcritical Flow
K Sum by GR= 0
Std Step Tol= 0.01
Critical Tol= 0.01
Num of Std Step Trials= 20
Max Error Tol= 0.3
Flow Tol Ratio= 0.001
Split Flow NTrial= 30
Split Flow Tol= 0.02
Split Flow Ratio= 0.02
Log Output Level= 0
Friction Slope Method= 1
Unsteady Friction Slope Method= 2
Unsteady Bridges Friction Slope Method= 1
Parabolic Critical Depth
Global Vel Dist= 0 , 0 , 0
Global Log Level= 0
CheckData=True
Encroach Param=-1 ,10,10, 2
Encroach River=Toisnot Swamp
Encroach Reach=Downstream
Encroach Node=10078
       1  1957.4  3184.7
Encroach Node=9110
       1 1790.79 3284.02
Encroach Node=8426
       1 2383.33 3515.15
Encroach Node=8273
       1 2491.96 3492.35
Encroach Node=8167
       1 2690.85 3385.05
Encroach Node=8041
       1 2891.58 3307.62
Encroach Node=7978
       1 2921.58 3337.62
Encroach Node=7454
       1 3259.72  4528.3
Encroach Node=6421
       1 3722.69 5484.02
Encroach Node=5072
       1 4917.87 7130.05
Encroach Node=4180
       4       1
Encroach Node=3102
       1    7751    9347
Encroach Node=1835
       4       1
Computation Interval=1HOUR
Output Interval=1HOUR
Run HTab= 0
Run UNet= 0
Run PostProcess= 0
Run WQNet= 0
UNET Theta= 1
UNET Theta Warmup= 1
UNET ZTol= 0.02
UNET ZSATol= 0.05
UNET MxIter= 20
UNET MaxInSteps= 0
UNET DtIC= 0
UNET DtMin= 0
UNET MaxCRTS= 20
UNET WFStab= 2
UNET SFStab= 1
UNET WFX= 1
UNET SFX= 1
UNET DSS MLevel= 4
UNET DZMax Abort= 100
UNET Convert EG Bridges= 0
UNET Use Existing IB Tables=-1
UNET Froude Reduction=False
UNET Froude Limit= 1
UNET Froude Power= 10
UNET Time Slicing=0,0, 5
Instantaneous Interval=1HOUR
Write IC File= 0
Echo Input=False
Echo Output=False
Write Detailed= 0
Detailed Automatic Start=False, 10
WQ ULTIMATE=-1
WQ Max Comp Step=1HOUR
WQ Output Interval=15MIN
WQ Output Selected Increments= 0
WQ Output face flow=0
WQ Output face velocity=0
WQ Output face area=0
WQ Output face dispersion=0
WQ Output cell volume=0
WQ Output cell surface area=0
WQ Output cell continuity=0
WQ Output face conc=0
WQ Output face dconc_dx=0
WQ Output face courant=0
WQ Output face peclet=0
WQ Output face adv mass=0
WQ Output face disp mass=0
WQ Output cell mass=0
WQ Output cell source sink temp=0
WQ Output cell source sink nsm=0
WQ Output MaxMinRange=-1
WQ Daily Max Min Mean=-1
WQ Daily Range=0
WQ Daily Time=0
WQ Create Restart=0
WQ Fixed Restart=0
WQ System Summary=False
Sorting and Armoring Iterations= 10
XS Update Threshold= 0.02
Hydraulics Update Threshold= 0.02
Energy Slope Method= 1
Volume Change Method= 0
XS Weighting Method= 0
Number of US Weighted Cross Sections= 1
Number of DS Weighted Cross Sections= 1
Upstream XS Weight=0.25
Main XS Weight=0.5
Downstream XS Weight=0.25
Number of DS XS's Weighted with US Boundary= 1
Upstream Boundary Weight= 1
Weight of XSs Associated with US Boundary= 0
Number of US XS's Weighted with DS Boundary= 1
Downstream Boundary Weight= 0.5
Weight of XSs Associated with DS Boundary= 0.5
Sediment Output Level= 4
Mass or Volume Output= 0
Output Increment Type= 1
Profile and TS Output Increment= 10
XS Output Flag= 0
XS Output Increment= 10
Disregard all LS=0
Disregard all Conn=0
Disregard all Breaches=0
Disregard all Pumps=0

--- DTL_Toinsnot_Swamp_DS.p02 (plan) ---

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Plan Title=DTL_Toisnot_Swamp_DS_Future
Short Identifier=Future
Geom File=g01
Flow File=f02
Encroach Param=-1 ,0,0, 0

--- DTL_Toinsnot_Swamp_DS.f01 (steady flow) ---

Flow Title=DTL_Toisnot_Swamp_DS
Program Version=4.00
Number of Profiles= 6
Profile Names=100-yr,FW,10-yr,25-yr,50-yr,500-yr
River Rch & RM=Toisnot Swamp,Downstream      ,10078
   14628   14628    7822   10280   12397   20706
River Rch & RM=Toisnot Swamp,Downstream      ,9110
   14630   14630    7820   10280   12400   20710
River Rch & RM=Toisnot Swamp,Downstream      ,7454
   15360   15360    8240   10810   13030   21710
Boundary for River Rch & Prof#=Toisnot Swamp,Downstream      , 1
Up Type= 0
Dn Type= 3
Dn Slope=0.002
Boundary for River Rch & Prof#=Toisnot Swamp,Downstream      , 2
Up Type= 0
Dn Type= 3
Dn Slope=0.002
Boundary for River Rch & Prof#=Toisnot Swamp,Downstream      , 3
Up Type= 0
Dn Type= 3
Dn Slope=0.002
Boundary for River Rch & Prof#=Toisnot Swamp,Downstream      , 4
Up Type= 0
Dn Type= 3
Dn Slope=0.002
Boundary for River Rch & Prof#=Toisnot Swamp,Downstream      , 5
Up Type= 0
Dn Type= 3
Dn Slope=0.002
Boundary for River Rch & Prof#=Toisnot Swamp,Downstream      , 6
Up Type= 0
Dn Type= 3
Dn Slope=0.002
DSS Import GetInterval= 0
DSS Import GetPeak= 0
DSS Import FillOption= 0

--- DTL_Toinsnot_Swamp_DS.f02 (steady flow) ---

Flow Title=DTL_Toisnot_Swamp_DS_Future
Program Version=4.00
Number of Profiles= 3
Profile Names=100-yr-10%,100-yr-20%,100-yr-35%
River Rch & RM=Toisnot Swamp,Downstream      ,10078
   14400   18400   22500
River Rch & RM=Toisnot Swamp,Downstream      ,7454
   15100   19300   23600
Boundary for River Rch & Prof#=Toisnot Swamp,Downstream      , 1
Up Type= 0
Dn Type= 3
Dn Slope=0.002
Boundary for River Rch & Prof#=Toisnot Swamp,Downstream      , 2
Up Type= 0
Dn Type= 3
Dn Slope=0.002
Boundary for River Rch & Prof#=Toisnot Swamp,Downstream      , 3
Up Type= 0
Dn Type= 3
Dn Slope=0.002
DSS Import GetInterval= 0
DSS Import GetPeak= 0
DSS Import FillOption= 0

--- DTL_Toinsnot_Swamp_DS.g01 (geometry) ---

Geom Title=DTL_Toisnot_Swamp_DS
Program Version=4.00

River Reach=Toisnot Swamp   ,Downstream
Reach XY= 30
2357456.09782004 676031.980036782357548.08190441 675842.90164113
2357502.08986223675602.7209763822357660.50689642675280.776681095
2358342.47867681674580.9885682912357953.90454626674101.471556127
2357658.92607936673977.5832807872357698.50941268  673689.0416141
 2357551.6344126673607.7916141452357494.34274596673200.630155802
 2357348.5094126673139.4322391452357533.40524602673000.109322473
  2357220.905246672821.7239057722357172.72816269672567.817655817
2356763.87399599672497.5051557722356783.40524599672320.421822429
2356562.05107935672001.4114058172356004.75941271671773.546822429
2355886.26982932671475.3697391452355973.50941269670838.650989145
2356133.66566265670649.8489057722356349.81149596670617.296822459
2356307.27677371670455.4044613692356170.64505972670413.460443944
 2356157.9323429670165.5624660852356410.06789306670099.880095869
2356384.64245945669957.9214247612356621.94650663669678.241654843
2356518.12598598669472.7193996912356721.01000001669329.629999995

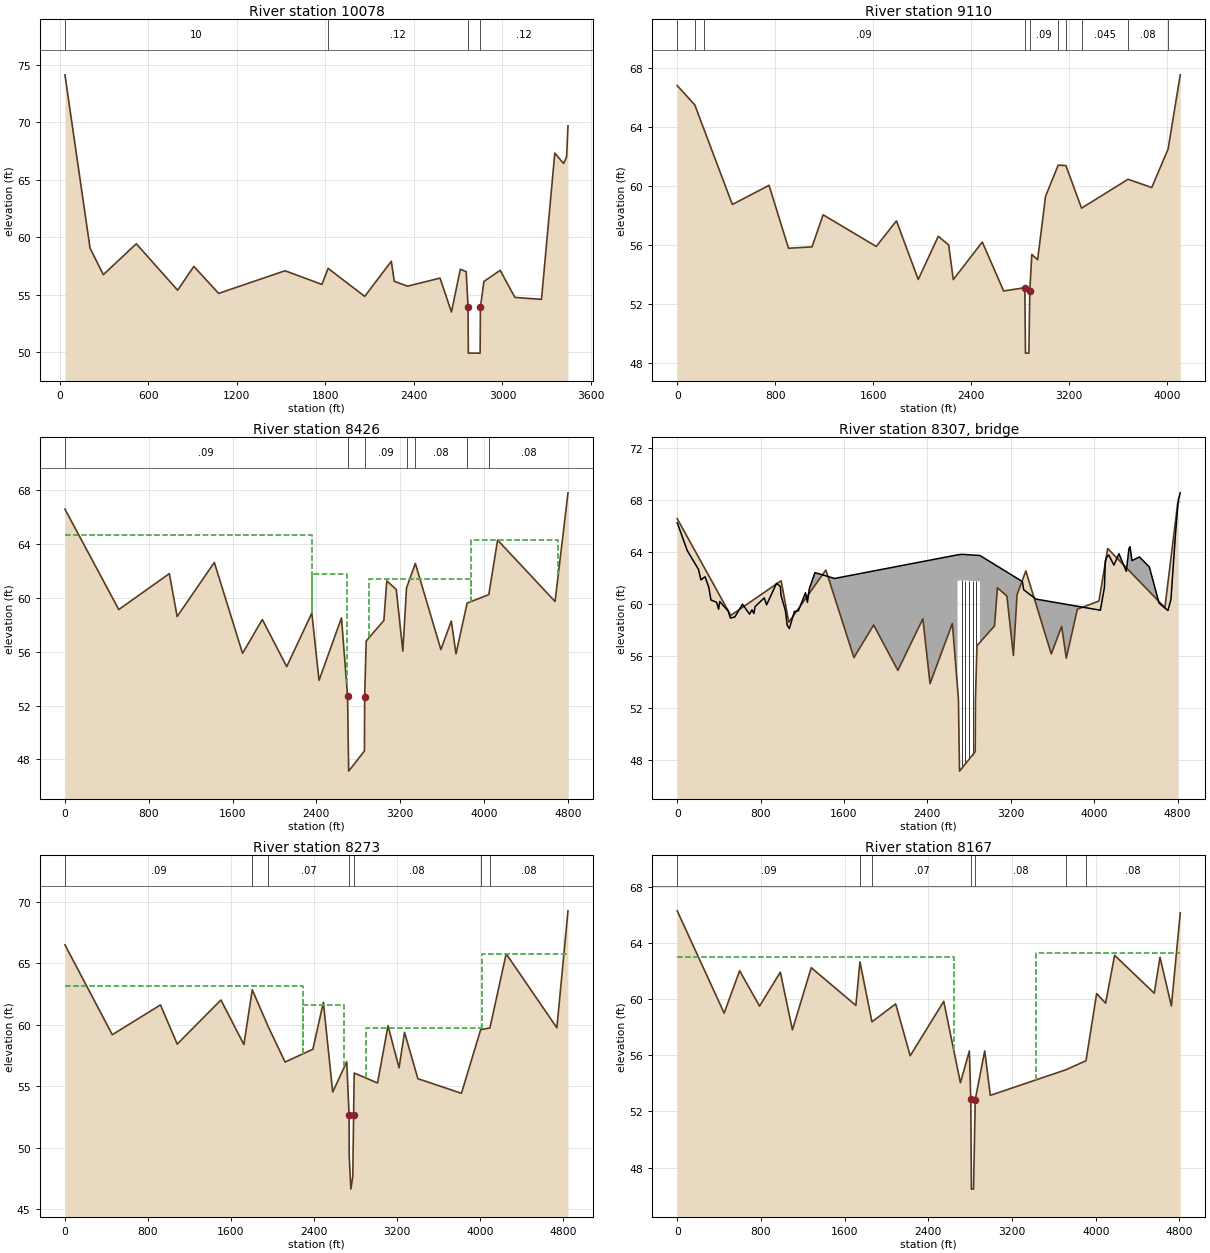
Type RM Length L Ch R = 1 ,10078   ,1144.74,967.69,775.51
BEGIN DESCRIPTION:
Tie in Section 8317
END DESCRIPTION:
XS GIS Cut Line= 6
2360246.09138895675846.1796485022359839.99999262675865.500027329
2359259.99998257675959.062508613 2358455.5000219676052.624989912
2357688.50002232676033.8749710922356859.63382798675923.375947006
#Sta/Elev= 30
    36.7   74.15   206.7   59.06   296.7   56.75     520   59.44     800    55.4
     910   57.47  1077.5   55.12  1527.5   57.09  1777.5    55.9    1819    57.3
  2067.4   54.86  2247.4   57.92  2267.4   56.17  2357.4   55.75  2577.4   56.45
  2654.7    53.5  2714.7   57.22  2754.7   57.01  2767.2   53.92  2769.2   49.92
  2848.9   49.92  2850.9   53.92  2874.7   56.16  2984.7   57.13  3084.7   54.77
  3264.7    54.6  3354.7   67.33  3414.7   66.43  3434.7   67.01  3444.1   69.71
#Mann= 4 ,-1 , 0
    36.7      10       0    1819     .12       0  2767.2    .045       0
  2850.9     .12       0
Bank Sta=2767.2,2850.9
XS Rating Curve= 0 ,0
Exp/Cntr=0.3,0.1

Type RM Length L Ch R = 1 ,9110    ,686.23,684.44,230.19
XS GIS Cut Line= 6
2360569.85656752674896.7397694292360054.00254039674767.776262641
 2359131.9134669674780.6726133082358055.06818524675103.081380263
2357287.73531987675232.0448870512356596.39643866675530.374947518
#Sta/Elev= 30
       0   66.83  143.76   65.52  215.02   63.94   450.4   58.76  750.07   60.06
  909.02   55.79 1101.01   55.88  1191.7   58.06  1625.8   55.91 1790.79   57.65
 1968.74   53.67 2132.43    56.6 2217.43   56.01 2255.02   53.66  2492.1   56.21
 2666.29   52.89 2839.42   53.11 2844.66   48.67 2872.49   48.67 2880.08   52.89
 2896.55   55.37 2944.08   55.01  3008.6   59.31 3112.16   61.43 3174.87    61.4
 3302.75   58.51 3682.71   60.47 3876.22   59.91 4009.72   62.52  4109.1   67.56
#Mann= 10 ,-1 , 0
       0     .09       0  143.76    .045       0  215.02     .09       0
 2839.42     .05       0 2880.08     .09       0 3112.16    .035       0
 3174.87     .08       0 3302.75    .045       0 3682.71     .08       0
 4009.72    .045       0
Bank Sta=2839.42,2880.08
XS Rating Curve= 0 ,0
Exp/Cntr=0.5,0.3

Type RM Length L Ch R = 1 ,8426    ,112.97,152.68,100.8
BEGIN DESCRIPTION:
Surveyed Section
END DESCRIPTION:
XS GIS Cut Line= 6
2360999.61247568674172.0334976322359780.20434584674247.095213905
2359044.46891384674378.0421747422358125.12910001674715.120800003
2357500.45773733674980.3597092182356384.07652132675329.016760722
#Sta/Elev= 30
       0   66.59  513.79   59.13  996.74    61.8 1070.98   58.61 1425.94   62.63
 1695.44   55.88 1884.43   58.39 2116.87   54.89 2356.73   58.87 2425.44   53.87
 2639.71   58.512697.923   52.71 2708.31   47.132858.837   48.632861.181   52.63
2875.446   56.79 3044.26   58.32 3072.14   61.26 3162.91   60.62 3225.34   56.04
 3260.58   60.73 3344.82   62.56  3588.7   56.16 3688.28   58.28 3732.92   55.84
 3838.98   59.61 4046.05   60.24 4129.95   64.29 4678.61   59.73 4801.88    67.8
#Mann= 7 ,-1 , 0
       0     .09       02697.923     .05       02861.181     .09       0
 3260.58    .035       0 3344.82     .08       0 3838.98    .045       0
 4046.05     .08       0
#XS Ineff= 4 ,-1
       0 2356.73   64.64 2356.73 2689.43    61.8 2904.71 3876.62   61.39
 3876.62 4706.23   64.29
Permanent Ineff=
       F       F       F       F
Bank Sta=2697.923,2861.181
XS Rating Curve= 0 ,0
Exp/Cntr=0.5,0.3

Type RM Length L Ch R = 3 ,8307    ,,,
BEGIN DESCRIPTION:
Sandpit Road (SR 1232)
END DESCRIPTION:
Bridge Culvert--1,0,-1,-1, 0
Deck Dist Width WeirC Skew NumUp NumDn MinLoCord MaxHiCord MaxSubmerge Is_Ogee
66,28,2.6,0, 60, 60, , , 0.98, 0, 1,1,,
       0   96.16  203.45  227.77  267.54   303.3  323.52  377.88  397.21  408.18
  489.71  510.06  552.85  626.24  693.74  717.14   735.5  746.99  834.49  857.87
  952.78  989.83   995.4 1037.55 1055.21 1075.91 1124.12 1161.67  1230.6 1249.32
 1267.22 1321.53 1509.75 2689.43 2689.432730.0842904.7092904.709 3311.54  3323.6
 3442.04 4059.52 4098.66 4107.24 4122.19 4139.45 4189.71 4237.87  4308.3 4333.82
 4344.34 4362.96 4434.57 4529.89 4622.68 4707.94 4737.03 4778.33 4806.99 4826.17
   66.28   64.13   62.69   61.87   62.11   61.28   60.32   60.14   59.61    60.2
   59.46   58.93   59.01      60   59.23   59.56   59.28   59.81   60.48   59.95
   61.61   61.36   60.69   59.51   58.37   58.12   59.44   59.48   60.88   60.14
   61.19   62.43   61.98    63.8    63.8   63.84   63.75   63.75   61.74   61.11
   60.39   59.53   61.29   63.33   63.64   63.79   63.01   63.89   62.53   64.28
   64.43   63.36   63.64   62.86   60.08   59.51   60.37    65.2   68.03   68.58
                                                                                
                                                                                
                                                                                
                                    61.8   61.84   61.75
                                                                                
                                                                                
       0   96.16  203.45  227.77  267.54   303.3  323.52  377.88  397.21  408.18
  489.71  510.06  552.85  626.24  693.74  717.14   735.5  746.99  834.49  857.87
  952.78  989.83   995.4 1037.55 1055.21 1075.91 1124.12 1161.67  1230.6 1249.32
 1267.22 1321.53 1509.75 2689.43 2689.432730.0842904.7092904.709 3311.54  3323.6
 3442.04 4059.52 4098.66 4107.24 4122.19 4139.45 4189.71 4237.87  4308.3 4333.82
 4344.34 4362.96 4434.57 4529.89 4622.68 4707.94 4737.03 4778.33 4806.99 4826.17
   66.28   64.13   62.69   61.87   62.11   61.28   60.32   60.14   59.61    60.2
   59.46   58.93   59.01      60   59.23   59.56   59.28   59.81   60.48   59.95
   61.61   61.36   60.69   59.51   58.37   58.12   59.44   59.48   60.88   60.14
   61.19   62.43   61.98    63.8    63.8   63.84   63.75   63.75   61.74   61.11
   60.39   59.53   61.29   63.33   63.64   63.79   63.01   63.89   62.53   64.28
   64.43   63.36   63.64   62.86   60.08   59.51   60.37    65.2   68.03   68.58
                                                                                
                                                                                
                                                                                
                                    61.8   61.84   61.75
                                                                                
                                                                                
Pier Skew, UpSta & Num, DnSta & Num=  ,2730.084, 2 ,2730.084, 2 , 0 , 0 , 0 ,,
       1       1
      45   61.84
       1       1
      45   61.84
Pier Skew, UpSta & Num, DnSta & Num=  ,2764.649, 2 ,2764.649, 2 , 0 , 0 , 0 ,,
       1       1
      45   61.84
       1       1
      45   61.84
Pier Skew, UpSta & Num, DnSta & Num=  ,2800.848, 2 ,2800.848, 2 , 0 , 0 , 0 ,,
       1       1
      45   61.84
       1       1
      45   61.84
Pier Skew, UpSta & Num, DnSta & Num=  ,2835.077, 2 ,2835.077, 2 , 0 , 0 , 0 ,,
       1       1
      45   61.84
       1       1
      45   61.84
Pier Skew, UpSta & Num, DnSta & Num=  ,2870.329, 2 ,2870.329, 2 , 0 , 0 , 0 ,,
       1       1
      45   61.84
       1       1
      45   61.84
BR Coef=-1 , 0 , 0 ,, 0 ,,,0.8,0,,0,
WSPro=,,,, 1 ,,,, 0 ,,,, 0 ,,,,-1 ,-1 ,-1 , 0 , 0 , 0 , 0 , 0
BC Design=,, 0 ,, 0 ,,,,,,
BC Use User HTab Curves=0
BC User HTab FreeFlow(D)= 0

Type RM Length L Ch R = 1 ,8273    ,81.2,105.87,189.54
BEGIN DESCRIPTION:
Surveyed Section
END DESCRIPTION:
XS GIS Cut Line= 6
2361020.25346231674085.3413537742359770.23552661674154.138431847
2359163.88635302674255.5508367572358688.85741705674410.146052584
2357538.28800981674882.7274930182356367.21220495675280.248291314
#Sta/Elev= 30
       0   66.49  456.67   59.19  920.93   61.61 1082.65   58.43 1504.02   62.01
 1725.62   58.39 1806.05   62.84 1961.65   59.82 2122.89   56.97 2390.79   58.01
 2491.96   61.82 2582.05   54.532717.205   56.992739.576   52.712741.271   49.33
2756.717   46.652775.569   47.66 2783.39   52.672789.377   56.083014.171   55.27
 3115.41   59.92  3221.4    56.5 3274.64   59.38 3403.19   55.62 3823.36   54.43
 4008.63    59.6 4097.81   59.74 4254.71   65.76 4743.59   59.75 4850.67   69.25
#Mann= 7 ,-1 , 0
       0     .09       0 1806.05    .035       0 1961.65     .07       0
2739.576     .05       0 2783.39     .08       0 4008.63    .045       0
 4097.81     .08       0
#XS Ineff= 4 ,-1
       0  2294.4   63.18  2294.4 2689.43   61.62 2904.71 4025.33   59.71
 4025.33 4850.67   65.76
Permanent Ineff=
       F       F       F       F
Bank Sta=2739.576,2783.39
XS Rating Curve= 0 ,0
Exp/Cntr=0.5,0.3

Type RM Length L Ch R = 1 ,8167    ,78.63,126.67,139.37
XS GIS Cut Line= 6
2361034.70215292673988.328716636 2360436.3373069674002.420180604
 2359805.6735625674083.8934873042359072.41380228674228.734921426
2357795.99866407674624.0313353692356389.82974114675112.871175528
#Sta/Elev= 30
       0   66.29  448.66      59  596.47   62.02  786.94    59.5   985.6   61.92
 1101.29   57.81 1281.02   62.24 1707.67   59.55 1746.63   62.66 1861.25   58.38
 2088.03   59.66 2226.99   55.96 2547.52   59.84 2706.93   54.04 2792.62   56.31
 2805.97   52.85 2812.09   46.46 2832.52   46.47 2848.74   52.84 2939.22   56.31
 2992.75   53.14 3716.84   54.97  3907.4   55.61    4009   60.39 4094.86   59.71
 4180.76   63.12 4559.72   60.42 4614.67   62.98  4723.7   59.51 4808.32   66.15
#Mann= 7 ,-1 , 0
       0     .09       0 1746.63    .035       0 1861.25     .07       0
 2805.97     .05       0 2848.74     .08       0 3716.84    .032       0
  3907.4     .08       0
#XS Ineff= 2 , 0
       0    2646      63 3427.01       0   63.27
Permanent Ineff=
       F       F
Bank Sta=2805.97,2848.74
XS Rating Curve= 0 ,0
Exp/Cntr=0.5,0.3

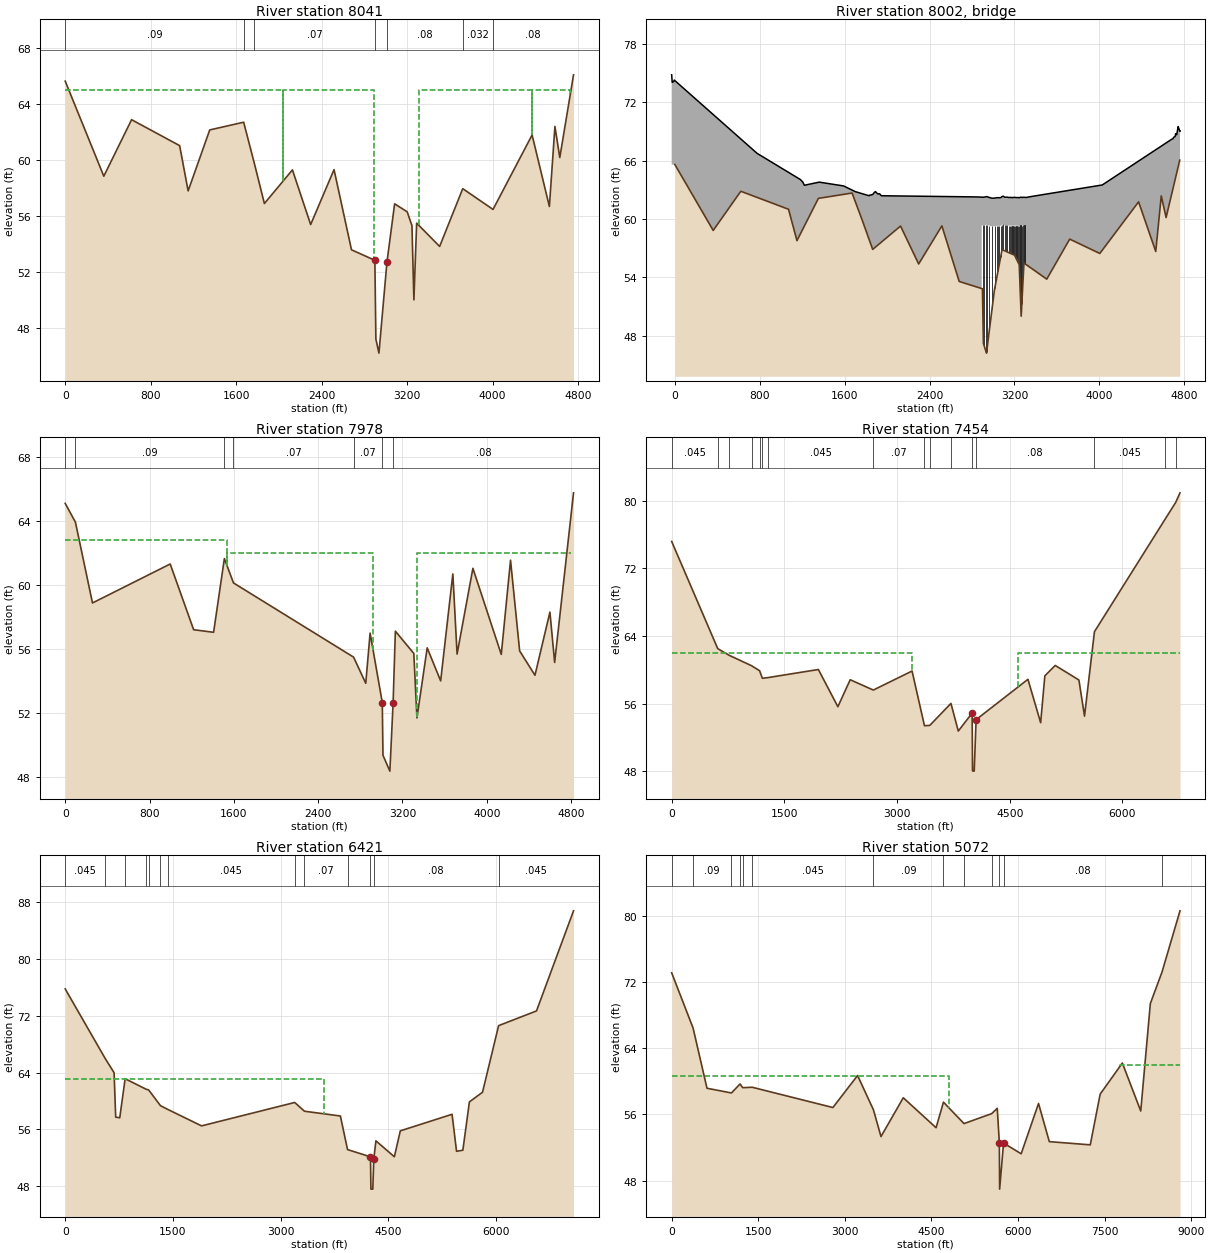
Type RM Length L Ch R = 1 ,8041    ,82.04,62.45,74.19
BEGIN DESCRIPTION:
Surveyed Section
END DESCRIPTION:
XS GIS Cut Line= 6
2361043.30108781673860.5174239432360628.00442147673854.905306831
2359784.31614892673997.0789403472358029.60769999674438.092900008
2357208.79952054674694.9981273712356420.13318078674894.770686522
#Sta/Elev= 30
       0   65.61  361.35   58.83  621.42   62.86 1071.14   61.01 1150.68   57.78
  1352.7   62.13 1670.33   62.68 1768.14   59.81 1864.29   56.88 2126.85   59.28
 2297.52   55.38 2516.24    59.3 2679.66   53.582898.384   52.832907.874   47.21
2936.447   46.213011.259   52.683083.398   56.863200.725   56.293245.381   55.31
3263.686   50.013289.544   55.48 3504.65   53.82 3721.04   57.94 4004.55   56.46
 4370.07   61.77 4531.83   56.67 4583.72   62.38 4629.31   60.16 4757.88   66.06
#Mann= 7 ,-1 , 0
       0     .09       0 1670.33    .035       0 1768.14     .07       0
2898.384     .05       03011.259     .08       0 3721.04    .032       0
 4004.55     .08       0
#XS Ineff= 4 ,-1
       0 2040.45      65 2040.45 2891.58      65 3307.62 4370.07      65
 4370.07 4725.13      65
Permanent Ineff=
       F       F       F       F
Bank Sta=2898.384,3011.259
XS Rating Curve= 0 ,0
Exp/Cntr=0.5,0.3

Type RM Length L Ch R = 3 ,8002    ,,,
BEGIN DESCRIPTION:
Railroad
END DESCRIPTION:
Bridge Culvert--1,0,-1,-1, 0
Deck Dist Width WeirC Skew NumUp NumDn MinLoCord MaxHiCord MaxSubmerge Is_Ogee
32,10,2.6,0, 68, 68, , , 0.98, 0, 1,1,,
     -30  -24.79  -12.31   -5.52  775.11 1182.69 1206.47 1220.23 1360.77 1589.87
  1701.4 1830.61  1835.5  1847.3 1864.02 1881.52 1891.11 1897.34 1913.61  1929.9
 1946.01 2839.36 2891.58 2891.58  2904.6 2916.46 2929.35 2937.35 2963.75 2989.05
 3014.48 3038.52 3045.89 3057.74 3070.01 3082.99 3094.95 3107.78 3119.98 3132.45
 3145.03 3157.33 3170.05 3182.31 3194.79 3207.27  3219.8 3231.73 3244.81 3257.18
 3269.54 3282.23 3294.67 3307.62 3307.62 3357.83 4027.84 4680.27 4694.53 4699.02
 4714.54 4718.62 4726.37 4729.35 4742.89 4743.65 4759.79 4760.29
   74.84   74.07   74.14    74.3   66.76   64.07    63.8   63.48    63.8   63.41
   62.82    62.4   62.46   62.48   62.53   62.76   62.83   62.73   62.59    62.6
    62.4   62.28   62.26   62.26   62.24   62.27   62.28   62.32   62.22   62.15
   62.16   62.21   62.19    62.2    62.2   62.31   62.36   62.25   62.25   62.26
   62.22   62.23   62.22   62.21   62.23   62.23   62.21   62.22   62.19   62.25
   62.23   62.24   62.24   62.22   62.22   62.32   63.51    68.2   68.27    68.4
   68.49   68.78    68.7   68.68   69.52   69.49   69.02   69.04
                                                                                
                                                                                
                           59.36   59.34   59.37   59.38   59.42   59.32   59.25
   59.26   59.31   59.29    59.3    59.3   59.41   59.46   59.35   59.35   59.36
   59.32   59.33   59.32   59.31   59.33   59.33   59.31   59.32   59.29   59.35
   59.33   59.34   59.34   59.32
                                                                
       0    5.21   17.69   24.48  805.11 1212.69 1236.47 1250.23 1390.77 1619.87
  1731.4 1860.61  1865.5  1877.3 1894.02 1911.52 1921.11 1927.34 1943.61  1959.9
 1976.012869.361 2921.58 2921.582934.6022946.459 2959.352967.3452993.7513019.048
3044.4773068.5233075.8863087.7353100.0123112.9873124.9493137.7763149.9833162.451
3175.0273187.3323200.0543212.3113224.7943237.269  3249.83261.7343274.8063287.181
3299.5373312.229 3324.673337.6243337.6243387.833 4057.84 4710.27 4724.53 4729.02
 4744.54 4748.62 4756.37 4759.35 4772.89 4773.65 4789.79 4790.29
   74.84   74.07   74.14    74.3   66.76   64.07    63.8   63.48    63.8   63.41
   62.82    62.4   62.46   62.48   62.53   62.76   62.83   62.73   62.59    62.6
    62.4   62.28   62.26   62.26   62.24   62.27   62.28   62.32   62.22   62.15
   62.16   62.21   62.19    62.2    62.2   62.31   62.36   62.25   62.25   62.26
   62.22   62.23   62.22   62.21   62.23   62.23   62.21   62.22   62.19   62.25
   62.23   62.24   62.24   62.22   62.22   62.32   63.51    68.2   68.27    68.4
   68.49   68.78    68.7   68.68   69.52   69.49   69.02   69.04
                                                                                
                                                                                
                           59.36   59.34   59.37   59.38   59.42   59.32   59.25
   59.26   59.31   59.29    59.3    59.3   59.41   59.46   59.35   59.35   59.36
   59.32   59.33   59.32   59.31   59.33   59.33   59.31   59.32   59.29   59.35
   59.33   59.34   59.34   59.32
                                                                
Pier Skew, UpSta & Num, DnSta & Num=  ,2904.6, 2 ,2934.602, 2 , 0 , 0 , 0 ,,
       1       1
      45   59.46
       1       1
      45   59.46
Pier Skew, UpSta & Num, DnSta & Num=  ,2916.46, 2 ,2946.459, 2 , 0 , 0 , 0 ,,
       1       1
      45   59.46
       1       1
      45   59.46
Pier Skew, UpSta & Num, DnSta & Num=  ,2929.35, 2 ,2959.35, 2 , 0 , 0 , 0 ,,
       1       1
      45   59.46
       1       1
      45   59.46
Pier Skew, UpSta & Num, DnSta & Num=  ,2937.35, 2 ,2967.345, 2 , 0 , 0 , 0 ,,
       1       1
      45   59.46
       1       1
      45   59.46
Pier Skew, UpSta & Num, DnSta & Num=  ,2963.75, 2 ,2993.751, 2 , 0 , 0 , 0 ,,
       1       1
      45   59.46
       1       1
      45   59.46
Pier Skew, UpSta & Num, DnSta & Num=  ,2989.05, 2 ,3019.048, 2 , 0 , 0 , 0 ,,
       1       1
      45   59.46
       1       1
      45   59.46
Pier Skew, UpSta & Num, DnSta & Num=  ,3014.48, 2 ,3044.477, 2 , 0 , 0 , 0 ,,
       1       1
      45   59.46
       1       1
      45   59.46
Pier Skew, UpSta & Num, DnSta & Num=  ,3038.52, 2 ,3068.523, 2 , 0 , 0 , 0 ,,
       1       1
      45   59.46
       1       1
      45   59.46
Pier Skew, UpSta & Num, DnSta & Num=  ,3045.89, 2 ,3075.886, 2 , 0 , 0 , 0 ,,
       1       1
      45   59.46
       1       1
      45   59.46
Pier Skew, UpSta & Num, DnSta & Num=  ,3057.74, 2 ,3087.735, 2 , 0 , 0 , 0 ,,
       1       1
      45   59.46
       1       1
      45   59.46
Pier Skew, UpSta & Num, DnSta & Num=  ,3070.01, 2 ,3100.012, 2 , 0 , 0 , 0 ,,
       1       1
      45   59.46
       1       1
      45   59.46
Pier Skew, UpSta & Num, DnSta & Num=  ,3082.99, 2 ,3112.987, 2 , 0 , 0 , 0 ,,
       1       1
      45   59.46
       1       1
      45   59.46
Pier Skew, UpSta & Num, DnSta & Num=  ,3094.95, 2 ,3124.949, 2 , 0 , 0 , 0 ,,
       1       1
      45   59.46
       1       1
      45   59.46
Pier Skew, UpSta & Num, DnSta & Num=  ,3107.78, 2 ,3137.776, 2 , 0 , 0 , 0 ,,
       1       1
      45   59.46
       1       1
      45   59.46
Pier Skew, UpSta & Num, DnSta & Num=  ,3119.98, 2 ,3149.983, 2 , 0 , 0 , 0 ,,
       1       1
      45   59.46
       1       1
      45   59.46
Pier Skew, UpSta & Num, DnSta & Num=  ,3132.45, 2 ,3162.451, 2 , 0 , 0 , 0 ,,
       1       1
      45   59.46
       1       1
      45   59.46
Pier Skew, UpSta & Num, DnSta & Num=  ,3145.03, 2 ,3175.027, 2 , 0 , 0 , 0 ,,
       1       1
      45   59.46
       1       1
      45   59.46
Pier Skew, UpSta & Num, DnSta & Num=  ,3157.33, 2 ,3187.332, 2 , 0 , 0 , 0 ,,
       1       1
      45   59.46
       1       1
      45   59.46
Pier Skew, UpSta & Num, DnSta & Num=  ,3170.05, 2 ,3200.054, 2 , 0 , 0 , 0 ,,
       1       1
      45   59.46
       1       1
      45   59.46
Pier Skew, UpSta & Num, DnSta & Num=  ,3182.31, 2 ,3212.311, 2 , 0 , 0 , 0 ,,
       1       1
      45   59.46
       1       1
      45   59.46
Pier Skew, UpSta & Num, DnSta & Num=  ,3194.79, 2 ,3224.794, 2 , 0 , 0 , 0 ,,
       1       1
      45   59.46
       1       1
      45   59.46
Pier Skew, UpSta & Num, DnSta & Num=  ,3207.27, 2 ,3237.269, 2 , 0 , 0 , 0 ,,
       1       1
      45   59.46
       1       1
      45   59.46
Pier Skew, UpSta & Num, DnSta & Num=  ,3219.8, 2 ,3249.8, 2 , 0 , 0 , 0 ,,
       1       1
      45   59.46
       1       1
      45   59.46
Pier Skew, UpSta & Num, DnSta & Num=  ,3231.73, 2 ,3261.734, 2 , 0 , 0 , 0 ,,
       1       1
      45   59.46
       1       1
      45   59.46
Pier Skew, UpSta & Num, DnSta & Num=  ,3244.81, 2 ,3274.806, 2 , 0 , 0 , 0 ,,
       1       1
      45   59.46
       1       1
      45   59.46
Pier Skew, UpSta & Num, DnSta & Num=  ,3257.18, 2 ,3287.181, 2 , 0 , 0 , 0 ,,
       1       1
      45   59.46
       1       1
      45   59.46
Pier Skew, UpSta & Num, DnSta & Num=  ,3269.54, 2 ,3299.537, 2 , 0 , 0 , 0 ,,
       1       1
      45   59.46
       1       1
      45   59.46
Pier Skew, UpSta & Num, DnSta & Num=  ,3282.23, 2 ,3312.229, 2 , 0 , 0 , 0 ,,
       1       1
      45   59.46
       1       1
      45   59.46
Pier Skew, UpSta & Num, DnSta & Num=  ,3294.67, 2 ,3324.67, 2 , 0 , 0 , 0 ,,
       1       1
      45   59.46
       1       1
      45   59.46
BR Coef=-1 , 0 , 0 ,, 0 ,,,0.8,-1,,0,
WSPro=,,,, 1 ,,,, 0 ,,,, 0 ,,,,-1 ,-1 ,-1 , 0 , 0 , 0 , 0 , 0
BC Design=,, 0 ,, 0 ,,,,,,
BC Use User HTab Curves=0
BC User HTab FreeFlow(D)= 0

Type RM Length L Ch R = 1 ,7978    ,593.95,524.8,264.76
BEGIN DESCRIPTION:
Surveyed Section
END DESCRIPTION:
XS GIS Cut Line= 6
2361065.23350029673661.5476123392360372.07701989 673704.05948092
2358952.42141706674092.316023663    2358151.2087674370.683200002
2357828.61300002674442.4021000122356400.54036929674815.746346697
#Sta/Elev= 30
       0   65.08   96.98   63.91  258.88   58.87  996.27    61.3 1218.68    57.2
  1408.2   57.04 1510.41   61.64 1596.83   60.12  2736.6   55.49 2852.09   53.86
 2893.31   56.99 3008.86   52.663015.418   49.373080.824   48.383111.514   52.64
3133.012   57.113308.011   55.723337.818    51.7 3434.88   56.07 3562.81   54.01
 3678.47   60.68 3718.67   55.68 3868.77   61.03 4137.97   55.66 4225.91   61.54
 4312.21   55.88 4457.77   54.36 4599.63    58.3 4644.44   55.16 4823.66   65.74
#Mann= 7 ,-1 , 0
       0    .045       0   96.98     .09       0 1510.41    .035       0
 1596.83     .07       0  2736.6     .07       0 3008.86     .05       0
3111.514     .08       0
#XS Ineff= 3 ,-1
       0 1537.53   62.78 1537.53 2921.58      62 3337.62 4801.06      62
Permanent Ineff=
       F       F       F
Bank Sta=3008.86,3111.514
XS Rating Curve= 0 ,0
Exp/Cntr=0.5,0.3

Type RM Length L Ch R = 1 ,7454    ,737.73,1032.27,956.79
XS GIS Cut Line= 6
2361509.34403138673341.116318852 2360003.4851761673096.658712476
2358878.98018681673341.1163188522358419.92330486673480.607177183
2357324.76218279674338.5996485952355202.33778703674934.979912385
#Sta/Elev= 30
       0   75.19  613.05   62.51  768.01   61.71 1063.03   60.49 1169.95    59.9
 1207.84      59 1278.89   59.08 1952.78   60.04 2212.54   55.64  2376.5   58.83
 2684.31   57.61 3200.01   59.86 3365.04   53.39 3436.09   53.43 3717.58   56.03
 3815.53   52.76 3999.74   54.89 4004.84   48.04  4027.2   48.02 4052.52   54.11
 4742.56   58.88 4911.59   53.75 4967.52   59.29 5105.81   60.52 5420.89    58.8
  5495.6   54.53 5627.79   64.51 6568.35   77.82  6709.1    79.8 6766.61   80.94
#Mann= 16 ,-1 , 0
       0    .045       0  613.05     .09       0  768.01    .045       0
 1063.03     .09       0 1169.95    .035       0 1207.84    .085       0
 1278.89    .045       0 2684.31     .07       0 3365.04     .08       0
 3436.09     .07       0 3717.58     .08       0 3999.74     .05       0
 4052.52     .08       0 5627.79    .045       0 6568.35     .08       0
  6709.1    .045       0
#XS Ineff= 2 , 0
       0 3200.01      62 4608.34       0      62
Permanent Ineff=
       F       F
Bank Sta=3999.74,4052.52
XS Rating Curve= 0 ,0
Exp/Cntr=0.3,0.1

Type RM Length L Ch R = 1 ,6421    ,989.33,1348.8,785.79
XS GIS Cut Line= 6
2361636.46198671673155.3285379862361137.76846971672901.092627361
2360052.37669739672734.8614550382358154.52548115673023.163782552
2357082.03489189673405.075065553 2355045.8849189674592.739263445
#Sta/Elev= 30
       0   75.75   557.2   65.97  680.83   63.97  703.36   57.73  759.66   57.64
  834.74   63.13 1125.72   61.66 1162.54   61.55  1326.859.34056 1431.58    58.8
 1899.32    56.5 3196.63   59.79 3332.57   58.56 3832.86   57.89 3932.25   53.17
 4251.81   52.15 4257.99   47.61 4284.24   47.61 4297.98   51.82 4327.39    54.4
 4584.62   52.16 4667.27    55.8 5388.16   58.13 5450.65   52.93 5538.59   53.08
 5629.55   59.87 5812.57   61.23 6036.43   70.59 6564.37   72.66 7080.03   86.73
#Mann= 13 ,-1 , 0
       0    .045       0   557.2     .09       0  834.74    .045       0
 1125.72    .035       0 1162.54    .045       0  1326.8    .085       0
 1431.58    .045       0 3196.63     .09       0 3332.57     .07       0
 3932.25     .08       0 4251.81     .05       0 4297.98     .08       0
 6036.43    .045       0
#XS Ineff= 2 , 0
       0 3610.58   63.07               0
Permanent Ineff=
       F       F
Bank Sta=4251.81,4297.98
XS Rating Curve= 0 ,0
Exp/Cntr=0.3,0.1

Type RM Length L Ch R = 1 ,5072    ,741.28,892.63,847.9
XS GIS Cut Line= 6
2362448.06123981671913.4838976412361763.57994199671483.238510415
2360335.94752079671532.1300317052358116.27245495672060.158461466
2355917.00929143673168.1788972772354547.19140194674318.946744323
#Sta/Elev= 30
       0    73.1  370.76   66.43  611.98   59.15 1035.67   58.58 1185.38   59.67
 1229.42   59.22 1394.98   59.27 2793.23   56.82 3220.78   60.69 3495.38   56.55
 3626.52   53.31 4012.72      58 4580.71   54.38 4708.95   57.47 5064.74   54.88
 5543.82   56.08 5640.92   56.72 5676.92   52.56 5681.87   46.96  5749.9   52.53
 6054.87   51.23 6355.97   57.31 6542.56    52.7 7252.15   52.31 7423.79   58.44
 7808.14    62.2 8126.59    56.4 8292.84   69.38 8494.95   73.19 8806.71   80.59
#Mann= 13 ,-1 , 0
       0    .045       0  370.76     .09       0 1035.67    .045       0
 1185.38    .035       0 1229.42    .085       0 1394.98    .045       0
 3495.38     .09       0 4708.95    .085       0 5064.74     .07       0
 5543.82     .08       0 5676.92     .05       0  5749.9     .08       0
 8494.95    .045       0
#XS Ineff= 2 , 0
       0 4807.21   60.69 7772.81       0   62.02
Permanent Ineff=
       F       F
Bank Sta=5676.92,5749.9
XS Rating Curve= 0 ,0
Exp/Cntr=0.3,0.1

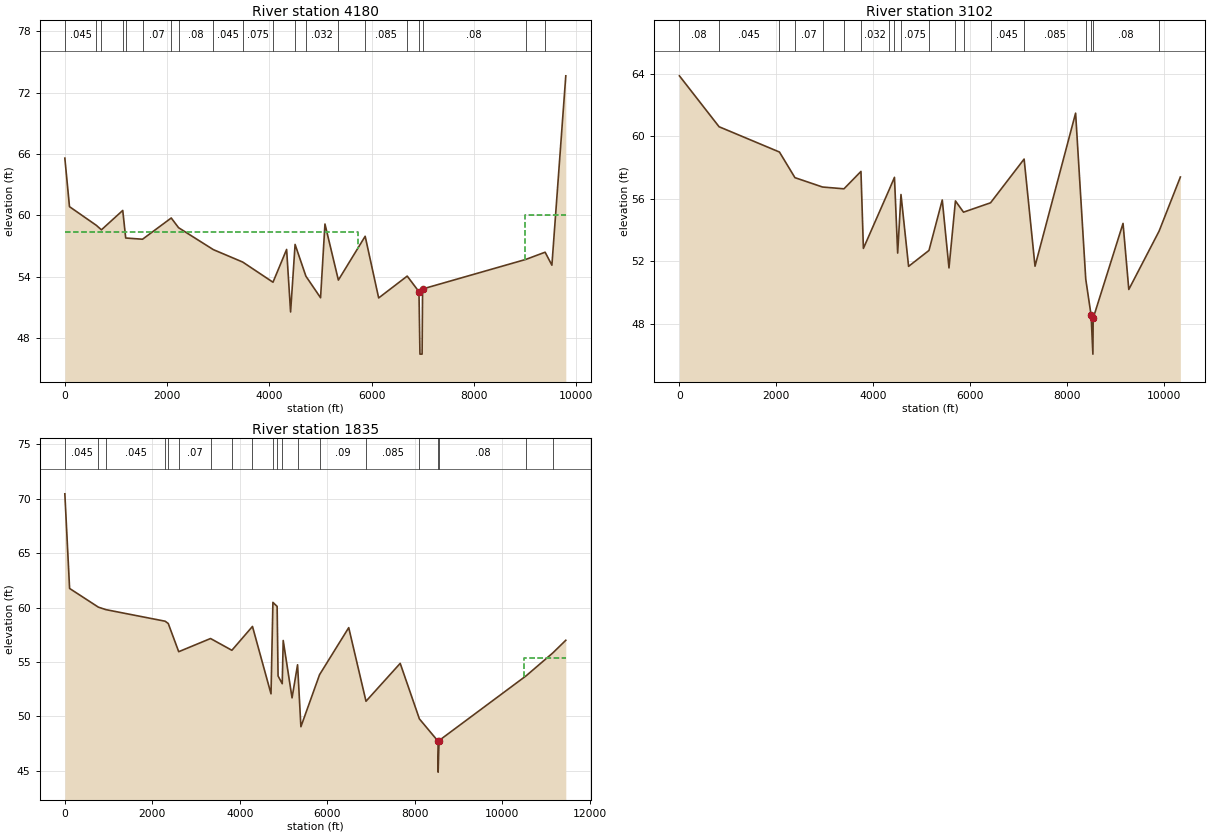
Type RM Length L Ch R = 1 ,4180    ,1040.36,1077.56,1000.93
XS GIS Cut Line= 6
2363189.21151249671262.7916992012360883.53255905670700.974170029
2358947.42831659670945.4317764192356363.04258868672047.754408211
 2355504.0616385672854.4116456962354229.29304343673559.345623776
#Sta/Elev= 30
       0   65.59   90.94   60.84  616.51   59.01  715.51   58.57 1133.05   60.47
 1190.88   57.77 1520.21   57.65 2081.83   59.73 2224.93   58.78 2906.13   56.63
  3480.555.41402 4072.51   53.44 4338.98   56.65 4416.79   50.53 4504.75   57.14
 4716.46   54.03 5003.02   51.92  5089.1   59.14  5351.6   53.65 5875.98   57.94
 6139.98    51.9 6698.32   54.04 6928.65   52.51 6947.56    46.4  6989.7    46.4
 6999.22   52.78 9016.36   55.67 9396.66   56.38 9528.94   55.11 9800.87   73.65
#Mann= 20 ,-1 , 0
       0    .045       0  616.51     .09       0  715.51    .045       0
 1133.05     .09       0 1190.88    .045       0 1520.21     .07       0
 2081.83    .045       0 2224.93     .08       0 2906.13    .045       0
  3480.5    .075       0 4072.51     .09       0 4504.75    .045       0
 4716.46    .032       0  5351.6    .045       0 5875.98    .085       0
 6698.32     .08       0 6928.65     .05       0 6999.22     .08       0
 9016.36    .045       0 9396.66     .08       0
#XS Ineff= 2 , 0
       0 5727.62    58.4 8994.83       0      60
Permanent Ineff=
       F       F
Bank Sta=6928.65,6999.22
XS Rating Curve= 0 ,0
Exp/Cntr=0.3,0.1

Type RM Length L Ch R = 1 ,3102    ,1014.77,1266.88,1125.05
BEGIN DESCRIPTION:
Surveyed Section
END DESCRIPTION:
XS GIS Cut Line= 6
2364195.03307788671034.1958888922362221.25112817670389.127086654
2360382.48357891670311.9760006672355372.48053287 671510.45068413
2354734.21784078671876.6669828892354338.94891961672227.861611009
#Sta/Elev= 30
       0   63.88  819.46   60.62 2066.24      59 2385.96   57.36 2956.06   56.76
  3398.956.64525 3749.66   57.76 3800.08   52.83 4331.14   56.58 4441.85   57.38
 4507.92   52.53 4576.36   56.28 4733.55   51.68 5154.7452.69992 5428.95   55.93
 5567.73   51.58 5701.05   55.87 5867.63   55.15 6426.36   55.75 7119.59   58.55
 7344.82   51.69 8183.02   61.498392.557   50.868503.147   48.558540.172   46.06
8546.055   48.36 9162.67   54.43 9281.71    50.2 9908.03   53.9410346.74    57.4
#Mann= 19 ,-1 , 0
       0     .08       0  819.46    .045       0 2066.24    .045       0
 2385.96     .07       0 2956.06     .08       0  3398.9    .045       0
 3749.66    .032       0 4331.14    .075       0 4441.85    .032       0
 4576.36    .075       0 5154.74     .09       0 5701.05     .08       0
 5867.63     .09       0 6426.36    .045       0 7119.59    .085       0
8392.557     .08       08503.147     .05       08546.055     .08       0
 9908.03    .045       0
#XS Ineff= 2 , 0
       0 7119.59   58.55               0
Permanent Ineff=
       F       F
Bank Sta=8503.147,8546.055
XS Rating Curve= 0 ,0
Exp/Cntr=0.3,0.1

Type RM Length L Ch R = 1 ,1835    ,87.55,83.07,48.2
XS GIS Cut Line= 6
2364720.80344161670645.5830113592361398.30621104670067.664228395
2357206.43053931670659.1558875892356044.07935016670461.717871383
2354812.69276191670861.7246691442353763.76746854671677.688049123
#Sta/Elev= 30
       0   70.45  108.51   61.76  767.16   60.04  942.35   59.81 2292.32   58.75
 2363.31   58.54 2602.62   55.95  3329.7   57.16 3817.48   56.08 4288.08   58.27
 4711.72   52.08 4755.25   60.48 4851.43   60.11 4873.13   53.72 4968.22   53.01
  4990.5   56.98 5192.61   51.71  5318.6   54.75  5394.9   49.06 5821.26   53.84
 6487.77   58.16 6882.69    51.4 7664.08   54.88 8102.81   49.78 8529.29   47.73
 8530.89   44.89 8551.96   47.79 10543.3   53.7411152.45   55.8411448.34      57
#Mann= 20 ,-1 , 0
       0    .045       0  767.16     .08       0  942.35    .045       0
 2292.32     .07       0 2363.31    .045       0 2602.62     .07       0
  3329.7    .085       0 3817.48    .045       0 4288.08    .032       0
 4755.25    .075       0 4851.43    .032       0 4968.22    .075       0
  5318.6    .032       0 5821.26     .09       0 6882.69    .085       0
 8102.81     .08       0 8529.29     .05       0 8551.96     .08       0
 10543.3    .085       011152.45    .045       0
#XS Ineff= 2 , 0
       0 6487.77   58.1610500.66       0   55.41
Permanent Ineff=
       F       F
Bank Sta=8529.29,8551.96
XS Rating Curve= 0 ,0
Exp/Cntr=0.3,0.1
Stream Node=Toisnot Swamp   ,Downstream      , 0 , 0 ,Upstream end
Stream Node=Toisnot Swamp   ,Downstream      , 0 , 1 ,Downstream end

Chan Stop Cuts=-1
Use User Specified Reach Order=0