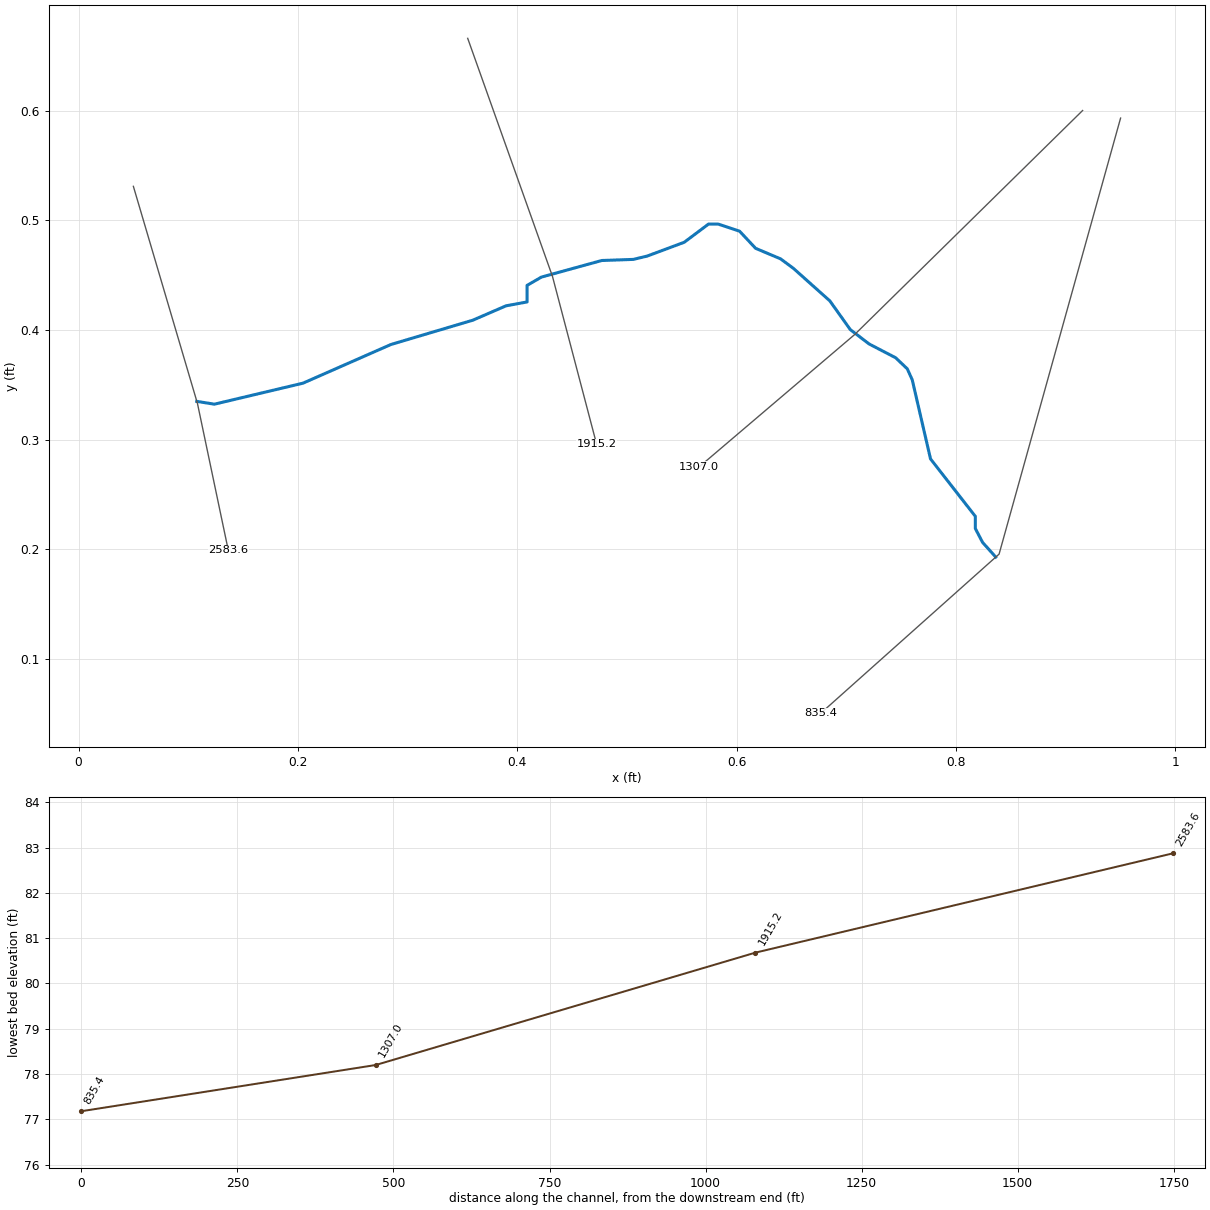
--- Apple_Tree_Swamp_Trib_FINAL.prj (project) ---

Proj Title=Apple Tree Swamp Tributary
Current Plan=p02
Default Exp/Contr=0.3,0.1
English Units
Geom File=g01
Flow File=f02
Flow File=f01
Plan File=p02
Plan File=p01
Y Axis Title=Elevation
X Axis Title(PF)=Main Channel Distance
X Axis Title(XS)=Station
BEGIN DESCRIPTION:
####(Watershed Name)####
APPLE TREE SWAMP TRIBUTARY
HCFCD Unit X###-##-##
(Flood Hazard, Floodway) Model
10, 2, 1, 0.2% Event
Filename:  N:\NC_flood\60138\Approximates\Eng\Toisnot_Nahunta\ENG\AppleTree_Swamp_Trib\Apple Tree Swamp Tributary.prj
Prepared by:  ________     Date: ________
Reviewed by:  ________     Date: ________
STATUS (Draft RAS, SVSQ, FINAL)
END DESCRIPTION:
DSS Export Rating Curves= 0
DSS Export Rating Curve Sorted= 0
DSS Export Volume Flow Curves= 0
DXF OffsetX= 0
DXF OffsetY= 0
DXF ScaleX= 1
DXF ScaleY= 10

--- Apple_Tree_Swamp_Trib_FINAL.p02 (plan) ---

Plan Title=Multi_Profile
Program Version=3.13
Short Identifier=Multi_Pro
Geom File=g01
Flow File=f02
Subcritical Flow
K Sum by GR= 0
Std Step Tol= 0.01
Critical Tol= 0.01
Num of Std Step Trials= 20
Max Error Tol= 0.3
Flow Tol Ratio= 0.001
Split Flow NTrial= 30
Split Flow Tol= 0.02
Split Flow Ratio= 0.02
Log Output Level= 0
Friction Slope Method= 1
Unsteady Friction Slope Method= 2
Unsteady Bridges Friction Slope Method= 1
Parabolic Critical Depth
Global Vel Dist= 0 , 0 , 0
Global Log Level= 0
CheckData=True
Encroach Param=-1 ,10,10, 2
Computation Interval=1HOUR
Output Interval=1HOUR
Run HTab= 0
Run UNet= 0
Run PostProcess= 0
UNET Theta= 1
UNET Theta Warmup= 1
UNET ZTol= 0.02
UNET ZSATol= 0.1
UNET MxIter= 20
UNET MaxInSteps= 20
UNET DtIC= 0
UNET DtMin= 0
UNET MaxCRTS= 20
UNET WFStab= 2
UNET SFStab= 1
UNET WFX= 1
UNET SFX= 1
UNET DSS MLevel= 4
UNET DZMax Abort= 100
UNET Convert EG Bridges=-1
UNET Use Existing IB Tables=-1
UNET Froude Reduction=False
UNET Froude Limit= 1
UNET Froude Power= 10
Instantaneous Interval=1HOUR
Write IC File= 0
Echo Input=False
Echo Output=False
Write Detailed= 0
Detailed Automatic Start=False, 10

--- Apple_Tree_Swamp_Trib_FINAL.p01 (plan) ---

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Plan Title=100 Year Single
Version=Version 3.0.1  Mar 2001
Short Identifier=Plan01
Geom File=g01
Flow File=f01
Encroach River=Apple Tree Swamp
Encroach Reach=Reach - 1
Encroach Node=2583.6
       4      .7
Encroach Node=1915.2
       4      .7
Encroach Node=1307.0
       4      .7
Encroach Node=835.4
       4      .7
Write Velocity= 0

--- Apple_Tree_Swamp_Trib_FINAL.f02 (steady flow) ---

Flow Title=Multi_Profile
Program Version=3.13
Number of Profiles= 7
Profile Names=10-yr,25-yr,50-yr,500-yr,100-yr-10%,100-yr-20%,100-yr-35%
River Rch & RM=Apple Tree Swamp,Reach - 1       ,2583.6
     241     357     463     960    1031    1321    1615
Boundary for River Rch & Prof#=Apple Tree Swamp,Reach - 1       , 1
Up Type= 0
Dn Type= 3
Dn Slope=0.0021
DSS Import GetInterval= 0
DSS Import GetPeak= 0
DSS Import FillOption= 0

--- Apple_Tree_Swamp_Trib_FINAL.f01 (steady flow) ---

Flow Title= 100 Year Single
Version=Version 3.0.1  Mar 2001
Number of Profiles= 2
Profile Names=100-Year,AFW
River Rch & RM=Apple Tree Swamp,Reach - 1       ,2583.6
     587     587
Boundary for River Rch & Prof#=Apple Tree Swamp,Reach - 1       , 1
Up Type= 0
Dn Type= 3
Dn Slope=.0021
DSS Import GetInterval= 0
DSS Import GetPeak= 0
DSS Import FillOption= 0

--- Apple_Tree_Swamp_Trib_FINAL.g01 (geometry) ---

Geom Title=Geom 01 by CodeH2 for Windows

River Reach=Apple Tree Swamp,Reach - 1
Reach XY= 30
   .107757314060   .334835829561   .123871389762   .332270128561
   .204593275077   .351444928561   .284816347412   .386758742043
   .359482750433   .408958601400   .389754798321   .422077919106
   .408929598321   .425607155022   .408929598321   .440743178966
   .422043552447   .448311190938   .477036342489   .463447214882
   .505795860699   .464455568001   .518411001846   .467485990938
   .552212285650   .480095768505   .574412145007   .496744322127
   .582988510097   .496744322127   .602667486657   .490190026854
   .617299334042   .474549826351   .639998006377   .464959744561
   .651604794405   .456383379470   .684901901650   .426615508141
   .703572525091   .400382236309   .720725255272   .387262918603
   .744941820867   .374653141036   .755534892195   .364558882687
   .760077844811   .354469987917   .776726398433   .282324467694
   .817591517650   .229852560449   .817591517650   .218755312561
   .824151176503   .206140171414   .836191865733   .192695427806

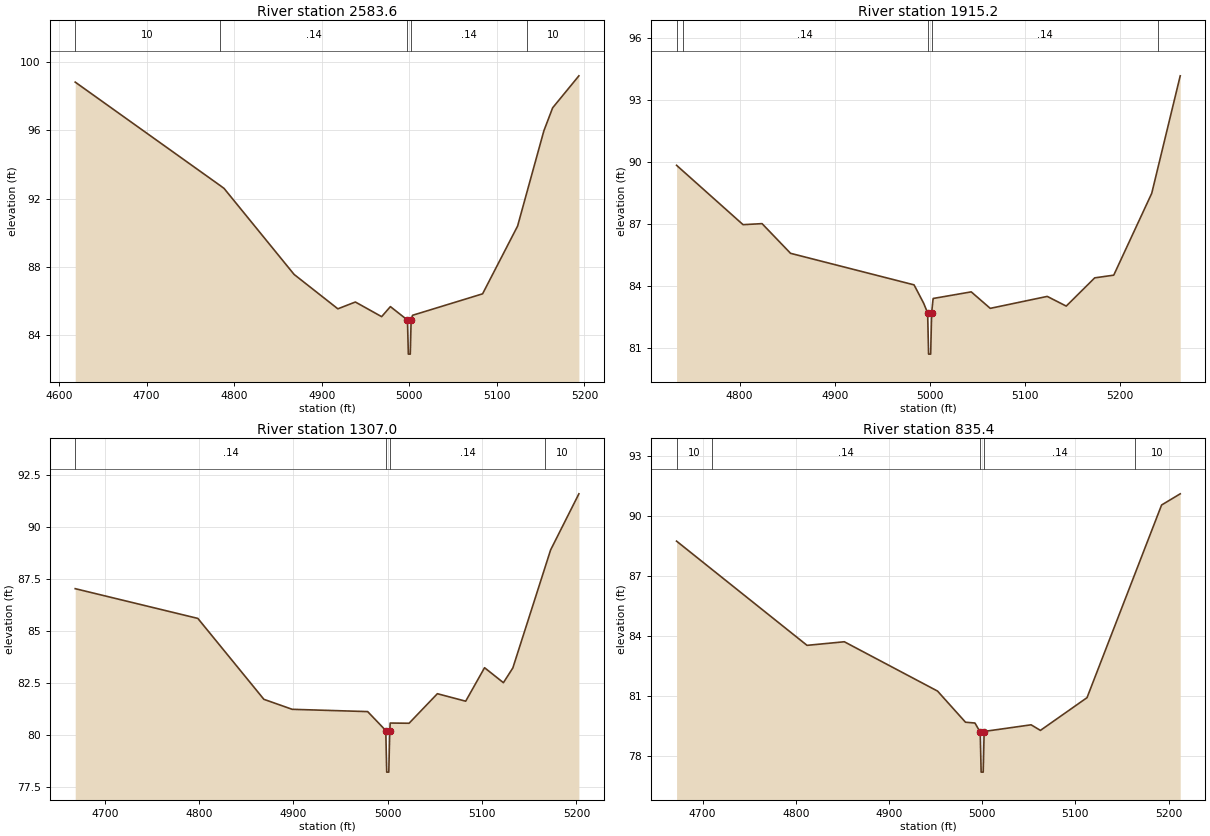
Type RM Length L Ch R = 1 ,2583.6,668.4,668.4,668.4
XS GIS Cut Line= 3
   .050000000000   .531153846158   .108420273570   .332942090579
   .136538461540   .198846153850
BEGIN DESCRIPTION:
UNT 1 to Apple Tree Swamp 4.0
END DESCRIPTION:
#Sta/Elev= 19
  4618.4   98.84  4783.9   92.77  4788.4    92.6  4868.4   87.55  4918.4   85.53
  4938.4   85.93  4968.4   85.07  4978.4   85.66  4997.9   84.87  4998.9   82.87
  5001.1   82.87  5002.1   84.87  5003.7   85.15  5083.7   86.41  5123.7   90.39
  5134.9   92.48  5153.7   95.98  5163.7   97.33  5193.7   99.21
#Mann= 5 , 1 , 0
 4618.40      10       0  4783.9    0.14       0  4997.9   0.044       0
  5002.1    0.14       0  5134.9      10       0
Bank Sta=4997.90,5002.10
Exp/Cntr=0.3,0.1

Type RM Length L Ch R = 1 ,1915.2,608.2,608.2,608.2
XS GIS Cut Line= 3
   .354795881482   .666273795403   .432090189846   .448883553124
   .472307692309   .295769230768
BEGIN DESCRIPTION:
UNT 1 to Apple Tree Swamp 3.0
END DESCRIPTION:
#Sta/Elev= 22
  4733.6   89.84  4739.9   89.58  4803.6   86.96  4823.6   87.01  4853.6   85.57
  4983.6   84.04  4993.6   83.16  4997.9   82.68  4998.9   80.68  5001.1   80.68
  5002.1   82.68  5003.6   83.35  5003.8   83.38  5043.8    83.7  5063.8    82.9
  5123.8   83.48  5143.8   83.01  5173.8   84.38  5193.8   84.51  5233.8   88.48
  5239.9   89.64  5263.8   94.18
#Mann= 5 , 1 , 0
 4733.60      10       0  4739.9    0.14       0  4997.9   0.044       0
  5002.1    0.14       0  5239.9      10       0
Bank Sta=4997.90,5002.10
Exp/Cntr=0.3,0.1

Type RM Length L Ch R = 1 ,1307.0,471.6,471.6,471.6
XS GIS Cut Line= 3
   .915384615386   .600384615385   .707451163397   .395743716126
   .565769230772   .275000000000
BEGIN DESCRIPTION:
UNT 1 to Apple Tree Swamp 2.0
END DESCRIPTION:
#Sta/Elev= 19
  4668.7   87.02  4798.7   85.59  4868.7    81.7  4898.7   81.22  4978.7   81.11
  4997.9    80.2  4998.9    78.2  5001.1    78.2  5002.1    80.2  5002.6   80.56
  5022.6   80.55  5052.6   81.97  5082.6   81.61  5102.6   83.22  5122.6    82.5
  5132.6   83.21  5166.9   88.07  5172.6   88.88  5202.6   91.58
#Mann= 4 , 1 , 0
 4668.70    0.14       0  4997.9   0.044       0  5002.1    0.14       0
  5166.9      10       0
Bank Sta=4997.90,5002.10
Exp/Cntr=0.3,0.1

Type RM Length L Ch R = 1 ,835.4,0,0,0
XS GIS Cut Line= 3
   .950000000000   .593461538462   .839230769231   .195384615388
   .676538461541   .050000000000
BEGIN DESCRIPTION:
UNT 1 to Apple Tree Swamp 1.0
END DESCRIPTION:
#Sta/Elev= 19
  4672.1   88.75  4709.9   87.34  4812.1   83.53  4852.1   83.71  4952.1   81.24
  4982.1   79.68  4992.1   79.64  4992.5   79.62  4997.9   79.18  4998.9   77.18
  5001.1   77.18  5002.1   79.18  5002.5   79.22  5052.5   79.55  5062.5   79.27
  5112.5   80.91  5163.9   87.11  5192.5   90.56  5212.5   91.12
#Mann= 5 , 1 , 0
 4672.10      10       0  4709.9    0.14       0  4997.9   0.044       0
  5002.1    0.14       0  5163.9      10       0
Bank Sta=4997.90,5002.10
Exp/Cntr=0.3,0.1

Chan Stop Cuts=-1