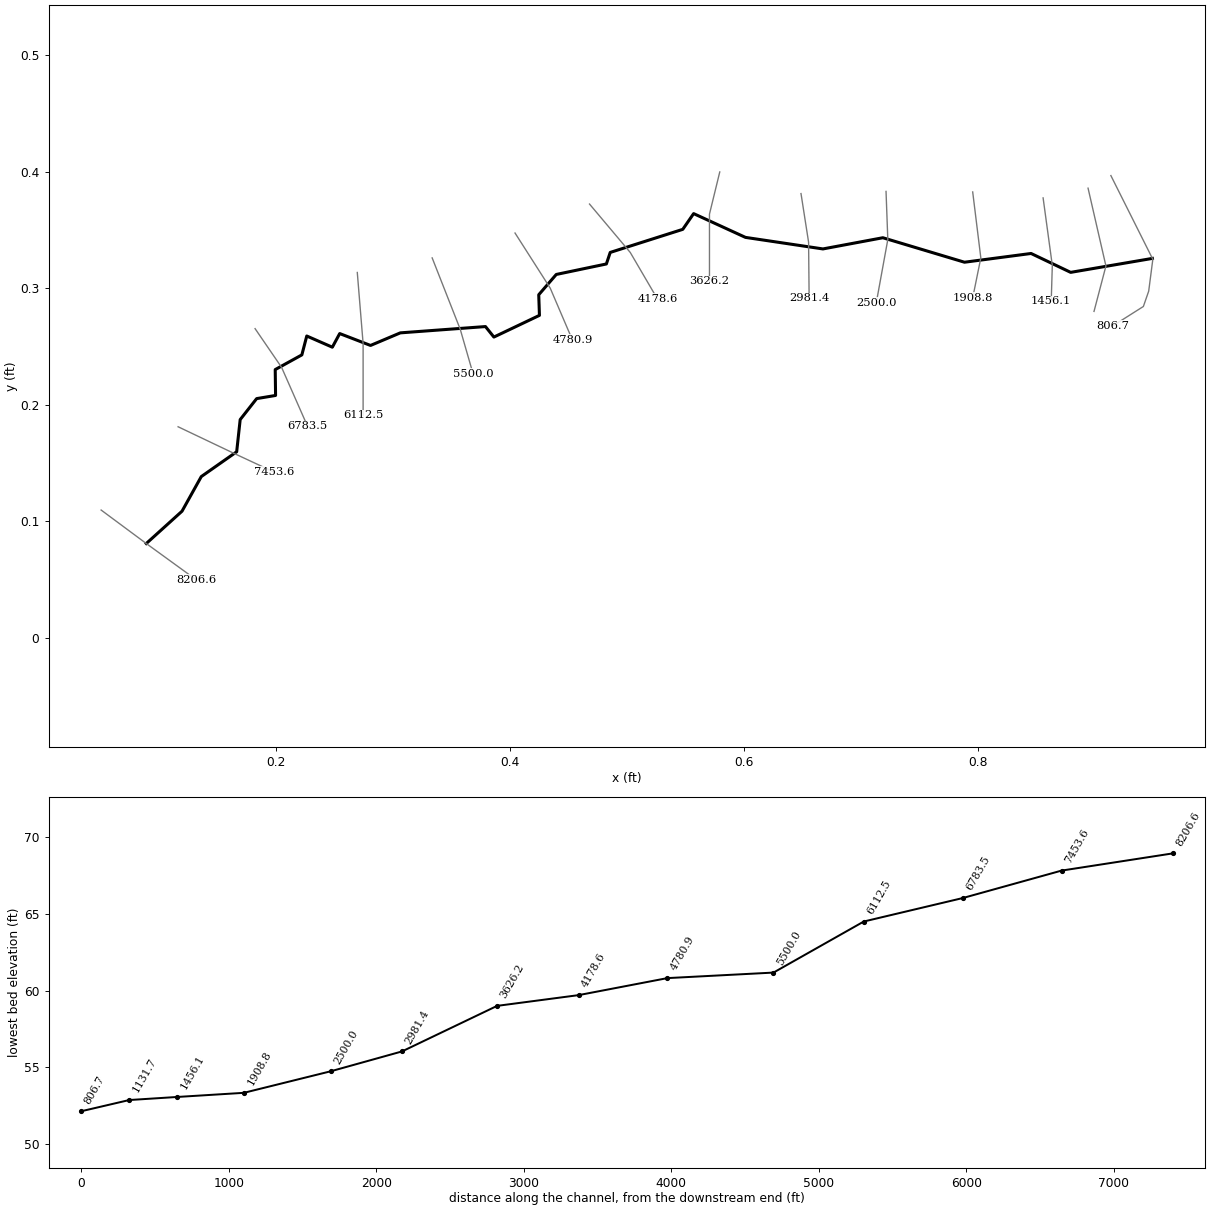
--- Reedy_Branch_FINAL.prj (project) ---

Proj Title=Reedy Branch
Current Plan=p02
Default Exp/Contr=0.3,0.1
English Units
Geom File=g01
Flow File=f02
Flow File=f01
Plan File=p02
Plan File=p01
Y Axis Title=Elevation
X Axis Title(PF)=Main Channel Distance
X Axis Title(XS)=Station
BEGIN DESCRIPTION:
was named Jacks Fork previously
####(Watershed Name)####
REEDY BRANCH
HCFCD Unit X###-##-##
(Flood Hazard, Floodway) Model
10, 2, 1, 0.2% Event
Filename:  N:\NC_flood\60138\Approximates\Eng\Toisnot_Nahunta\ENG\Reedy_Branch\Reedy Branch.prj
Prepared by:  ________     Date: ________
Reviewed by:  ________     Date: ________
STATUS (Draft RAS, SVSQ, FINAL)
END DESCRIPTION:
DSS Export Rating Curves= 0
DSS Export Rating Curve Sorted= 0
DSS Export Volume Flow Curves= 0
DXF OffsetX= 0
DXF OffsetY= 0
DXF ScaleX= 1
DXF ScaleY= 10

--- Reedy_Branch_FINAL.p02 (plan) ---

Plan Title=Multi_Profile
Program Version=3.13
Short Identifier=Multi_Pro
Geom File=g01
Flow File=f02
Subcritical Flow
K Sum by GR= 0
Std Step Tol= 0.01
Critical Tol= 0.01
Num of Std Step Trials= 20
Max Error Tol= 0.3
Flow Tol Ratio= 0.001
Split Flow NTrial= 30
Split Flow Tol= 0.02
Split Flow Ratio= 0.02
Log Output Level= 0
Friction Slope Method= 1
Unsteady Friction Slope Method= 2
Unsteady Bridges Friction Slope Method= 1
Parabolic Critical Depth
Global Vel Dist= 0 , 0 , 0
Global Log Level= 0
CheckData=True
Encroach Param=-1 ,10,10, 2
Computation Interval=1HOUR
Output Interval=1HOUR
Run HTab= 0
Run UNet= 0
Run PostProcess= 0
UNET Theta= 1
UNET Theta Warmup= 1
UNET ZTol= 0.02
UNET ZSATol= 0.1
UNET MxIter= 20
UNET MaxInSteps= 20
UNET DtIC= 0
UNET DtMin= 0
UNET MaxCRTS= 20
UNET WFStab= 2
UNET SFStab= 1
UNET WFX= 1
UNET SFX= 1
UNET DSS MLevel= 4
UNET DZMax Abort= 100
UNET Convert EG Bridges=-1
UNET Use Existing IB Tables=-1
UNET Froude Reduction=False
UNET Froude Limit= 1
UNET Froude Power= 10
Instantaneous Interval=1HOUR
Write IC File= 0
Echo Input=False
Echo Output=False
Write Detailed= 0
Detailed Automatic Start=False, 10

--- Reedy_Branch_FINAL.p01 (plan) ---

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Plan Title=100 Year Single
Version=Version 3.0.1  Mar 2001
Short Identifier=Plan01
Geom File=g01
Flow File=f01
Encroach River=Reedy Branch
Encroach Reach=Reach - 1
Encroach Node=8206.6
       4      .7
Encroach Node=7453.6
       1    4915    5060
Encroach Node=6783.5
       1    4935    5130
Encroach Node=6112.5
       4      .7
Encroach Node=5500.0
       1    4840    5045
Encroach Node=4780.9
       4      .7
Encroach Node=4178.6
       4      .7
Encroach Node=3626.2
       4      .7
Encroach Node=2981.4
       4      .7
Encroach Node=2500.0
       4      .7
Encroach Node=1908.8
       4      .7
Encroach Node=1456.1
       4      .7
Encroach Node=1131.7
       4      .7
Encroach Node=806.7
       4      .7
Write Velocity= 0

--- Reedy_Branch_FINAL.f02 (steady flow) ---

Flow Title=Multi_Profile
Program Version=3.13
Number of Profiles= 7
Profile Names=10-yr,25-yr,50-yr,500-yr,100-yr-10%,100-yr-20%,100-yr-35%
River Rch & RM=Reedy Branch,Reach - 1       ,8206.6
     341     499     643    1302    1405    1801    2200
River Rch & RM=Reedy Branch,Reach - 1       ,5500.0
     416     604     774    1549    1676    2148    2624
Boundary for River Rch & Prof#=Reedy Branch,Reach - 1       , 1
Up Type= 0
Dn Type= 3
Dn Slope=0.0015
DSS Import GetInterval= 0
DSS Import GetPeak= 0
DSS Import FillOption= 0

--- Reedy_Branch_FINAL.f01 (steady flow) ---

Flow Title= 100 Year Single
Version=Version 3.0.1  Mar 2001
Number of Profiles= 2
Profile Names=100-Year,AFW
River Rch & RM=Reedy Branch,Reach - 1       ,8206.6
     809     809
River Rch & RM=Reedy Branch,Reach - 1       ,5500.0
     971     971
Boundary for River Rch & Prof#=Reedy Branch,Reach - 1       , 1
Up Type= 0
Dn Type= 3
Dn Slope=.0015
DSS Import GetInterval= 0
DSS Import GetPeak= 0
DSS Import FillOption= 0

--- Reedy_Branch_FINAL.g01 (geometry) ---

Geom Title=Geom 01 by CodeH2 for Windows
Version=Version 3.0.1  Mar 2001

River Reach=Reedy Branch    ,Reach - 1
Reach XY= 30
        .0886454        .0810872        .1192167        .1087832
        .1357107        .1384713        .1659964        .1597608
        .1689962        .1873501        .1830896        .2053425
        .1992834        .2080405        .1989831        .2302308
         .221774        .2428258        .2259718        .2590196
        .2478618        .2494228        .2541601        .2611185
        .2805482        .2509227         .306037        .2617176
        .3789062        .2671165        .3861038        .2581203
         .425087        .2767118        .4244864         .294404
        .4394806        .3117974        .4823628        .3207936
        .4856614        .3306892        .5477341        .3504803
        .5570306        .3639746        .6014112         .343583
        .6676834        .3336874        .7189613        .3432827
        .7888322         .322292        .8458078        .3297899
        .8796938         .313596         .949607        .3255656

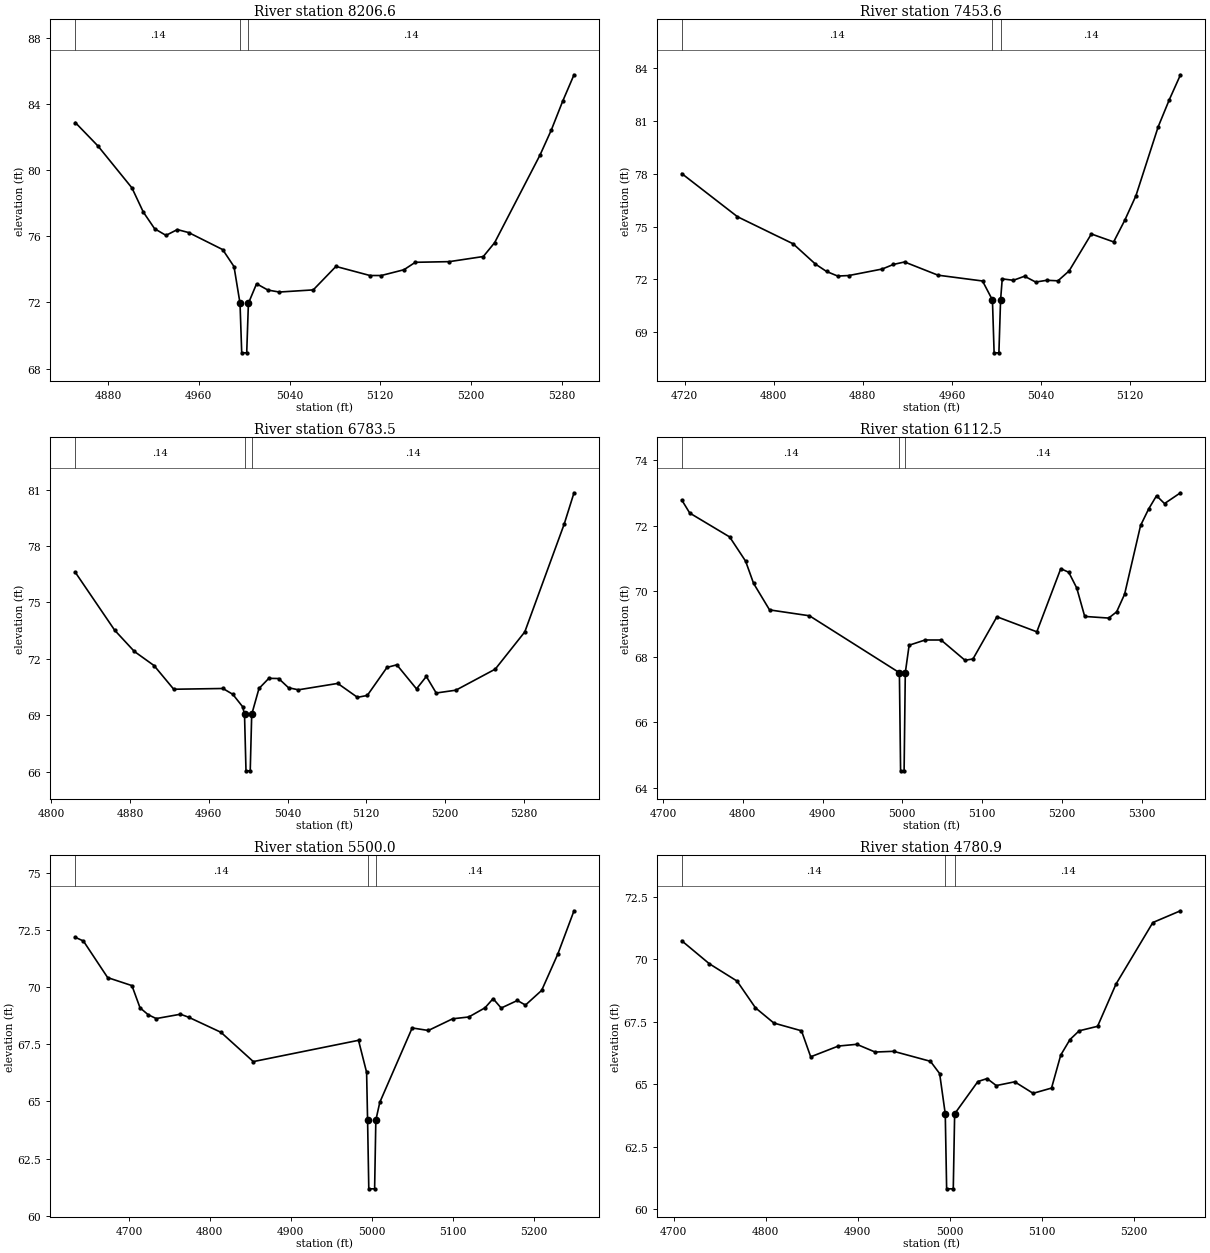
Type RM Length L Ch R = 1 ,8206.6  ,753,753,753
BEGIN DESCRIPTION:
Reedy Branch 13.0
END DESCRIPTION:
XS GIS Cut Line= 3
             .05        .1097847        .0887494        .0809995
        .1313736             .05
#Sta/Elev= 30
    4851   82.89    4871   81.47    4901   78.93    4911   77.47    4921   76.46
    4931   76.06    4941   76.41    4951   76.23    4981    75.2    4991   74.17
  4996.3   71.95  4997.8   68.95  5002.2   68.95  5003.7   71.95  5010.9   73.13
  5020.9   72.75  5030.9   72.63  5060.9   72.76  5080.9   74.18  5110.9   73.63
  5120.9   73.63  5140.9   73.98  5150.9   74.43  5180.9   74.47  5210.9   74.78
  5220.9   75.62  5260.9   80.92  5270.9   82.44  5280.9   84.18  5290.9   85.78
#Mann= 3 ,-1 , 0
    4851     .14       0  4996.3    .047       0  5003.7     .14       0
Bank Sta=4996.3,5003.7
XS Rating Curve= 0
Exp/Cntr=.3,.1

Type RM Length L Ch R = 1 ,7453.6  ,670.1,670.1,670.1
BEGIN DESCRIPTION:
Reedy Branch 12.0
END DESCRIPTION:
XS GIS Cut Line= 3
        .1158739        .1811942        .1645874        .1579446
        .1978011        .1424449
#Sta/Elev= 30
  4717.5   78.01  4767.5   75.56  4817.5   74.02  4837.5   72.87  4847.5   72.45
  4857.5   72.19  4867.5   72.22  4897.5   72.59  4907.5   72.85  4917.5   72.99
  4947.5   72.24  4987.5   71.91  4996.4   70.83  4997.9   67.83  5002.2   67.83
  5003.7   70.83  5005.2   72.03  5015.2   71.95  5025.2   72.18  5035.2   71.85
  5045.2   71.95  5055.2   71.92  5065.2   72.48  5085.2   74.58  5105.2   74.13
  5115.2   75.36  5125.2   76.75  5145.2   80.67  5155.2   82.21  5165.2   83.62
#Mann= 3 ,-1 , 0
  4717.5     .14       0  4996.4    .047       0  5003.7     .14       0
Bank Sta=4996.4,5003.7
XS Rating Curve= 0
Exp/Cntr=.3,.1

Type RM Length L Ch R = 1 ,6783.5  ,671,671,671
BEGIN DESCRIPTION:
Reedy Branch 11.0
END DESCRIPTION:
XS GIS Cut Line= 3
        .1817478        .2653357        .2044438        .2321219
        .2265863        .1817478
#Sta/Elev= 30
  4824.4    76.6  4864.4   73.52  4884.4   72.39  4904.4   71.64  4924.4   70.38
  4974.4   70.42  4984.4   70.11  4994.4   69.45  4996.3   69.04  4997.8   66.04
  5002.1   66.04  5003.6   69.04    5011   70.42    5021   70.96    5031   70.95
    5041   70.46    5051   70.35    5091   70.69    5111   69.95    5121   70.05
    5141   71.54    5151   71.68    5171    70.4    5181   71.06    5191   70.18
    5211   70.33    5251   71.45    5281   73.43    5321   79.16    5331   80.83
#Mann= 3 ,-1 , 0
  4824.4     .14       0  4996.3    .047       0  5003.6     .14       0
Bank Sta=4996.3,5003.6
XS Rating Curve= 0
Exp/Cntr=.3,.1

Type RM Length L Ch R = 1 ,6112.5  ,612.5,612.5,612.5
BEGIN DESCRIPTION:
Reedy Branch 10.0
END DESCRIPTION:
XS GIS Cut Line= 3
        .2692106        .3134956        .2741927        .2526037
        .2741927        .1911583
#Sta/Elev= 30
  4723.6   72.79  4733.6   72.39  4783.6   71.66  4803.6   70.92  4813.6   70.24
  4833.6   69.43  4883.6   69.25  4996.3   67.51  4997.8   64.51  5002.2   64.51
  5003.7   67.51  5008.5   68.35  5028.5   68.51  5048.5   68.51  5078.5   67.89
  5088.5   67.93  5118.5   69.22  5168.5   68.76  5198.5   70.69  5208.5   70.58
  5218.5    70.1  5228.5   69.23  5258.5   69.18  5268.5   69.37  5278.5   69.91
  5298.5   72.01  5308.5   72.51  5318.5   72.92  5328.5   72.68  5348.5   73.01
#Mann= 3 ,-1 , 0
  4723.6     .14       0  4996.3    .047       0  5003.7     .14       0
Bank Sta=4996.3,5003.7
XS Rating Curve= 0
Exp/Cntr=.3,.1

Type RM Length L Ch R = 1 ,5500.0  ,719.1,719.1,719.1
BEGIN DESCRIPTION:
Reedy Branch 9.0
END DESCRIPTION:
XS GIS Cut Line= 3
        .3332896        .3260045        .3573351        .2647168
        .3682982        .2265863
#Sta/Elev= 30
  4633.7   72.17  4643.7   72.01  4673.7   70.41  4703.7   70.06  4713.7   69.09
  4723.7   68.79  4733.7   68.62  4763.7   68.81  4773.7   68.68  4813.7   68.02
  4853.7   66.74  4983.7   67.67  4993.7   66.27  4994.9   64.18  4996.4   61.18
  5003.6   61.18  5005.1   64.18    5010   64.96    5050   68.21    5070    68.1
    5100   68.61    5120   68.69    5140   69.09    5150   69.49    5160   69.08
    5180   69.41    5190   69.21    5210   69.85    5230   71.44    5250   73.33
#Mann= 3 ,-1 , 0
  4633.7     .14       0  4994.9    .047       0  5005.1     .14       0
Bank Sta=4994.9,5005.1
XS Rating Curve= 0
Exp/Cntr=.3,.1

Type RM Length L Ch R = 1 ,4780.9  ,602.3,602.3,602.3
BEGIN DESCRIPTION:
Reedy Branch 8.0
END DESCRIPTION:
XS GIS Cut Line= 3
        .4042029        .3473249        .4343295        .3000493
        .4533324        .2555547
#Sta/Elev= 30
  4708.8   70.74  4738.8   69.82  4768.8   69.13  4788.8   68.06  4808.8   67.45
  4838.8   67.14  4848.8    66.1  4878.8   66.53  4898.8    66.6  4918.8   66.29
  4938.8   66.32  4978.8   65.92  4988.8   65.43  4994.9   63.82  4996.4   60.82
  5003.6   60.82  5005.1   63.82  5030.3   65.11  5040.3   65.23  5050.3   64.95
  5070.3    65.1  5090.3   64.64  5110.3   64.85  5120.3   66.17  5130.3   66.79
  5140.3   67.14  5160.3   67.32  5180.3   69.01  5220.3   71.47  5250.3   71.94
#Mann= 3 ,-1 , 0
  4708.8     .14       0  4994.9    .047       0  5005.1     .14       0
Bank Sta=4994.9,5005.1
XS Rating Curve= 0
Exp/Cntr=.3,.1

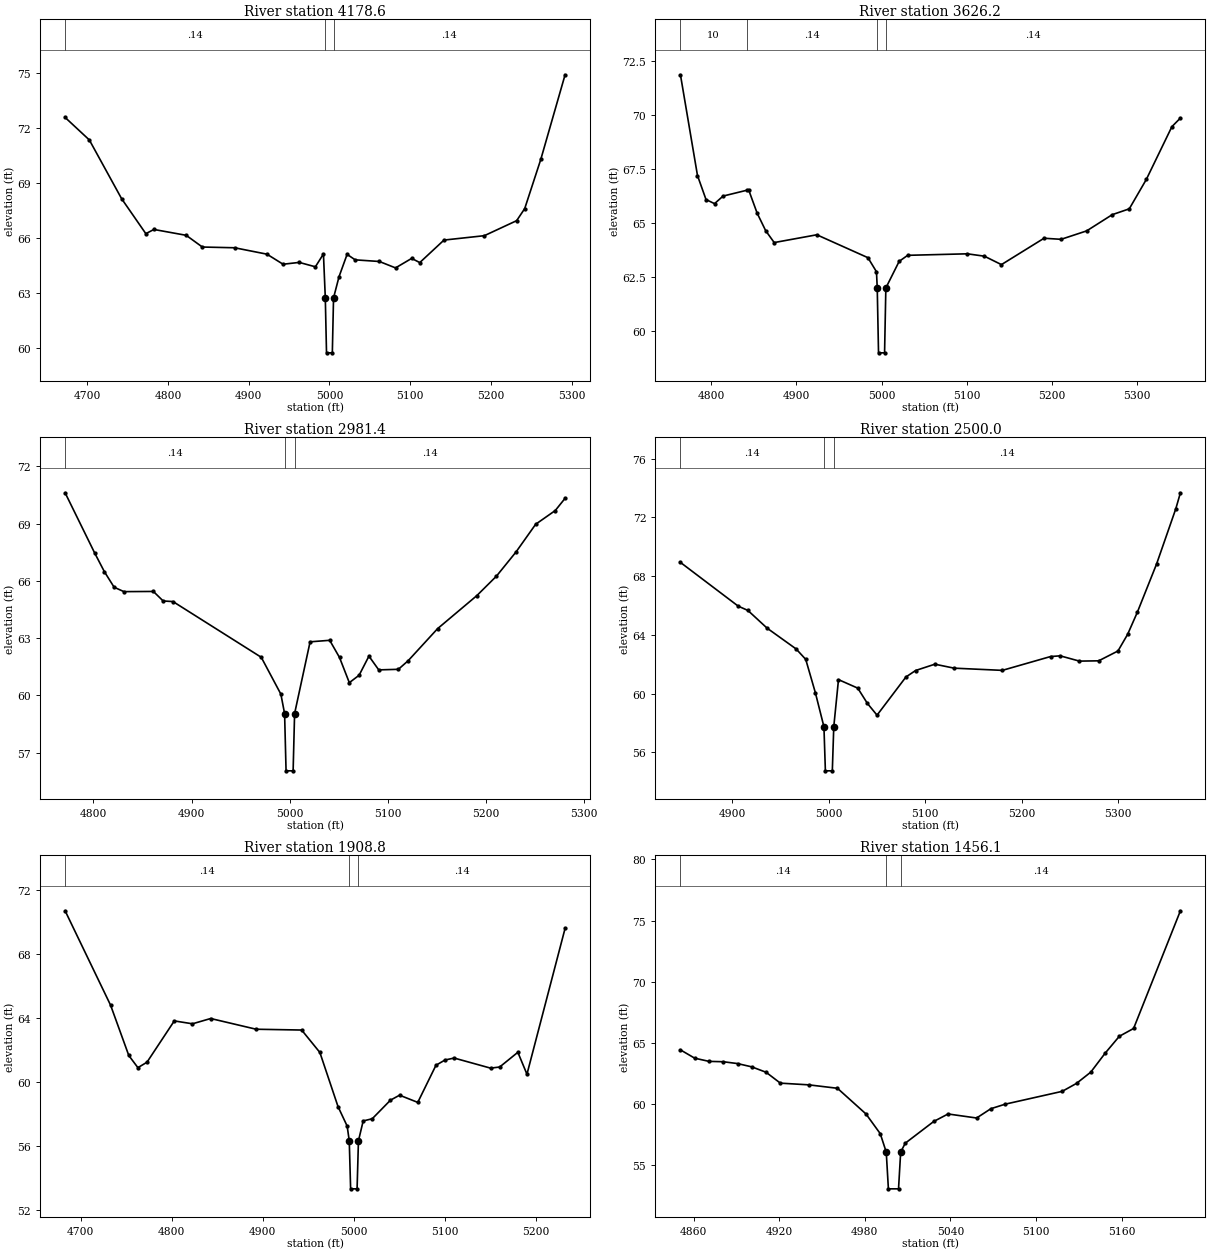
Type RM Length L Ch R = 1 ,4178.6  ,552.4,552.4,552.4
BEGIN DESCRIPTION:
Reedy Branch 7.0
END DESCRIPTION:
XS GIS Cut Line= 3
        .4679394        .3721732        .5028138         .330656
        .5260634        .2907995
#Sta/Elev= 30
  4672.6   72.57  4702.6   71.34  4742.6   68.13  4772.6   66.22  4782.6   66.45
  4822.6   66.13  4842.6   65.49  4882.6   65.45  4922.6    65.1  4942.6   64.55
  4962.6   64.65  4982.6   64.41  4992.6   65.11  4994.9   62.71  4996.4   59.71
  5003.6   59.71  5005.1   62.71  5011.9   63.87  5021.9   65.09  5031.9   64.79
  5061.9    64.7  5081.9   64.35  5101.9   64.87  5111.9   64.64  5141.9   65.87
  5191.9   66.11  5231.9   66.93  5241.9   67.59  5261.9   70.29  5291.9    74.9
#Mann= 3 ,-1 , 0
  4672.6     .14       0  4994.9    .047       0  5005.1     .14       0
Bank Sta=4994.9,5005.1
XS Rating Curve= 0
Exp/Cntr=.3,.1

Type RM Length L Ch R = 1 ,3626.2  ,644.8,644.8,644.8
BEGIN DESCRIPTION:
Reedy Branch 6.0
END DESCRIPTION:
XS GIS Cut Line= 3
        .5794005        .3996987        .5705943        .3635469
        .5705943        .3060746
#Sta/Elev= 30
    4764   71.87    4784   67.21    4794    66.1    4804   65.91    4814   66.26
  4841.9   66.53    4844   66.55    4854   65.47    4864   64.66    4874   64.11
    4924   64.47    4984   63.41    4994   62.76  4994.9   62.01  4996.4   59.01
  5003.5   59.01    5005   62.01  5020.6   63.24  5030.6   63.52  5100.6   63.59
  5120.6   63.48  5140.6   63.09  5190.6   64.31  5210.6   64.26  5240.6   64.65
  5270.6    65.4  5290.6   65.67  5310.6   67.03  5340.6   69.47  5350.6   69.87
#Mann= 4 ,-1 , 0
    4764      10       0  4841.9     .14       0  4994.9    .047       0
    5005     .14       0
Bank Sta=4994.9,5005
XS Rating Curve= 0
Exp/Cntr=.3,.1

Type RM Length L Ch R = 1 ,2981.4  ,481.4,481.4,481.4
BEGIN DESCRIPTION:
Reedy Branch 5.0
END DESCRIPTION:
XS GIS Cut Line= 3
        .6489234        .3811593        .6554122        .3394456
        .6558757        .2912431
#Sta/Elev= 30
  4771.1   70.61  4801.1   67.47  4811.1   66.48  4821.1   65.66  4831.1   65.43
  4861.1   65.44  4871.1   64.94  4881.1   64.91  4971.1   61.99  4991.1   60.06
  4994.9   59.04  4996.4   56.04  5003.6   56.04  5005.1   59.04  5020.9    62.8
  5040.9   62.88  5050.9   61.98  5060.9   60.66  5070.9   61.05  5080.9   62.05
  5090.9   61.33  5110.9   61.36  5120.9   61.81  5150.9   63.49  5190.9   65.22
  5210.9   66.24  5230.9   67.51  5250.9   68.96  5270.9   69.68  5280.9   70.32
#Mann= 3 ,-1 , 0
  4771.1     .14       0  4994.9    .047       0  5005.1     .14       0
Bank Sta=4994.9,5005.1
XS Rating Curve= 0
Exp/Cntr=.3,.1

Type RM Length L Ch R = 1 ,2500.0  ,591.2,591.2,591.2
BEGIN DESCRIPTION:
Reedy Branch 4.0
END DESCRIPTION:
XS GIS Cut Line= 3
        .7216906        .3830133        .7232059        .3416919
        .7133479        .2875352
#Sta/Elev= 30
    4846   68.94    4906   65.96    4916   65.67    4936   64.46    4966   63.05
    4976   62.34    4986   60.07  4994.9   57.75  4996.4   54.75  5003.6   54.75
  5005.1   57.75    5010   60.96    5030   60.38    5040   59.34    5050   58.54
    5080   61.14    5090   61.58    5110   62.01    5130   61.74    5180   61.59
    5230   62.53    5240   62.58    5260   62.22    5280   62.24    5300   62.91
    5310   64.04    5320   65.53    5340   68.82    5360   72.59  5364.8   73.68
#Mann= 3 ,-1 , 0
    4846     .14       0  4994.9    .047       0  5005.1     .14       0
Bank Sta=4994.9,5005.1
XS Rating Curve= 0
Exp/Cntr=.3,.1

Type RM Length L Ch R = 1 ,1908.8  ,452.7,452.7,452.7
BEGIN DESCRIPTION:
Reedy Branch 3.0
END DESCRIPTION:
XS GIS Cut Line= 3
        .7958483        .3825498        .8028006        .3260045
        .7958483        .2917066
#Sta/Elev= 30
  4682.7   70.71  4732.7   64.81  4752.7   61.67  4762.7   60.91  4772.7   61.25
  4802.7   63.83  4822.7   63.65  4842.7   63.98  4892.7   63.31  4942.7   63.26
  4962.7   61.86  4982.7   58.47  4992.7   57.26    4995   56.34  4996.5   53.34
  5003.6   53.34  5005.1   56.34  5010.3   57.58  5020.3   57.72  5040.3   58.88
  5050.3   59.19  5070.3   58.74  5090.3   61.06  5100.3   61.39  5110.3   61.51
  5150.3   60.88  5160.3   60.95  5180.3   61.87  5190.3    60.5  5232.2   69.61
#Mann= 3 ,-1 , 0
  4682.7     .14       0    4995    .047       0  5005.1     .14       0
Bank Sta=4995,5005.1
XS Rating Curve= 0
Exp/Cntr=.3,.1

Type RM Length L Ch R = 1 ,1456.1  ,324.4,324.4,324.4
BEGIN DESCRIPTION:
Reedy Branch 2.0
END DESCRIPTION:
XS GIS Cut Line= 3
        .8561015        .3774514        .8639807        .3195157
        .8630537        .2889257
#Sta/Elev= 29
  4850.8   64.43  4860.8   63.75  4870.8   63.49  4880.8   63.46  4890.8   63.31
  4900.8   63.04  4910.8    62.6  4920.8   61.71  4940.8   61.57  4960.8   61.29
  4980.8   59.19  4990.8   57.58    4995   56.07  4996.5   53.07  5003.6   53.07
  5005.1   56.07  5008.3    56.8  5028.3   58.58  5038.3   59.19  5058.3   58.86
  5068.3   59.62  5078.3   59.99  5118.3   61.04  5128.3   61.69  5138.3   62.61
  5148.3   64.15  5158.3   65.54  5168.3   66.18  5201.1    75.8
#Mann= 3 ,-1 , 0
  4850.8     .14       0    4995    .047       0  5005.1     .14       0
Bank Sta=4995,5005.1
XS Rating Curve= 0
Exp/Cntr=.3,.1

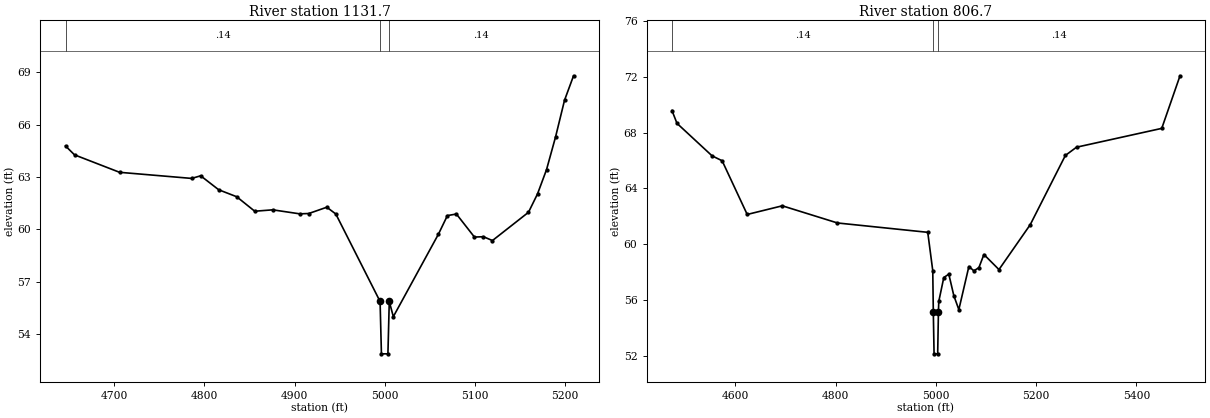
Type RM Length L Ch R = 1 ,1131.7  ,325,325,325
BEGIN DESCRIPTION:
Reedy Branch 1.0
END DESCRIPTION:
XS GIS Cut Line= 3
        .8945708        .3857942        .9098658        .3190522
        .8996691        .2801194
#Sta/Elev= 30
  4645.8   64.78  4655.8   64.27  4705.8   63.27  4785.8   62.92  4795.8   63.07
  4815.8   62.27  4835.8   61.87  4855.8   61.04  4875.8   61.12  4905.8   60.89
  4915.8   60.91  4935.8   61.27  4945.8   60.88  4994.9   55.87  4996.4   52.87
  5003.6   52.87  5005.1   55.87  5009.6      55  5059.6   59.72  5069.6   60.79
  5079.6   60.88  5099.6   59.56  5109.6   59.58  5119.6   59.36  5159.6   60.98
  5169.6   62.03  5179.6   63.42  5189.6   65.29  5199.6    67.4  5209.6    68.8
#Mann= 3 ,-1 , 0
  4645.8     .14       0  4994.9    .047       0  5005.1     .14       0
Bank Sta=4994.9,5005.1
XS Rating Curve= 0
Exp/Cntr=.3,.1

Type RM Length L Ch R = 1 ,806.7   ,0,0,0
BEGIN DESCRIPTION:
Reedy Branch 0.5
END DESCRIPTION:
XS GIS Cut Line= 5
        .9141011        .3965883             .95        .3247905
        .9464607        .2974871        .9419101         .284341
        .9156179        .2676556
#Sta/Elev= 28
  4473.8   69.58  4483.8   68.66  4553.8   66.33  4573.8   65.98  4623.8   62.13
  4693.8   62.75  4803.8   61.52  4983.8   60.85  4993.8    58.1  4994.9   55.14
  4996.4   52.14  5003.6   52.14  5005.1   55.14  5005.8    55.9  5015.8   57.61
  5025.8   57.85  5035.8   56.31  5045.8   55.31  5065.8    58.4  5075.8   58.09
  5085.8   58.32  5095.8   59.26  5125.8   58.18  5188.2    61.4  5258.2   66.36
  5280.4   66.95  5450.4    68.3  5486.8   72.07
#Mann= 3 , 1 , 0
  4473.8     .14       0  4994.9    .047       0  5005.1     .14       0
Bank Sta=4994.9,5005.1
XS Rating Curve= 0
Exp/Cntr=.3,.1

Chan Stop Cuts=-1