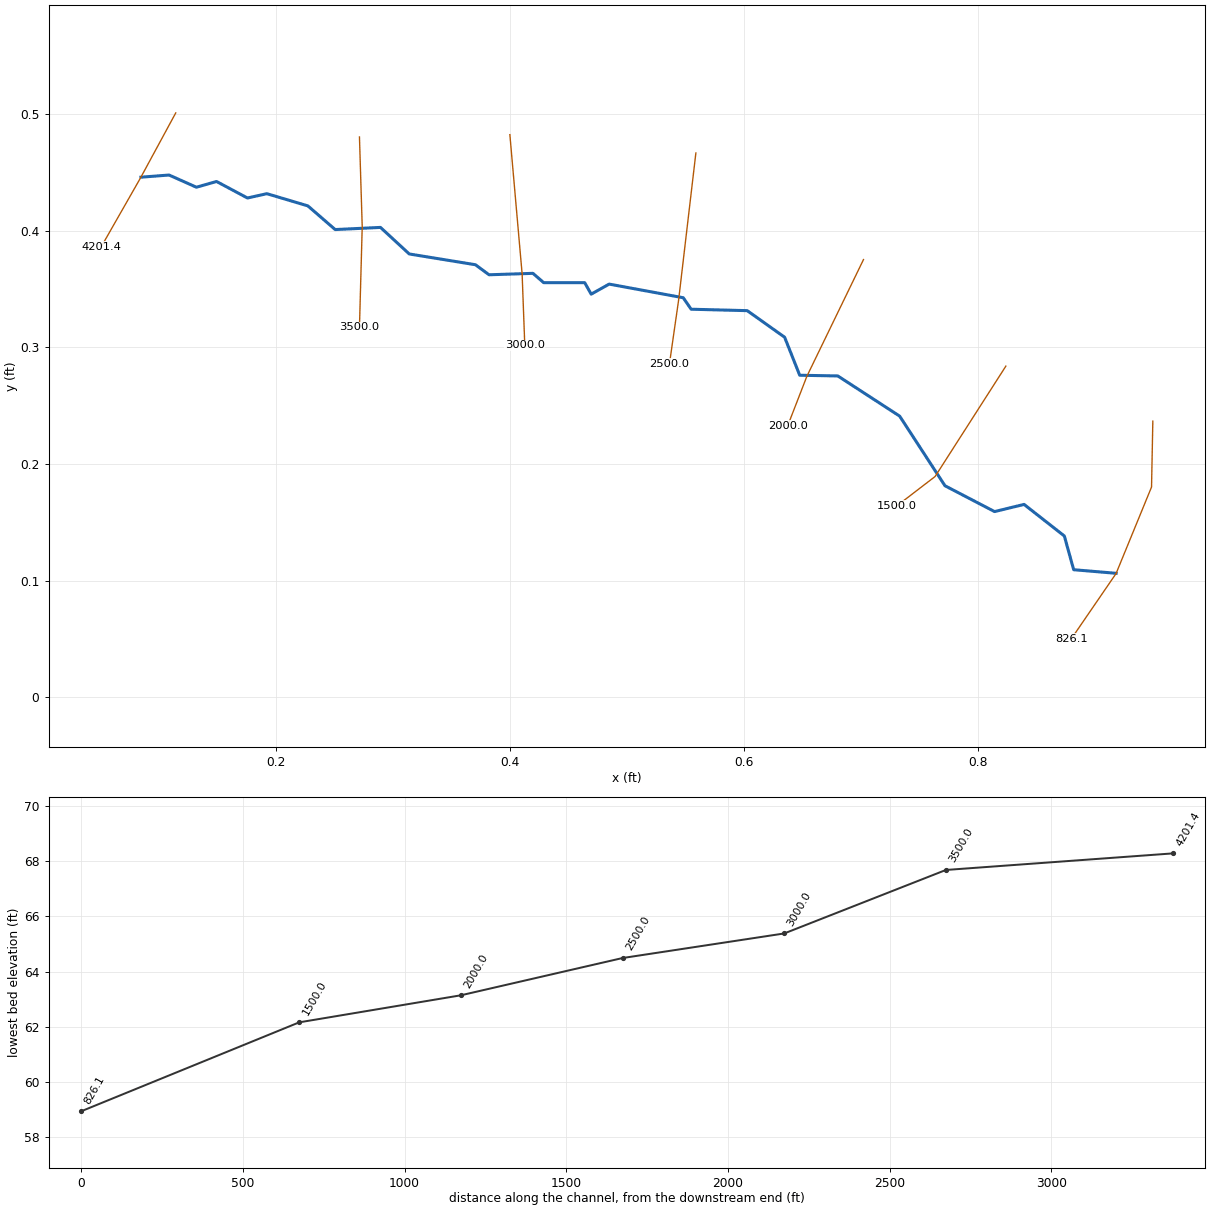
--- Lewis_Branch_FINAL.prj (project) ---

Proj Title=Lewis Branch
Current Plan=p02
Default Exp/Contr=0.3,0.1
English Units
Geom File=g01
Flow File=f02
Flow File=f01
Plan File=p02
Plan File=p01
Y Axis Title=Elevation
X Axis Title(PF)=Main Channel Distance
X Axis Title(XS)=Station
BEGIN DESCRIPTION:
####(Watershed Name)####
LEWIS BRANCH
HCFCD Unit X###-##-##
(Flood Hazard, Floodway) Model
10, 2, 1, 0.2% Event
Filename:  N:\NC_flood\60138\Approximates\Eng\Toisnot_Nahunta\ENG\Lewis_Branch\Lewis Branch.prj
Prepared by:  ________     Date: ________
Reviewed by:  ________     Date: ________
STATUS (Draft RAS, SVSQ, FINAL)
END DESCRIPTION:
DSS Export Rating Curves= 0
DSS Export Rating Curve Sorted= 0
DSS Export Volume Flow Curves= 0
DXF OffsetX= 0
DXF OffsetY= 0
DXF ScaleX= 1
DXF ScaleY= 10

--- Lewis_Branch_FINAL.p02 (plan) ---

Plan Title=Multi_Profile
Program Version=3.13
Short Identifier=Multi_Pro
Geom File=g01
Flow File=f02
Subcritical Flow
K Sum by GR= 0
Std Step Tol= 0.01
Critical Tol= 0.01
Num of Std Step Trials= 20
Max Error Tol= 0.3
Flow Tol Ratio= 0.001
Split Flow NTrial= 30
Split Flow Tol= 0.02
Split Flow Ratio= 0.02
Log Output Level= 0
Friction Slope Method= 1
Unsteady Friction Slope Method= 2
Unsteady Bridges Friction Slope Method= 1
Parabolic Critical Depth
Global Vel Dist= 0 , 0 , 0
Global Log Level= 0
CheckData=True
Encroach Param=-1 ,10,10, 2
Computation Interval=1HOUR
Output Interval=1HOUR
Run HTab= 0
Run UNet= 0
Run PostProcess= 0
UNET Theta= 1
UNET Theta Warmup= 1
UNET ZTol= 0.02
UNET ZSATol= 0.1
UNET MxIter= 20
UNET MaxInSteps= 20
UNET DtIC= 0
UNET DtMin= 0
UNET MaxCRTS= 20
UNET WFStab= 2
UNET SFStab= 1
UNET WFX= 1
UNET SFX= 1
UNET DSS MLevel= 4
UNET DZMax Abort= 100
UNET Convert EG Bridges=-1
UNET Use Existing IB Tables=-1
UNET Froude Reduction=False
UNET Froude Limit= 1
UNET Froude Power= 10
Instantaneous Interval=1HOUR
Write IC File= 0
Echo Input=False
Echo Output=False
Write Detailed= 0
Detailed Automatic Start=False, 10

--- Lewis_Branch_FINAL.p01 (plan) ---

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Plan Title=100 Year Single
Version=Version 3.0.1  Mar 2001
Short Identifier=Plan01
Geom File=g01
Flow File=f01
Encroach River=Lewis Branch
Encroach Reach=Reach - 1
Encroach Node=4201.4
       4      .7
Encroach Node=3500.0
       4      .7
Encroach Node=3000.0
       4      .7
Encroach Node=2500.0
       4      .7
Encroach Node=2000.0
       4      .7
Encroach Node=1500.0
       4      .7
Encroach Node=826.1
       4      .7
Write Velocity= 0

--- Lewis_Branch_FINAL.f02 (steady flow) ---

Flow Title=Multi_Profile
Program Version=3.13
Number of Profiles= 7
Profile Names=10-yr,25-yr,50-yr,500-yr,100-yr-10%,100-yr-20%,100-yr-35%
River Rch & RM=Lewis Branch,Reach - 1       ,4201.4
     269     397     515    1059    1140    1461    1785
Boundary for River Rch & Prof#=Lewis Branch,Reach - 1       , 1
Up Type= 0
Dn Type= 3
Dn Slope=0.0035
DSS Import GetInterval= 0
DSS Import GetPeak= 0
DSS Import FillOption= 0

--- Lewis_Branch_FINAL.f01 (steady flow) ---

Flow Title= 100 Year Single
Version=Version 3.0.1  Mar 2001
Number of Profiles= 2
Profile Names=100-Year,AFW
River Rch & RM=Lewis Branch,Reach - 1       ,4201.4
     652     652
Boundary for River Rch & Prof#=Lewis Branch,Reach - 1       , 1
Up Type= 0
Dn Type= 3
Dn Slope=.0035
DSS Import GetInterval= 0
DSS Import GetPeak= 0
DSS Import FillOption= 0

--- Lewis_Branch_FINAL.g01 (geometry) ---

Geom Title=Geom 01 by CodeH2 for Windows

River Reach=Lewis Branch,Reach - 1
Reach XY= 30
   .084050512430   .445845415266   .108146364823   .447701643563
   .131528749511   .437243020446   .148760431604   .442164189698
   .175221203474   .428010894785   .191833565070   .431702530696
   .226910177986   .421243907578   .250295598558   .400936874188
   .289060811500   .402782692143   .313675765414   .380013556184
   .370288945063   .370781430523   .381980137407   .362168625361
   .419518852891   .363398158703   .428747942667   .355398602269
   .463824555583   .355398602269   .469362009448   .345553227881
   .484747873587   .354169068928   .548128040443   .342474840699
   .554898063535   .332629466310   .602895402137   .331399932968
   .634896663756   .308630797009   .647817389442   .276016286661
   .680431899790   .275403037933   .733353443528   .240942709630
   .772121692355   .181251142799   .814581577091   .159098291454
   .839809779734   .165252029932   .874270108037   .138174973449
   .882269664471   .109255134897   .918629411635   .106179572477

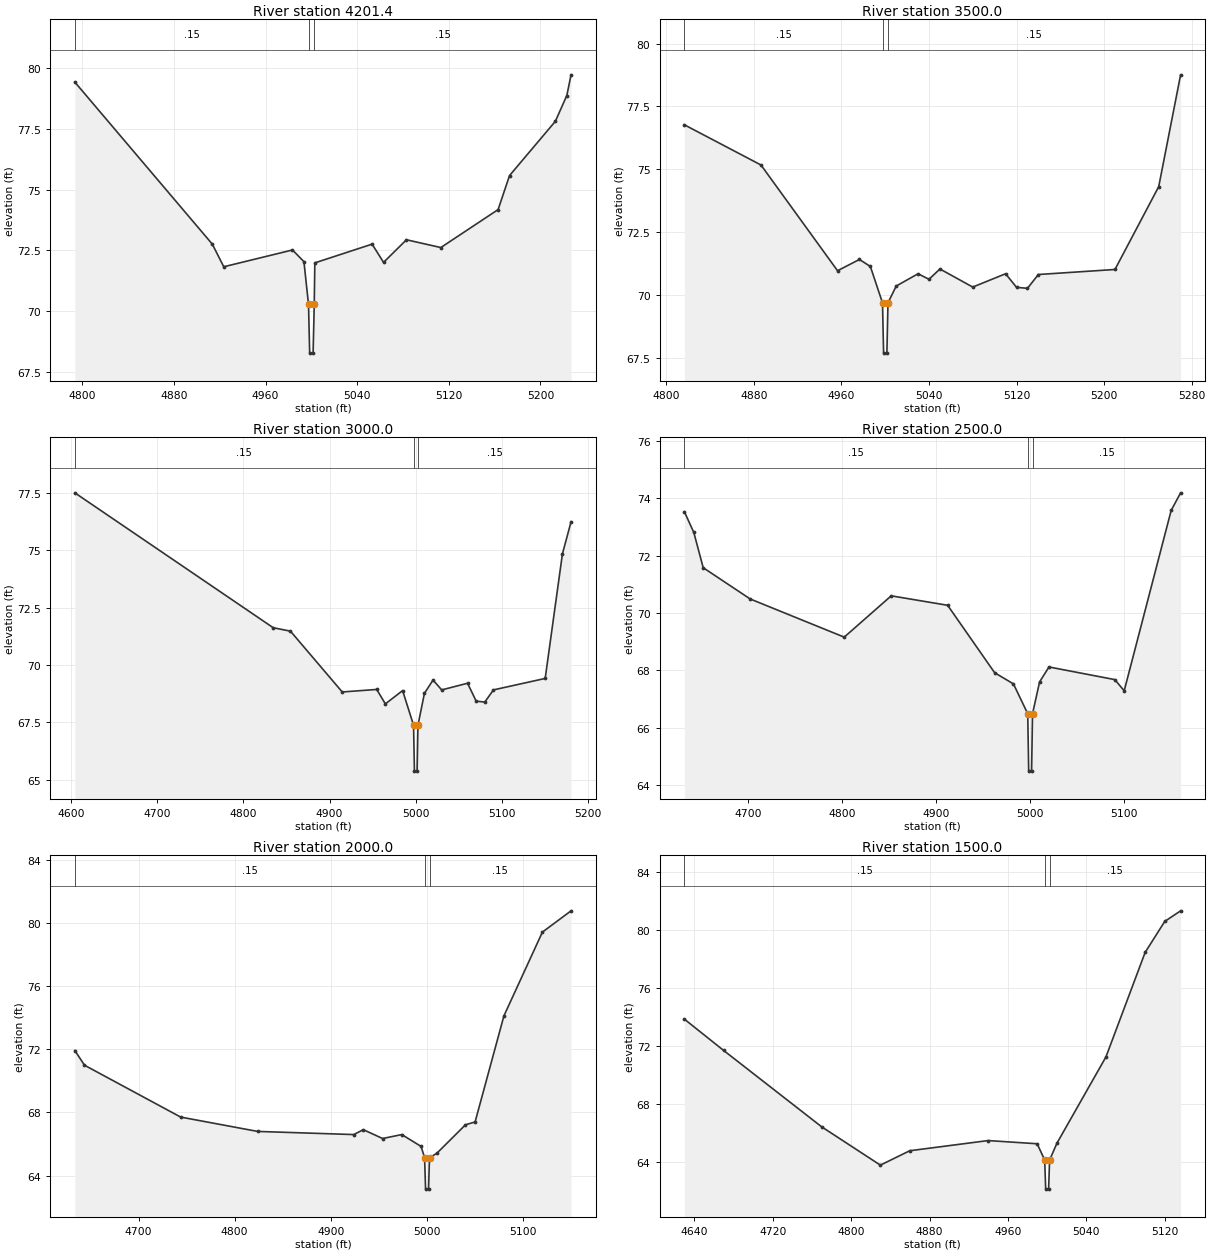
Type RM Length L Ch R = 1 ,4201.4,701.4,701.4,701.4
XS GIS Cut Line= 3
   .113864628822   .500982532750   .083600662258   .445032217996
   .050000000000   .386026200872
BEGIN DESCRIPTION:
Lewis Branch 7.0
END DESCRIPTION:
#Sta/Elev= 19
  4793.5   79.42  4913.5   72.76  4923.5   71.83  4983.5   72.52  4993.5   72.04
  4997.5   70.28  4998.5   68.28  5001.5   68.28  5002.5   70.28    5003   71.99
    5053   72.76    5063   72.01    5083   72.94    5113   72.62    5163   74.18
    5173   75.58    5213   77.81    5223   78.87  5226.7   79.72
#Mann= 3 , 1 , 0
 4793.50    0.15       0  4997.5    0.05       0  5002.5    0.15       0
Bank Sta=4997.50,5002.50
Exp/Cntr=0.3,0.1

Type RM Length L Ch R = 1 ,3500.0,500,500,500
XS GIS Cut Line= 3
   .271069868997   .480349344978   .273429700169   .403396952206
   .271069868997   .317248908297
BEGIN DESCRIPTION:
Lewis Branch 6.0
END DESCRIPTION:
#Sta/Elev= 21
  4816.4   76.77  4886.4   75.17  4956.4   70.96  4976.4   71.41  4986.4   71.13
  4997.5   69.68  4998.5   67.68  5001.5   67.68  5002.5   69.68    5010   70.35
    5030   70.84    5040   70.62    5050   71.03    5080   70.31    5110   70.84
    5120    70.3    5130   70.26    5140   70.81    5210   71.01    5250   74.31
    5270   78.76
#Mann= 3 , 1 , 0
 4816.40    0.15       0  4997.5    0.05       0  5002.5    0.15       0
Bank Sta=4997.50,5002.50
Exp/Cntr=0.3,0.1

Type RM Length L Ch R = 1 ,3000.0,500,500,500
XS GIS Cut Line= 3
   .399781659391   .482314410481   .410279173082   .362781038812
   .412554585153   .301528384278
BEGIN DESCRIPTION:
Lewis Branch 5.0
END DESCRIPTION:
#Sta/Elev= 21
  4604.7   77.51  4834.7   71.63  4854.7   71.48  4914.7   68.83  4954.7   68.94
  4964.7   68.31  4984.7   68.89  4997.4   67.38  4998.4   65.38  5001.5   65.38
  5002.5   67.38    5010   68.77    5020   69.35    5030   68.92    5060   69.21
    5070   68.43    5080   68.39    5090   68.92    5150   69.42    5170   74.85
    5180   76.25
#Mann= 3 , 1 , 0
 4604.70    0.15       0  4997.4    0.05       0  5002.5    0.15       0
Bank Sta=4997.40,5002.50
Exp/Cntr=0.3,0.1

Type RM Length L Ch R = 1 ,2500.0,500,500,500
XS GIS Cut Line= 3
   .558951965066   .466593886463   .544204667456   .340630019234
   .536353711791   .285807860263
BEGIN DESCRIPTION:
Lewis Branch 4.0
END DESCRIPTION:
#Sta/Elev= 19
  4632.2   73.53  4642.2   72.81  4652.2   71.58  4702.2   70.49  4802.2   69.16
  4852.2    70.6  4912.2   70.27  4962.2   67.92  4982.2   67.53  4997.4   66.49
  4998.4   64.49  5001.5   64.49  5002.5   66.49    5010    67.6    5020   68.12
    5090   67.68    5100   67.29    5150   73.58    5160   74.19
#Mann= 3 , 1 , 0
 4632.20    0.15       0  4997.4    0.05       0  5002.5    0.15       0
Bank Sta=4997.40,5002.50
Exp/Cntr=0.3,0.1

Type RM Length L Ch R = 1 ,2000.0,500,500,500
XS GIS Cut Line= 3
   .702401746725   .375218340612   .653959023972   .275139712171
   .637554585153   .232751091703
BEGIN DESCRIPTION:
Lewis Branch 3.0
END DESCRIPTION:
#Sta/Elev= 19
  4633.8   71.93  4643.8      71  4743.8   67.71  4823.8    66.8  4923.8    66.6
  4933.8   66.91  4953.8   66.35  4973.8    66.6  4993.8   65.85  4997.5   65.14
  4998.5   63.14  5001.6   63.14  5002.6   65.14    5010    65.4    5040   67.22
    5050    67.4    5080   74.13    5120   79.44  5149.8   80.79
#Mann= 3 , 1 , 0
 4633.80    0.15       0  4997.5    0.05       0  5002.6    0.15       0
Bank Sta=4997.50,5002.60
Exp/Cntr=0.3,0.1

Type RM Length L Ch R = 1 ,1500.0,673.9,673.9,673.9
XS GIS Cut Line= 3
   .824235807859   .283842794759   .763679825776   .189173290652
   .730895196506   .163973799125
BEGIN DESCRIPTION:
Lewis Branch 2.0
END DESCRIPTION:
#Sta/Elev= 16
  4629.8   73.85  4669.8    71.7  4769.8   66.45  4829.8   63.81  4859.8    64.8
  4939.8    65.5  4989.8   65.28  4997.5   64.16  4998.5   62.16  5001.5   62.16
  5002.5   64.16    5010   65.32    5060   71.25    5100   78.44    5120   80.57
  5136.2    81.3
#Mann= 3 , 1 , 0
 4629.80    0.15       0  4997.5    0.05       0  5002.5    0.15       0
Bank Sta=4997.50,5002.50
Exp/Cntr=0.3,0.1

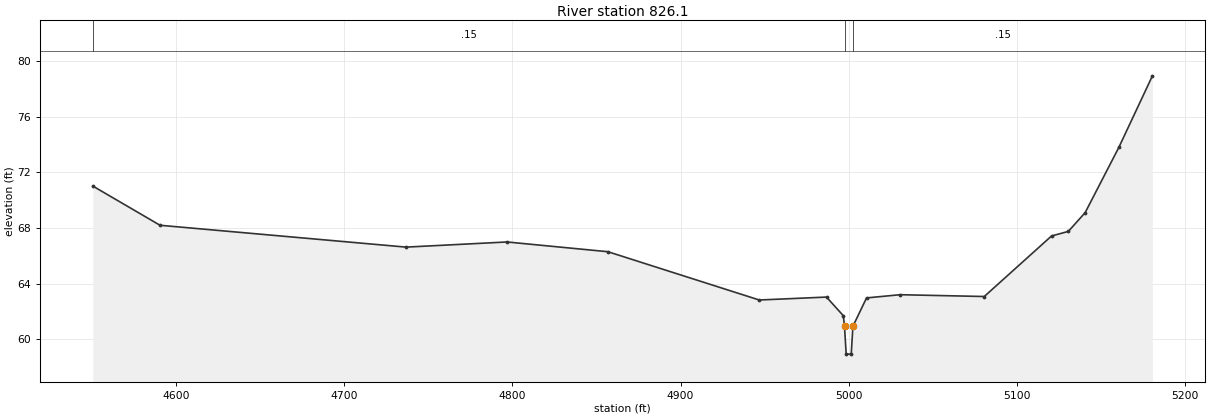
Type RM Length L Ch R = 1 ,826.1,0,0,0
XS GIS Cut Line= 4
   .950000000000   .236681222706   .948890520540   .180148201105
   .918558951966   .106004366813   .880240174672   .050000000000
BEGIN DESCRIPTION:
Lewis Branch 1.0
END DESCRIPTION:
#Sta/Elev= 20
  4550.5   71.02  4590.5    68.2  4736.8   66.63  4796.8      67  4856.8    66.3
  4946.8   62.83  4986.8   63.04  4996.8    61.7  4997.5   60.94  4998.5   58.94
  5001.5   58.94  5002.5   60.94  5010.6   62.98  5030.6   63.21  5080.6   63.08
  5120.6   67.43  5130.6   67.76  5140.6   69.11  5160.6   73.79  5180.6   78.94
#Mann= 3 , 1 , 0
 4550.50    0.15       0  4997.5    0.05       0  5002.5    0.15       0
Bank Sta=4997.50,5002.50
Exp/Cntr=0.3,0.1

Chan Stop Cuts=-1