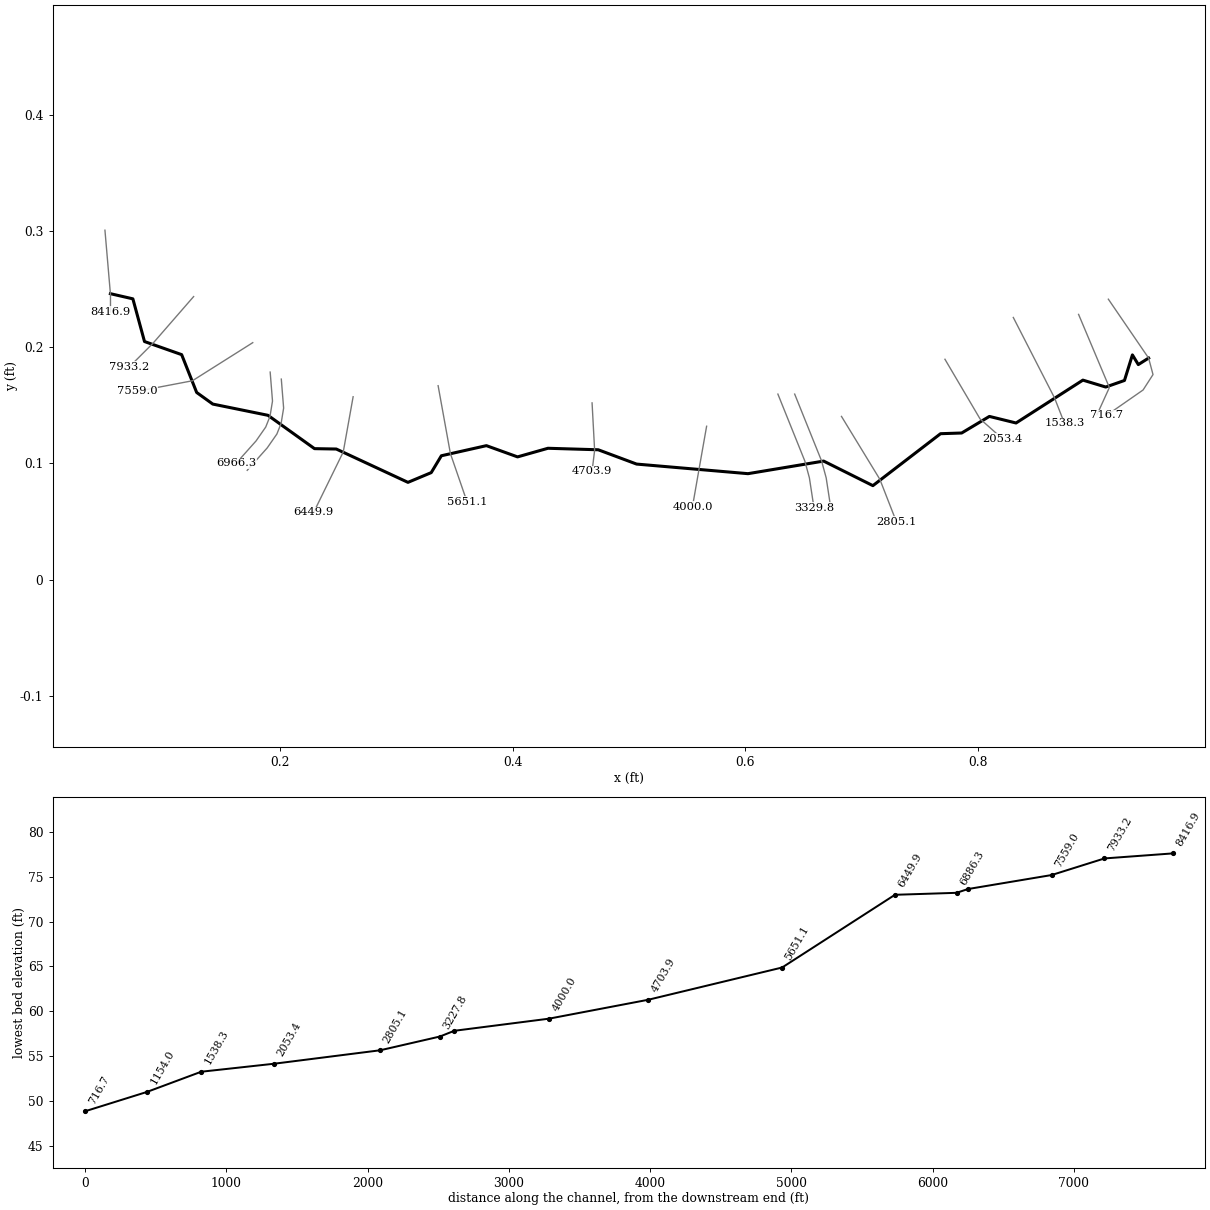
--- Reeders_Fork_FINAL.prj (project) ---

Proj Title=Reeders Fork
Current Plan=p02
Default Exp/Contr=0.3,0.1
English Units
Geom File=g01
Flow File=f02
Flow File=f01
Plan File=p02
Plan File=p01
Y Axis Title=Elevation
X Axis Title(PF)=Main Channel Distance
X Axis Title(XS)=Station
BEGIN DESCRIPTION:
####(Watershed Name)####
REEDERS FORK
HCFCD Unit X###-##-##
(Flood Hazard, Floodway) Model
10, 2, 1, 0.2% Event
Filename:  N:\NC_flood\60138\Approximates\Eng\Toisnot_Nahunta\ENG\Reeders_Fork\Reeders Fork.prj
Prepared by:  ________     Date: ________
Reviewed by:  ________     Date: ________
STATUS (Draft RAS, SVSQ, FINAL)
END DESCRIPTION:
DSS Export Rating Curves= 0
DSS Export Rating Curve Sorted= 0
DSS Export Volume Flow Curves= 0
DXF OffsetX= 0
DXF OffsetY= 0
DXF ScaleX= 1
DXF ScaleY= 10

--- Reeders_Fork_FINAL.p02 (plan) ---

Plan Title=Multi_Profile
Program Version=3.13
Short Identifier=Multi_Pro
Geom File=g01
Flow File=f02
Subcritical Flow
K Sum by GR= 0
Std Step Tol= 0.01
Critical Tol= 0.01
Num of Std Step Trials= 20
Max Error Tol= 0.3
Flow Tol Ratio= 0.001
Split Flow NTrial= 30
Split Flow Tol= 0.02
Split Flow Ratio= 0.02
Log Output Level= 0
Friction Slope Method= 1
Unsteady Friction Slope Method= 2
Unsteady Bridges Friction Slope Method= 1
Parabolic Critical Depth
Global Vel Dist= 0 , 0 , 0
Global Log Level= 0
CheckData=True
Encroach Param=-1 ,10,10, 2
Computation Interval=1HOUR
Output Interval=1HOUR
Run HTab= 0
Run UNet= 0
Run PostProcess= 0
UNET Theta= 1
UNET Theta Warmup= 1
UNET ZTol= 0.02
UNET ZSATol= 0.1
UNET MxIter= 20
UNET MaxInSteps= 20
UNET DtIC= 0
UNET DtMin= 0
UNET MaxCRTS= 20
UNET WFStab= 2
UNET SFStab= 1
UNET WFX= 1
UNET SFX= 1
UNET DSS MLevel= 4
UNET DZMax Abort= 100
UNET Convert EG Bridges=-1
UNET Use Existing IB Tables=-1
UNET Froude Reduction=False
UNET Froude Limit= 1
UNET Froude Power= 10
Instantaneous Interval=1HOUR
Write IC File= 0
Echo Input=False
Echo Output=False
Write Detailed= 0
Detailed Automatic Start=False, 10

--- Reeders_Fork_FINAL.p01 (plan) ---

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Plan Title=100 Year Single
Version=Version 3.0.1  Mar 2001
Short Identifier=Plan01
Geom File=g01
Flow File=f01
Encroach River=Reeders Fork
Encroach Reach=Reach - 1
Encroach Node=8416.9
       4      .7
Encroach Node=7933.2
       1    4895    5020
Encroach Node=7559.0
       1    4970    5045
Encroach Node=6966.3
       4      .7
Encroach Node=6926.3
       4      .7
Encroach Node=6886.3
       4      .7
Encroach Node=6449.9
       1    4979    5065
Encroach Node=5651.1
       1    4970    5055
Encroach Node=4703.9
       1    4950    5020
Encroach Node=4000.0
       4      .7
Encroach Node=3329.8
       4      .7
Encroach Node=3278.8
       4      .7
Encroach Node=3227.8
       4      .7
Encroach Node=2805.1
       1    4990    5080
Encroach Node=2053.4
       1    4910    5070
Encroach Node=1538.3
       4      .7
Encroach Node=1154.0
       4      .7
Encroach Node=716.7
       4      .7
Write Velocity= 0

--- Reeders_Fork_FINAL.f02 (steady flow) ---

Flow Title=Multi_Profile
Program Version=3.13
Number of Profiles= 7
Profile Names=10-yr,25-yr,50-yr,500-yr,100-yr-10%,100-yr-20%,100-yr-35%
River Rch & RM=Reeders Fork,Reach - 1       ,8416.9
     234     347     450     935    1005    1287    1573
River Rch & RM=Reeders Fork,Reach - 1       ,4000.0
     259     382     496    1023    1100    1409    1722
Boundary for River Rch & Prof#=Reeders Fork,Reach - 1       , 1
Up Type= 0
Dn Type= 3
Dn Slope=0.0037
DSS Import GetInterval= 0
DSS Import GetPeak= 0
DSS Import FillOption= 0

--- Reeders_Fork_FINAL.f01 (steady flow) ---

Flow Title= 100 Year Single
Version=Version 3.0.1  Mar 2001
Number of Profiles= 2
Profile Names=100-Year,AFW
River Rch & RM=Reeders Fork,Reach - 1       ,8416.9
     572
River Rch & RM=Reeders Fork,Reach - 1       ,4000.0
     628
Boundary for River Rch & Prof#=Reeders Fork,Reach - 1       , 1
Up Type= 0
Dn Type= 3
Dn Slope=.0037
DSS Import GetInterval= 0
DSS Import GetPeak= 0
DSS Import FillOption= 0

--- Reeders_Fork_FINAL.g01 (geometry) ---

Geom Title=Geom 01 by CodeH2 for Windows

River Reach=Reeders Fork,Reach - 1
Reach XY= 30
   .054675118645   .246049049350   .073974923979   .241609362965
   .083966148793   .204869354096   .115871648457   .193589303677
   .128762730883   .161037978024   .142620432513   .151048166397
   .189996078999   .141379147984   .229959565068   .112695712334
   .248651775904   .112373505933   .310207330422   .083691483469
   .330188366863   .092070263090   .338890766072   .106572377523
   .377564013350   .115274776731   .404312797405   .105605758319
   .430418581845   .113017918736   .473604131927   .111729093130
   .506541257349   .099418830138   .602194162971   .091167237254
   .667165387980   .101996481349   .709449325414   .080855219225
   .767551053418   .125561357413   .785693534912   .126156308706
   .809485933917   .140430900198   .832386612574   .134780982686
   .889785987151   .171659483781   .909413727100   .165711384030
   .925474585659   .171361301541   .932314405758   .193370259851
   .937370785161   .185042354925   .946220072956   .190632610895

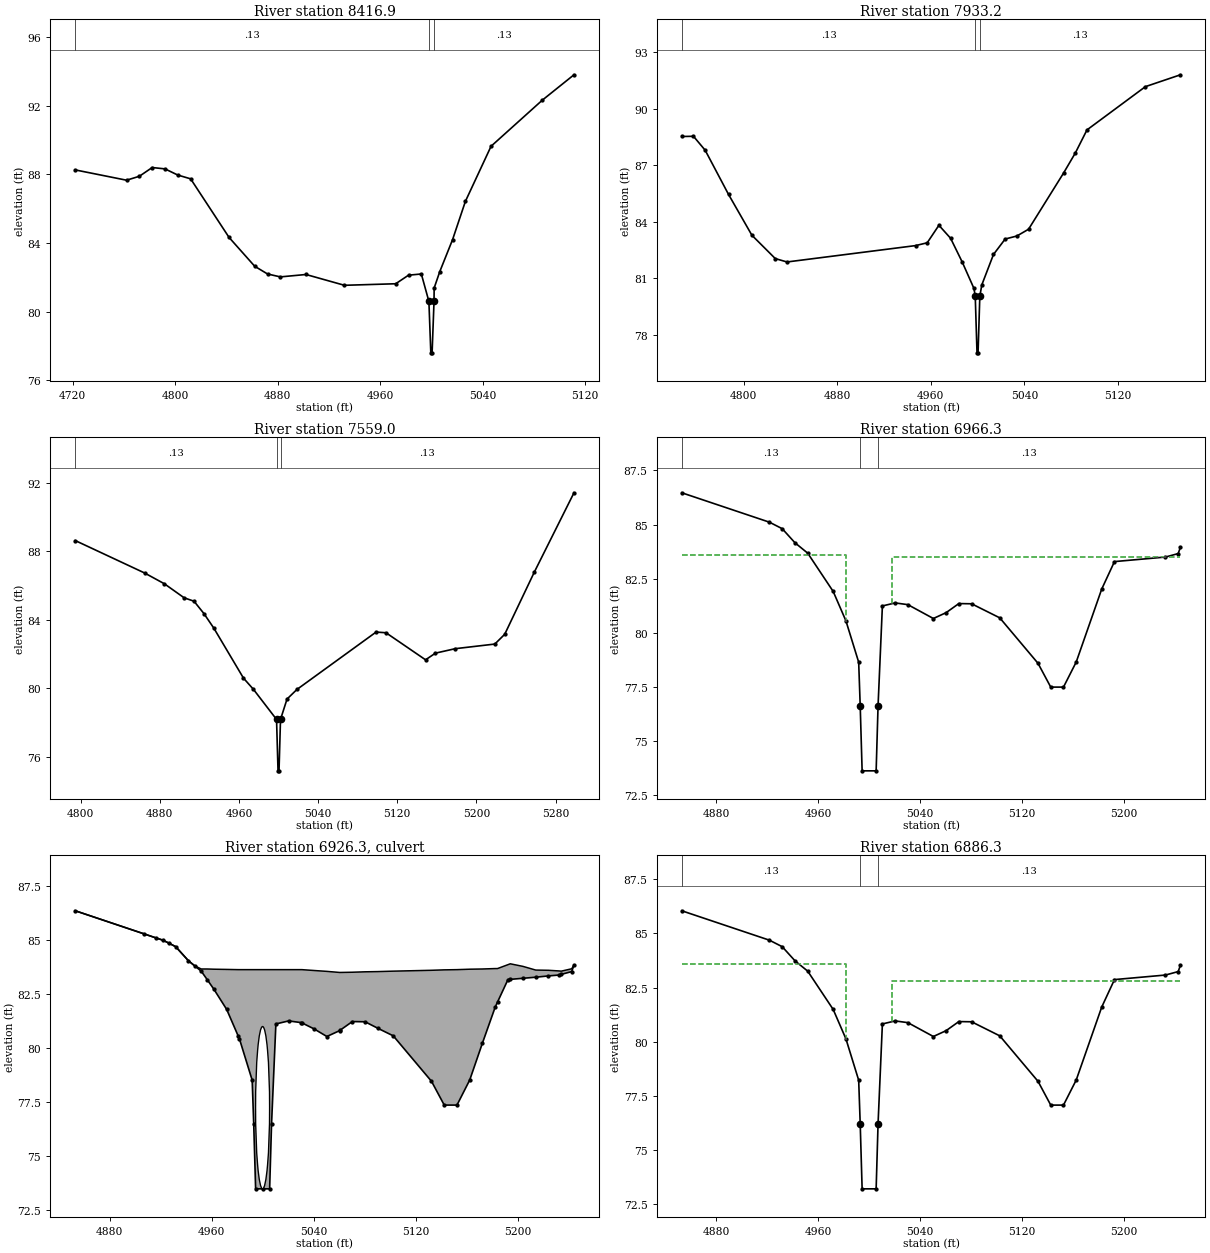
Type RM Length L Ch R = 1 ,8416.9,483.7,483.7,483.7
XS GIS Cut Line= 3
   .050000000000   .300667409705   .054759507779   .245139818948
   .054759507779   .230332461411
BEGIN DESCRIPTION:
Reeders Fork 11.0
END DESCRIPTION:
#Sta/Elev= 27
  4722.1   88.26  4762.1   87.66  4772.1   87.89  4782.1    88.4  4792.1   88.32
  4802.1   87.96  4812.1   87.74  4842.1   84.32  4862.1   82.64  4872.1   82.19
  4882.1   82.02  4902.1   82.16  4932.1   81.53  4972.1   81.62  4982.1   82.12
  4992.1   82.19    4998   80.59  4999.5   77.59  5000.5   77.59    5002   80.59
  5002.1   81.37  5006.5   82.33  5016.5    84.2  5026.5   86.43  5046.5   89.64
  5086.5   92.33  5111.2   93.81
#Mann= 3 , 1 , 0
 4722.10    0.13       0    4998   0.047       0    5002    0.13       0
Bank Sta=4998.00,5002.00
Exp/Cntr=0.3,0.1

Type RM Length L Ch R = 1 ,7933.2,374.2,374.2,374.2
XS GIS Cut Line= 3
   .126152124468   .243553316354   .091249067419   .203361917330
   .071153367907   .183266217818
BEGIN DESCRIPTION:
Reeders Fork 10.0
END DESCRIPTION:
#Sta/Elev= 27
  4746.9   88.53  4756.9   88.54  4766.9    87.8  4786.9   85.45  4806.9   83.28
  4826.9   82.04  4836.9   81.86  4946.9   82.73  4956.9   82.88  4966.9   83.81
  4976.9   83.12  4986.9   81.85  4996.9   80.45    4998   80.03  4999.5   77.03
  5000.4   77.03  5001.9   80.03  5003.6   80.64  5013.6   82.26  5023.6   83.08
  5033.6   83.24  5043.6    83.6  5073.6   86.59  5083.6   87.65  5093.6   88.88
  5143.6   91.18  5173.6   91.81
#Mann= 3 , 1 , 0
 4746.90    0.13       0    4998   0.047       0  5001.9    0.13       0
Bank Sta=4998.00,5001.90
Exp/Cntr=0.3,0.1

Type RM Length L Ch R = 1 ,7559.0,592.7,592.7,592.7
XS GIS Cut Line= 3
   .176920207445   .203890751527   .125094456073   .171103031271
   .078028212478   .162112849909
BEGIN DESCRIPTION:
Reeders Fork 9.0
END DESCRIPTION:
#Sta/Elev= 24
  4794.6   88.62  4864.6   86.73  4884.6    86.1  4904.6   85.28  4914.6   85.08
  4924.6   84.36  4934.6   83.51  4964.6   80.59  4974.6   79.94    4998   78.18
  4999.5   75.18  5000.5   75.18    5002   78.18  5008.6   79.37  5018.6   79.93
  5098.6   83.28  5108.6   83.24  5148.6   81.66  5158.6   82.05  5178.6   82.31
  5218.6   82.58  5228.6   83.15  5258.6   86.79  5298.6   91.41
#Mann= 3 , 1 , 0
 4794.60    0.13       0    4998   0.047       0    5002    0.13       0
Bank Sta=4998.00,5002.00
Exp/Cntr=0.5,0.3

Type RM Length L Ch R = 1 ,6966.3,80,80,80
XS GIS Cut Line= 6
   .191882930106   .178578119290   .193883495036   .153638121398
   .191738358544   .140529982062   .188082041911   .131304890233
   .179751289235   .119320303575   .162622043134   .100085059688
BEGIN DESCRIPTION:
Upstream Section of Bridge/Culvert/Weir
END DESCRIPTION:
#Sta/Elev= 29
    4853   86.47  4921.8   85.11  4931.8   84.81  4941.8   84.16  4951.8   83.68
  4971.8   81.91  4981.8   80.55  4991.8   78.64    4993   76.62  4994.5   73.62
  5005.5   73.62    5007   76.62  5010.4   81.24  5020.4   81.38  5030.4    81.3
  5050.4   80.66  5060.4   80.93  5070.4   81.35  5080.4   81.34  5102.5   80.69
  5132.5   78.59  5142.5   77.49  5152.5   77.49  5162.5   78.65  5182.5   82.02
  5192.5   83.29  5232.5    83.5  5242.5   83.66  5244.3   83.96
#Mann= 3 , 1 , 0
 4853.00    0.13       0    4993   0.047       0    5007    0.13       0
#XS Ineff= 2 , 0
       0    4982    83.6    5018       0    83.5
Bank Sta=4993.00,5007.00
Exp/Cntr=0.5,0.3

Type RM Length L Ch R = 2 ,6926.3,,,
BEGIN DESCRIPTION:
Burrellfield Rd-TOR
Structure ID: Burrellfield Rd-Culvert
Approximate Survey Structure
END DESCRIPTION:
Bridge Culvert--1,0,-1,-1, 0
Deck Dist Width WeirC Skew NumUp NumDn MinLoCord MaxHiCord MaxSubmerge Is_Ogee
10,60,3,,48,48,,,0.95,0,1,1,,
    4853  4906.6  4916.6  4921.8  4926.6  4931.8  4941.8  4946.6  4951.8  4956.6
  4961.8  4971.8  4980.7  4981.8  4991.8    4993  4994.5    5000  5005.5    5007
  5010.4  5020.4  5030.4  5030.8  5040.4  5050.4  5060.4  5060.8  5070.4  5080.4
  5090.4  5102.5  5132.5  5142.5  5152.5  5162.5  5172.5  5182.5  5184.3  5192.5
  5194.3  5204.3  5214.3  5224.3  5232.5  5234.3  5242.5  5244.3
   86.35   85.29   85.09   84.99   84.85   84.69   84.04   83.81   83.66   83.66
   83.65   83.64   83.63   83.63   83.63   83.63   83.63   83.63   83.63   83.63
   83.63   83.63   83.63   83.63   83.59   83.55    83.5    83.5   83.51   83.53
   83.54   83.56    83.6   83.62   83.63   83.65   83.66   83.68   83.68   83.86
    83.9   83.78   83.61    83.6   83.57   83.56   83.67   83.84
   86.35   85.29   85.09   84.99   84.85   84.69   84.04   83.81   83.56   83.16
   82.72   81.79   80.58   80.43   78.52    76.5    73.5    73.5    73.5    76.5
   81.12   81.26   81.18   81.17   80.89   80.54   80.81   80.83   81.23   81.22
   80.92   80.57   78.47   77.37   77.37   78.53   80.24    81.9   82.13   83.17
   83.18   83.23   83.28   83.34   83.38   83.41   83.54   83.84
    4853  4906.6  4916.6  4921.8  4926.6  4931.8  4941.8  4946.6  4951.8  4956.6
  4961.8  4971.8  4980.7  4981.8  4991.8    4993  4994.5    5000  5005.5    5007
  5010.4  5020.4  5030.4  5030.8  5040.4  5050.4  5060.4  5060.8  5070.4  5080.4
  5090.4  5102.5  5132.5  5142.5  5152.5  5162.5  5172.5  5182.5  5184.3  5192.5
  5194.3  5204.3  5214.3  5224.3  5232.5  5234.3  5242.5  5244.3
    86.2   85.15   84.95   84.85   84.71   84.55    83.9   83.66   83.66   83.66
   83.65   83.64   83.63   83.63   83.63   83.63   83.63   83.63   83.63   83.63
   83.63   83.63   83.63   83.63   83.59   83.55    83.5    83.5   83.51   83.53
   83.54   83.56    83.6   83.62   83.63   83.65   83.66   83.68   83.68   83.86
    83.9   83.78   83.61    83.6   83.57   83.56   83.67   83.69
   86.05   84.99   84.79   84.69   84.55   84.39   83.74   83.51   83.26   82.86
   82.42   81.49   80.28   80.13   78.22    76.2    73.2    73.2    73.2    76.2
   80.82   80.96   80.88   80.87   80.59   80.24   80.51   80.53   80.93   80.92
   80.62   80.27   78.17   77.07   77.07   78.23   79.94    81.6   81.83   82.87
   82.88   82.93   82.98   83.04   83.08   83.11   83.24   83.54
BR Coef= 1 , 0 , 0 ,1.25, 0 ,,,0.8,-1,2,0,
Wspro=,,,, 1 ,,,, 0 ,,,, 0 ,,,,-1 ,-1 ,-1 , 0 , 0 , 0 , 0 , 0
Culvert=4,7.5,11.0,60.0,0.015,0.9,1.0,29,1,73.50,4999.96,73.20,4999.96,Culvert #1  ,0,10
BC Design=,, 0 ,, 0 ,,,,,,
BR U #Sta/Elev= 48
    4853   86.35  4906.6   85.29  4916.6   85.09  4921.8   84.99  4926.6   84.85
  4931.8   84.69  4941.8   84.04  4946.6   83.81  4951.8   83.56  4956.6   83.16
  4961.8   82.72  4971.8   81.79  4980.7   80.58  4981.8   80.43  4991.8   78.52
    4993    76.5  4994.5    73.5    5000    73.5  5005.5    73.5    5007    76.5
  5010.4   81.12  5020.4   81.26  5030.4   81.18  5030.8   81.17  5040.4   80.89
  5050.4   80.54  5060.4   80.81  5060.8   80.83  5070.4   81.23  5080.4   81.22
  5090.4   80.92  5102.5   80.57  5132.5   78.47  5142.5   77.37  5152.5   77.37
  5162.5   78.53  5172.5   80.24  5182.5    81.9  5184.3   82.13  5192.5   83.17
  5194.3   83.18  5204.3   83.23  5214.3   83.28  5224.3   83.34  5232.5   83.38
  5234.3   83.41  5242.5   83.54  5244.3   83.84
BR U #Mann= 3
 4853.00    0.13    4993   0.047    5007    0.13
BR U Banks=4993.00,5007.00
BR D #Sta/Elev= 48
    4853   86.05  4906.6   84.99  4916.6   84.79  4921.8   84.69  4926.6   84.55
  4931.8   84.39  4941.8   83.74  4946.6   83.51  4951.8   83.26  4956.6   82.86
  4961.8   82.42  4971.8   81.49  4980.7   80.28  4981.8   80.13  4991.8   78.22
    4993    76.2  4994.5    73.2    5000    73.2  5005.5    73.2    5007    76.2
  5010.4   80.82  5020.4   80.96  5030.4   80.88  5030.8   80.87  5040.4   80.59
  5050.4   80.24  5060.4   80.51  5060.8   80.53  5070.4   80.93  5080.4   80.92
  5090.4   80.62  5102.5   80.27  5132.5   78.17  5142.5   77.07  5152.5   77.07
  5162.5   78.23  5172.5   79.94  5182.5    81.6  5184.3   81.83  5192.5   82.87
  5194.3   82.88  5204.3   82.93  5214.3   82.98  5224.3   83.04  5232.5   83.08
  5234.3   83.11  5242.5   83.24  5244.3   83.54
BR D #Mann= 3
 4853.00    0.13    4993   0.047    5007    0.13
BR D Banks=4993.00,5007.00

Type RM Length L Ch R = 1 ,6886.3,436.4,436.4,436.4
XS GIS Cut Line= 6
   .201441227611   .172540487101   .203441792542   .147600489210
   .201296656049   .134492349874   .197640339417   .125267258045
   .189309586740   .113282671387   .172180340640   .094047427499
BEGIN DESCRIPTION:
Downstream Section of Bridge/Culvert/Weir
END DESCRIPTION:
#Sta/Elev= 29
    4853   86.05  4921.8   84.69  4931.8   84.39  4941.8   83.74  4951.8   83.26
  4971.8   81.49  4981.8   80.13  4991.8   78.22    4993    76.2  4994.5    73.2
  5005.5    73.2    5007    76.2  5010.4   80.82  5020.4   80.96  5030.4   80.88
  5050.4   80.24  5060.4   80.51  5070.4   80.93  5080.4   80.92  5102.5   80.27
  5132.5   78.17  5142.5   77.07  5152.5   77.07  5162.5   78.23  5182.5    81.6
  5192.5   82.87  5232.5   83.08  5242.5   83.24  5244.3   83.54
#Mann= 3 , 1 , 0
 4853.00    0.13       0    4993   0.047       0    5007    0.13       0
#XS Ineff= 2 , 0
       0    4982    83.6    5018       0    82.8
Bank Sta=4993.00,5007.00
Exp/Cntr=0.5,0.3

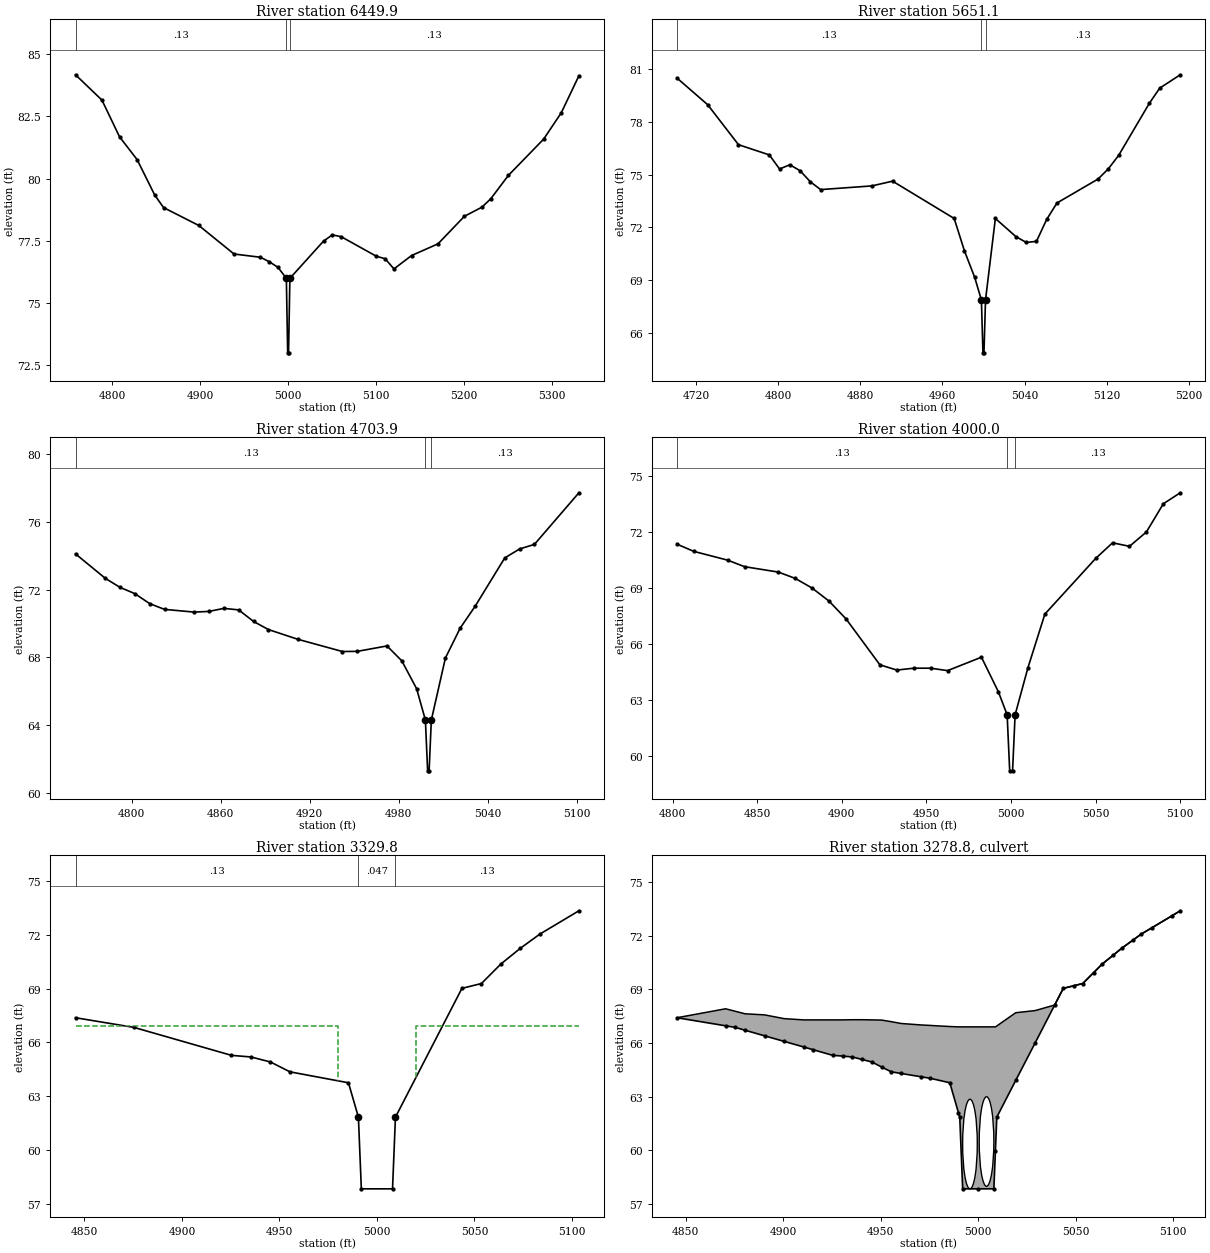
Type RM Length L Ch R = 1 ,6449.9,798.8,798.8,798.8
XS GIS Cut Line= 3
   .263120181670   .157353342130   .254635275328   .109836038334
   .229274793018   .057932512964
BEGIN DESCRIPTION:
Reeders Fork 8.0
END DESCRIPTION:
#Sta/Elev= 30
  4758.6   84.18  4788.6   83.16  4808.6   81.68  4828.6   80.76  4848.6   79.33
  4858.6   78.83  4898.6   78.11  4938.6   76.96  4968.6   76.83  4978.6   76.65
  4988.6   76.42    4998   75.98  4999.5   72.98  5000.5   72.98    5002   75.98
  5040.2   77.48  5050.2   77.73  5060.2   77.66  5100.2   76.87  5110.2   76.77
  5120.2   76.36  5140.2    76.9  5170.2   77.37  5200.2   78.48  5220.2   78.85
  5230.2   79.19  5250.2   80.13  5290.2   81.59  5310.2   82.65  5330.2   84.14
#Mann= 3 , 1 , 0
 4758.60    0.13       0    4998   0.047       0    5002    0.13       0
Bank Sta=4998.00,5002.00
Exp/Cntr=0.3,0.1

Type RM Length L Ch R = 1 ,5651.1,947.2,947.2,947.2
XS GIS Cut Line= 3
   .336099300951   .166872357689   .346655074711   .108452281953
   .360954508243   .066922694326
BEGIN DESCRIPTION:
Reeders Fork 7.0
END DESCRIPTION:
#Sta/Elev= 30
  4701.5   80.49  4731.5   78.97  4761.5    76.7  4791.5   76.12  4801.5   75.32
  4811.5   75.56  4821.5   75.22  4831.5   74.59  4841.5   74.15  4891.5   74.36
  4911.5   74.63  4971.5   72.51  4981.5   70.67  4991.5   69.16    4998   67.88
  4999.5   64.88  5000.5   64.88    5002   67.88  5011.6   72.51  5031.6   71.48
  5041.6   71.15  5051.6   71.21  5061.6   72.46  5071.6   73.39  5111.6   74.75
  5121.6   75.33  5131.6   76.09  5161.6   79.06  5171.6   79.91  5191.6   80.67
#Mann= 3 , 1 , 0
 4701.50    0.13       0    4998   0.047       0    5002    0.13       0
Bank Sta=4998.00,5002.00
Exp/Cntr=0.3,0.1

Type RM Length L Ch R = 1 ,4703.9,703.9,703.9,703.9
XS GIS Cut Line= 3
   .468307850374   .152065000154   .470501270874   .111219794716
   .468307850374   .093364404211
BEGIN DESCRIPTION:
Reeders Fork 6.0
END DESCRIPTION:
#Sta/Elev= 29
  4762.1   74.11  4782.1   72.67  4792.1   72.13  4802.1   71.76  4812.1   71.17
  4822.1   70.83  4842.1   70.67  4852.1   70.71  4862.1   70.89  4872.1    70.8
  4882.1   70.12  4892.1   69.64  4912.1   69.06  4942.1   68.34  4952.1   68.35
  4972.1   68.67  4982.1   67.79  4992.1   66.14    4998   64.29  4999.5   61.29
  5000.5   61.29    5002   64.29  5011.5   67.96  5021.5   69.73  5031.5   71.01
  5051.5   73.87  5061.5    74.4  5071.5   74.67  5101.5   77.72
#Mann= 3 , 1 , 0
 4762.10    0.13       0    4998   0.047       0    5002    0.13       0
Bank Sta=4998.00,5002.00
Exp/Cntr=0.3,0.1

Type RM Length L Ch R = 1 ,4000.0,670.2,670.2,670.2
XS GIS Cut Line= 3
   .566671011144   .131969300642   .560842718276   .098915299161
   .554507824597   .062692020743
BEGIN DESCRIPTION:
Reeders Fork 5.0
END DESCRIPTION:
#Sta/Elev= 28
  4802.5   71.33  4812.5   70.94  4832.5   70.47  4842.5   70.12  4862.5   69.83
  4872.5   69.49  4882.5   68.97  4892.5   68.27  4902.5   67.32  4922.5   64.86
  4932.5   64.58  4942.5   64.68  4952.5   64.68  4962.5   64.55  4982.5   65.27
  4992.5   63.42  4997.7   62.18  4999.2   59.18  5000.9   59.18  5002.4   62.18
    5010   64.71    5020   67.58    5050   70.56    5060    71.4    5070   71.21
    5080   71.98    5090   73.49    5100   74.08
#Mann= 3 , 1 , 0
 4802.50    0.13       0  4997.7   0.047       0  5002.4    0.13       0
Bank Sta=4997.70,5002.40
Exp/Cntr=0.5,0.3

Type RM Length L Ch R = 1 ,3329.8,102,102,102
XS GIS Cut Line= 4
   .627871634729   .159645521318   .650989035853   .102097948307
   .654923912641   .087588090155   .658884591859   .061634352349
BEGIN DESCRIPTION:
Upstream Section of Bridge/Culvert/Weir
END DESCRIPTION:
#Sta/Elev= 17
  4845.4   67.38  4875.4   66.84  4925.4   65.28  4935.4   65.19  4945.4   64.91
  4955.4   64.36  4985.4   63.75  4990.5   61.83    4992   57.83    5008   57.83
  5009.5   61.83  5043.6   69.02  5053.6   69.29  5063.6   70.38  5073.6   71.26
  5083.6   72.05  5103.6   73.35
#Mann= 3 , 1 , 0
 4845.40    0.13       0  4990.5   0.047       0  5009.5    0.13       0
#XS Ineff= 2 , 0
       0    4980    66.9    5020       0    66.9
Bank Sta=4990.50,5009.50
Exp/Cntr=0.5,0.3

Type RM Length L Ch R = 2 ,3278.8,,,
BEGIN DESCRIPTION:
Grand Sand Hole Rd-TOR
Structure ID: Grand Sand Hill Rd-Culvert
Approximate Survey Structure
END DESCRIPTION:
Bridge Culvert--1,0,-1,-1, 0
Deck Dist Width WeirC Skew NumUp NumDn MinLoCord MaxHiCord MaxSubmerge Is_Ogee
10,82,3,,41,41,,,0.95,0,1,1,,
  4845.4  4870.4  4875.4  4880.4  4890.4  4900.4  4910.4  4915.4  4925.4  4930.4
  4935.4  4940.4  4945.4  4950.4  4955.4  4960.4  4970.4  4975.4  4985.4  4989.8
  4990.5    4992    5000    5008  5008.8  5009.5  5019.2  5029.2  5039.2  5043.6
  5049.2  5053.6  5059.2  5063.6  5069.2  5073.6  5079.2  5083.6  5089.2  5099.2
  5103.6
   67.41   67.91   67.77   67.63   67.57   67.36   67.29   67.29   67.29   67.29
    67.3    67.3   67.29   67.28   67.19   67.09   67.01   66.98   66.92    66.9
    66.9    66.9    66.9    66.9    66.9   66.95   67.69   67.81   68.12   69.05
    69.2   69.32   69.93   70.41    70.9   71.29   71.73   72.08   72.44   73.09
   73.38
   67.41   66.96   66.87   66.71    66.4   66.09   65.78   65.62   65.31   65.27
   65.22   65.08   64.94   64.66   64.39    64.3   64.12   64.03   63.78   62.12
   61.86   57.86   57.86   57.86   59.99   61.86   63.91   66.01   68.12   69.05
    69.2   69.32   69.93   70.41    70.9   71.29   71.73   72.08   72.44   73.09
   73.38
  4845.4  4870.4  4875.4  4880.4  4890.4  4900.4  4910.4  4915.4  4925.4  4930.4
  4935.4  4940.4  4945.4  4950.4  4955.4  4960.4  4970.4  4975.4  4985.4  4989.8
  4990.5    4992    5000    5008  5008.8  5009.5  5019.2  5029.2  5039.2  5043.6
  5049.2  5053.6  5059.2  5063.6  5069.2  5073.6  5079.2  5083.6  5089.2  5099.2
  5103.6
   67.21   67.91   67.77   67.63   67.57   67.36   67.29   67.29   67.29   67.29
    67.3    67.3   67.29   67.28   67.19   67.09   67.01   66.98   66.92    66.9
    66.9    66.9    66.9    66.9    66.9   66.95   67.69   67.81   68.03   68.86
   69.01   69.13   69.74   70.22   70.71    71.1   71.54   71.89   72.25    72.9
   73.18
      67   66.55   66.46    66.3   65.99   65.68   65.37   65.21    64.9   64.86
   64.81   64.67   64.53   64.25   63.98   63.89   63.71   63.62   63.37   61.71
   61.45   57.45   57.45   57.45   59.58   61.45    63.5    65.6   67.71   68.64
   68.79   68.91   69.52      70   70.49   70.88   71.32   71.67   72.03   72.68
   72.97
BR Coef= 1 , 0 , 0 ,1.25, 0 ,,,0.8,-1,2,0,
Wspro=,,,, 1 ,,,, 0 ,,,, 0 ,,,,-1 ,-1 ,-1 , 0 , 0 , 0 , 0 , 0
Culvert=4,5.0,7.5,82.0,0.015,0.9,1.0,29,1,57.86,4995.74,57.55,4995.74,Culvert #1  ,0,10
Culvert=4,5.0,7.5,82.0,0.015,0.9,1.0,29,1,58.00,5004.24,57.70,5004.24,Culvert #2  ,0,10
BC Design=,, 0 ,, 0 ,,,,,,
BR U #Sta/Elev= 41
  4845.4   67.41  4870.4   66.96  4875.4   66.87  4880.4   66.71  4890.4    66.4
  4900.4   66.09  4910.4   65.78  4915.4   65.62  4925.4   65.31  4930.4   65.27
  4935.4   65.22  4940.4   65.08  4945.4   64.94  4950.4   64.66  4955.4   64.39
  4960.4    64.3  4970.4   64.12  4975.4   64.03  4985.4   63.78  4989.8   62.12
  4990.5   61.86    4992   57.86    5000   57.86    5008   57.86  5008.8   59.99
  5009.5   61.86  5019.2   63.91  5029.2   66.01  5039.2   68.12  5043.6   69.05
  5049.2    69.2  5053.6   69.32  5059.2   69.93  5063.6   70.41  5069.2    70.9
  5073.6   71.29  5079.2   71.73  5083.6   72.08  5089.2   72.44  5099.2   73.09
  5103.6   73.38
BR U #Mann= 3
 4845.40    0.13  4990.5   0.047  5009.5    0.13
BR U Banks=4990.50,5009.50
BR D #Sta/Elev= 41
  4845.4      67  4870.4   66.55  4875.4   66.46  4880.4    66.3  4890.4   65.99
  4900.4   65.68  4910.4   65.37  4915.4   65.21  4925.4    64.9  4930.4   64.86
  4935.4   64.81  4940.4   64.67  4945.4   64.53  4950.4   64.25  4955.4   63.98
  4960.4   63.89  4970.4   63.71  4975.4   63.62  4985.4   63.37  4989.8   61.71
  4990.5   61.45    4992   57.45    5000   57.45    5008   57.45  5008.8   59.58
  5009.5   61.45  5019.2    63.5  5029.2    65.6  5039.2   67.71  5043.6   68.64
  5049.2   68.79  5053.6   68.91  5059.2   69.52  5063.6      70  5069.2   70.49
  5073.6   70.88  5079.2   71.32  5083.6   71.67  5089.2   72.03  5099.2   72.68
  5103.6   72.97
BR D #Mann= 3
 4845.40    0.13  4990.5   0.047  5009.5    0.13
BR D Banks=4990.50,5009.50

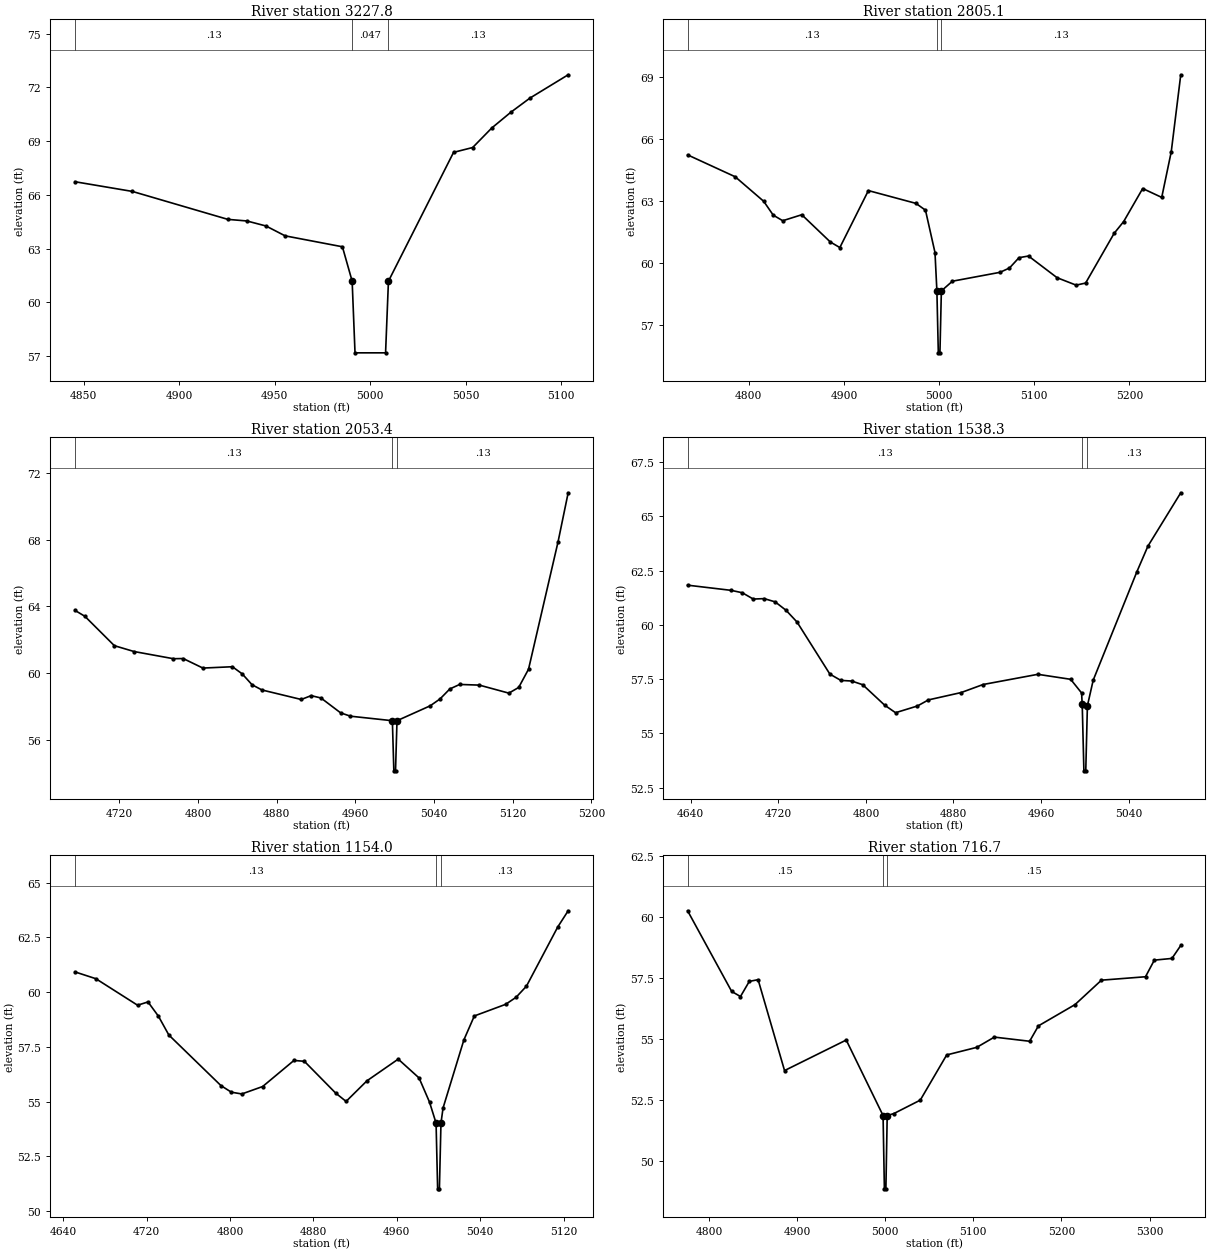
Type RM Length L Ch R = 1 ,3227.8,422.7,422.7,422.7
XS GIS Cut Line= 4
   .642286131631   .159645521318   .665403532755   .102097948307
   .669338409543   .087588090155   .673299088761   .061634352349
BEGIN DESCRIPTION:
Downstream Section of Bridge/Culvert/Weir
END DESCRIPTION:
#Sta/Elev= 17
  4845.4   66.74  4875.4    66.2  4925.4   64.64  4935.4   64.55  4945.4   64.27
  4955.4   63.72  4985.4   63.11  4990.5   61.19    4992   57.19    5008   57.19
  5009.5   61.19  5043.6   68.38  5053.6   68.65  5063.6   69.74  5073.6   70.62
  5083.6   71.41  5103.6   72.71
#Mann= 3 , 1 , 0
 4845.40    0.13       0  4990.5   0.047       0  5009.5    0.13       0
#XS Ineff= 2 , 0
       0    4980      63    5020       0      63
Bank Sta=4990.50,5009.50
Exp/Cntr=0.5,0.3

Type RM Length L Ch R = 1 ,2805.1,751.7,751.7,751.7
XS GIS Cut Line= 3
   .682485700439   .140430647804   .715426150436   .086312179845
   .729551944033   .050000000000
BEGIN DESCRIPTION:
Reeders Fork 4.0
END DESCRIPTION:
#Sta/Elev= 30
  4735.7   65.25  4785.7   64.19  4815.7      63  4825.7   62.33  4835.7   62.06
  4855.7   62.35  4885.7   61.03  4895.7   60.76  4925.7   63.52  4975.7    62.9
  4985.7   62.57  4995.7   60.52  4997.7   58.66  4999.2   55.66  5000.9   55.66
  5002.4   58.66    5014   59.13    5064   59.56    5074   59.77    5084   60.27
    5094   60.35    5124    59.3    5144   58.94    5154   59.04    5184   61.45
    5194   62.02    5214   63.62    5234   63.19    5244    65.4    5254   69.13
#Mann= 3 , 1 , 0
 4735.70    0.13       0  4997.7   0.047       0  5002.4    0.13       0
Bank Sta=4997.70,5002.40
Exp/Cntr=0.3,0.1

Type RM Length L Ch R = 1 ,2053.4,515.1,515.1,515.1
XS GIS Cut Line= 3
   .771329845652   .189612228190   .801473394919   .138315311014
   .820511426036   .121392616688
BEGIN DESCRIPTION:
Reeders Fork 3.0
END DESCRIPTION:
#Sta/Elev= 30
  4675.1   63.76  4685.1   63.41  4715.1   61.65  4735.1    61.3  4775.1   60.87
  4785.1   60.88  4805.1   60.31  4835.1   60.39  4845.1   59.96  4855.1   59.31
  4865.1      59  4905.1   58.43  4915.1   58.66  4925.1   58.52  4945.1   57.63
  4955.1   57.43  4997.7   57.16  4999.2   54.16  5000.9   54.16  5002.4   57.16
  5036.1   58.05  5046.1   58.46  5056.1   59.06  5066.1   59.33  5086.1   59.29
  5116.1   58.81  5126.1   59.15  5136.1   60.24  5166.1   67.86  5176.4    70.8
#Mann= 3 , 1 , 0
 4675.10    0.13       0  4997.7   0.047       0  5002.4    0.13       0
Bank Sta=4997.70,5002.40
Exp/Cntr=0.3,0.1

Type RM Length L Ch R = 1 ,1538.3,384.3,384.3,384.3
XS GIS Cut Line= 3
   .830030441595   .225572953634   .865462332840   .156295673735
   .873923680004   .134613471630
BEGIN DESCRIPTION:
Reeders Fork 2.0
END DESCRIPTION:
#Sta/Elev= 30
  4637.1   61.83  4677.1   61.59  4687.1   61.48  4697.1   61.19  4707.1   61.21
  4717.1   61.06  4727.1   60.67  4737.1   60.13  4767.1   57.73  4777.1   57.44
  4787.1   57.41  4797.1   57.24  4817.1    56.3  4827.1   55.95  4847.1   56.26
  4857.1   56.54  4887.1   56.88  4907.1   57.25  4957.1   57.72  4987.1   57.49
  4997.1   56.86  4997.6   56.37  4997.7   56.27  4999.2   53.27  5000.9   53.27
  5002.4   56.27  5007.7   57.45  5047.7   62.46  5057.7   63.63  5087.7   66.09
#Mann= 3 , 1 , 0
 4637.10    0.13       0  4997.6   0.047       0  5002.4    0.13       0
Bank Sta=4997.60,5002.40
Exp/Cntr=0.3,0.1

Type RM Length L Ch R = 1 ,1154.0,437.3,437.3,437.3
XS GIS Cut Line= 3
   .886086866550   .228217124622   .912528576435   .165285855096
   .901951892480   .142017150397
BEGIN DESCRIPTION:
Reeders Fork 1.0
END DESCRIPTION:
#Sta/Elev= 30
  4651.3   60.92  4671.3   60.61  4711.3    59.4  4721.3   59.55  4731.3    58.9
  4741.3   58.04  4791.3   55.73  4801.3   55.43  4811.3   55.35  4831.3   55.69
  4861.3   56.88  4871.3   56.84  4901.3   55.39  4911.3   55.01  4931.3   55.95
  4961.3   56.94  4981.3   56.08  4991.3   54.98  4997.6   54.02  4999.1   51.02
  5000.8   51.02  5002.3   54.02  5004.3   54.71  5024.3   57.82  5034.3   58.91
  5064.3   59.44  5074.3   59.76  5084.3   60.27  5114.3   62.97  5124.3   63.71
#Mann= 3 , 1 , 0
 4651.30    0.13       0  4997.6   0.047       0  5002.3    0.13       0
Bank Sta=4997.60,5002.30
Exp/Cntr=0.3,0.1

Type RM Length L Ch R = 1 ,716.7,0,0,0
XS GIS Cut Line= 5
   .911643516721   .241313157607   .946211705355   .190644716733
   .950000000000   .176438611815   .941476337049   .163179580557
   .910222906229   .141396886350
BEGIN DESCRIPTION:
Reeders Fork 0.5
END DESCRIPTION:
#Sta/Elev= 24
  4775.8   60.25  4825.8   56.95  4835.8   56.74  4845.8   57.36  4855.8   57.43
  4885.8   53.71  4955.8   54.96  4997.6   51.87  4999.1   48.87  5000.8   48.87
  5002.3   51.87  5009.8   51.95  5039.8    52.5  5069.8   54.35  5103.9   54.66
  5123.9   55.08  5163.9   54.91  5173.9   55.54  5215.4   56.41  5245.4   57.41
  5295.4   57.55  5305.4   58.23  5325.4    58.3  5335.4   58.83
#Mann= 3 , 1 , 0
 4775.80    0.15       0  4997.6    0.05       0  5002.3    0.15       0
Bank Sta=4997.60,5002.30
Exp/Cntr=0.3,0.1

Chan Stop Cuts=-1