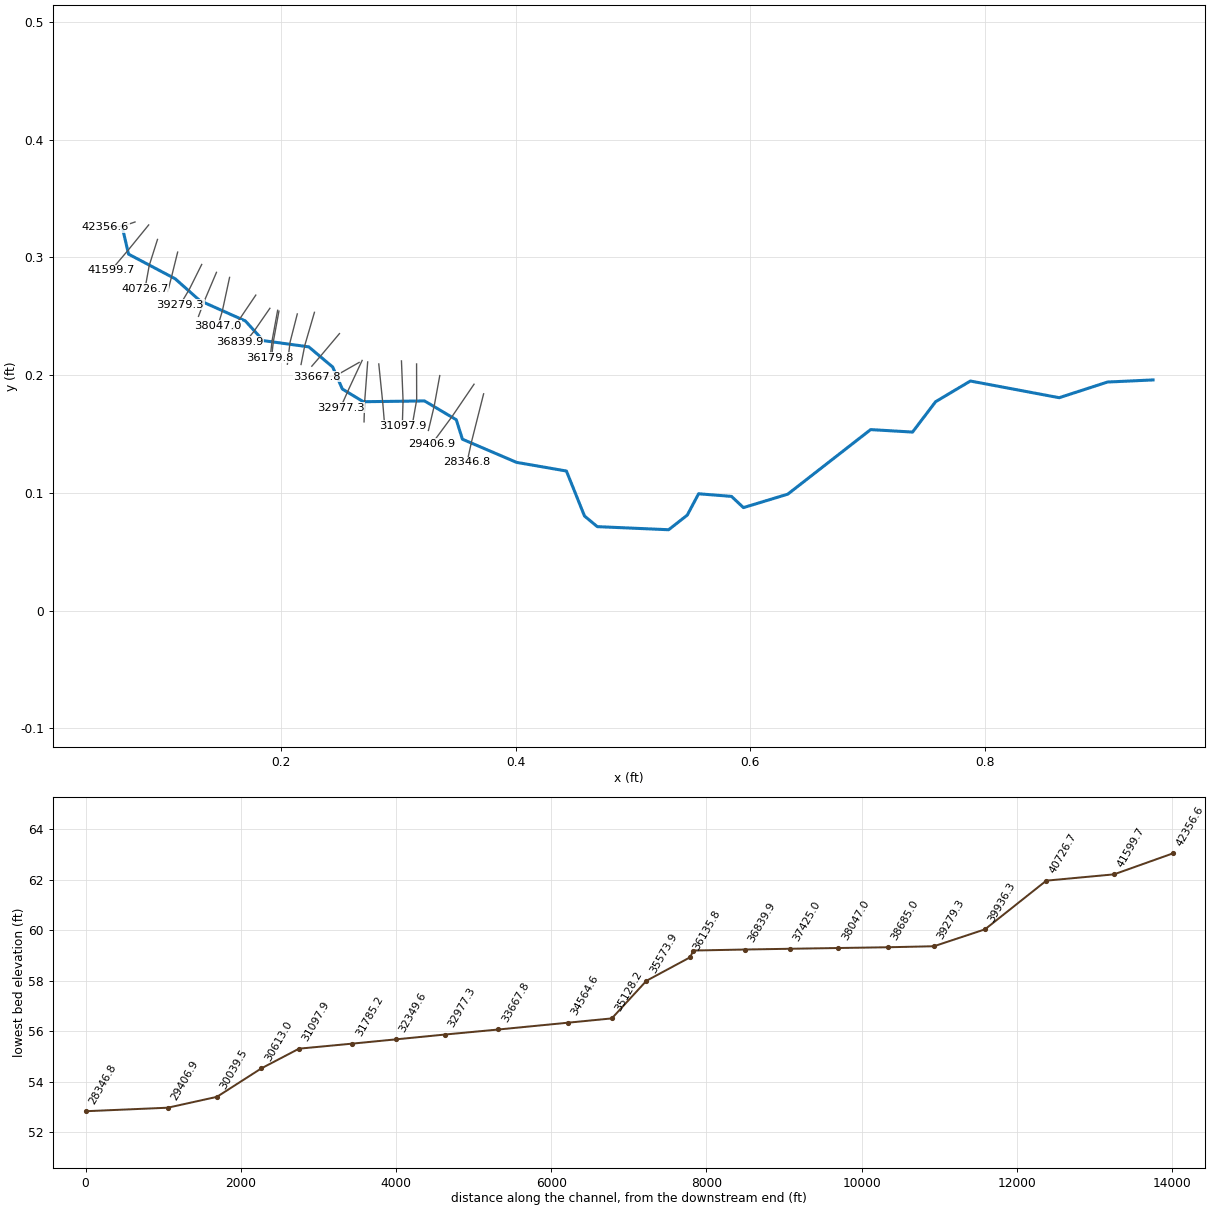
--- Sandy_Run_FINAL.prj (project) ---

Proj Title=Sandy Run
Current Plan=p02
Default Exp/Contr=0.3,0.1
English Units
Geom File=g01
Flow File=f02
Flow File=f01
Plan File=p02
Plan File=p01
Y Axis Title=Elevation
X Axis Title(PF)=Main Channel Distance
X Axis Title(XS)=Station
BEGIN DESCRIPTION:
####(Watershed Name)####
SANDY RUN
HCFCD Unit X###-##-##
(Flood Hazard, Floodway) Model
10, 2, 1, 0.2% Event
Filename:  n:\NC_flood\60138\Approximates\URS\L_Contentnea_Pitt\ENG\Sandy Run\Sandy Run.prj
Prepared by:  ________     Date: ________
Reviewed by:  ________     Date: ________
STATUS (Draft RAS, SVSQ, FINAL)
END DESCRIPTION:
DSS Export Rating Curves= 0
DSS Export Rating Curve Sorted= 0
DSS Export Volume Flow Curves= 0
DXF OffsetX= 0
DXF OffsetY= 0
DXF ScaleX= 1
DXF ScaleY= 10

--- Sandy_Run_FINAL.p02 (plan) ---

Plan Title=Multi_Profile
Program Version=3.13
Short Identifier=Multi_Pro
Geom File=g01
Flow File=f02
Subcritical Flow
K Sum by GR= 0
Std Step Tol= 0.01
Critical Tol= 0.01
Num of Std Step Trials= 20
Max Error Tol= 0.3
Flow Tol Ratio= 0.001
Split Flow NTrial= 30
Split Flow Tol= 0.02
Split Flow Ratio= 0.02
Log Output Level= 0
Friction Slope Method= 1
Unsteady Friction Slope Method= 2
Unsteady Bridges Friction Slope Method= 1
Parabolic Critical Depth
Global Vel Dist= 0 , 0 , 0
Global Log Level= 0
CheckData=True
Encroach Param=-1 ,0,0, 2
Computation Interval=1HOUR
Output Interval=1HOUR
Run HTab= 0
Run UNet= 0
Run PostProcess= 0
UNET Theta= 1
UNET Theta Warmup= 1
UNET ZTol= 0.02
UNET ZSATol= 0.1
UNET MxIter= 20
UNET MaxInSteps= 20
UNET DtIC= 0
UNET DtMin= 0
UNET MaxCRTS= 20
UNET WFStab= 2
UNET SFStab= 1
UNET WFX= 1
UNET SFX= 1
UNET DSS MLevel= 4
UNET DZMax Abort= 100
UNET Convert EG Bridges=-1
UNET Use Existing IB Tables=-1
UNET Froude Reduction=False
UNET Froude Limit= 1
UNET Froude Power= 10
Instantaneous Interval=1HOUR
Write IC File= 0
Echo Input=False
Echo Output=False
Write Detailed= 0
Detailed Automatic Start=False, 10

--- Sandy_Run_FINAL.p01 (plan) ---

Plan Title=100 Year FW
Version=Version 3.0.1  Mar 2001
Short Identifier=fw
Geom File=g01
Flow File=f01
Subcritical Flow
K Sum by GR= 0
Std Step Tol= 0.01
Critical Tol= 0.01
Num of Std Step Trials= 20
Max Error Tol= 0.3
Flow Tol Ratio= 0.001
Split Flow NTrial= 30
Split Flow Tol= 0.02
Split Flow Ratio= 0.02
Log Output Level= 0
Friction Slope Method= 1
Unsteady Friction Slope Method= 2
Parabolic Critical Depth
Global Vel Dist= 0 , 0 , 0
Global Log Level= 0
CheckData=True
Encroach Param=-1 ,0,0, 2
Encroach River=Sandy Run
Encroach Reach=Reach - 1
Encroach Node=42356.6
       1 4990.36 5074.01
Encroach Node=41599.7
       1    4880    5280
Encroach Node=40726.7
       1 4706.57  5177.3
Encroach Node=39936.3
       1 4856.78 5224.14
Encroach Node=39279.3
       1 4760.23 5079.46
Encroach Node=38685.0
       1 4748.48 5158.02
Encroach Node=38047.0
       1 4768.91 5184.87
Encroach Node=37425.0
       1    4880    5100
Encroach Node=36839.9
       1    4850    5150
Encroach Node=36179.8
       1    4946    5053
Encroach Node=36157.8
       1    4946    5053
Encroach Node=36135.8
       1    4946    5053
Encroach Node=35573.9
       1    4900    5160
Encroach Node=35128.2
       1 4755.96  5183.9
Encroach Node=34564.6
       1  4750.1 5066.13
Encroach Node=33667.8
       1 4824.81 5207.82
Encroach Node=32977.3
       1 4815.75 5129.49
Encroach Node=32349.6
       1 4815.02 5139.63
Encroach Node=31785.2
       1  4681.9  5147.1
Encroach Node=31097.9
       1 4752.99 5187.15
Encroach Node=30613.0
       1 4868.37 5175.04
Encroach Node=30039.5
       1 4659.14    5120
Encroach Node=29406.9
       1    4800    5050
Encroach Node=28346.8
       1 4664.25 5160.63
Encroach Node=27597.1
       1  4899.7 5357.69
Encroach Node=27061.0
       1 4908.52 5367.17
Encroach Node=26385.0
       1  4791.1 5246.06
Encroach Node=25895.7
       1 4296.03 5039.32
Encroach Node=25217.4
       1    4700    5210
Encroach Node=24455.6
       1    4950    5380
Encroach Node=23415.9
       1    4520    5200
Encroach Node=22563.6
       1    4780    5150
Encroach Node=22001.0
       1    4974    5026
Encroach Node=21972.0
       1    4974    5026
Encroach Node=21943.0
       1    4600    5026
Encroach Node=21255.4
       1    4550    5130
Encroach Node=20521.0
       1    4580    5065
Encroach Node=19542.3
       1  4800.4 5345.37
Encroach Node=18611.5
       1 4669.48 5435.36
Encroach Node=17869.2
       1 4515.14 5198.59
Encroach Node=17049.2
       1  4884.6 5331.04
Encroach Node=16500.0
       1 4789.82 5215.58
Encroach Node=15754.5
       1 4593.97 5285.21
Encroach Node=14900.4
       1    4550    5090
Encroach Node=14480.4
       1    4730    5077
Encroach Node=13764.9
       1    4600    5130
Encroach Node=13000.0
       1 4800.87 5456.38
Encroach Node=12351.9
       1 4790.63 5173.87
Encroach Node=11620.0
       1 4446.44 5141.11
Encroach Node=10646.2
       1  4574.5 5066.87
Encroach Node=9788.2
       1 4804.87 5049.94
Encroach Node=8588.5
       1  4603.6 5143.18
Encroach Node=7481.1
       1 4740.71 5200.29
Encroach Node=6628.4
       1    4750    5080
Encroach Node=5881.5
       1 4820.18 5044.82
Encroach Node=5139.5
       1 4561.49    5060
Encroach Node=4361.9
       1    4850    5090
Encroach Node=3538.9
       1    4970    5030
Computation Interval=1HOUR
Output Interval=1HOUR
Run HTab= 0
Run UNet= 0
Run PostProcess= 0
UNET Theta= 1
UNET ZTol= 0.02
UNET ZSATol= 0.1
UNET MxIter= 20
UNET MaxInSteps= 20
UNET DtIC= 0
UNET DtMin= 0
UNET MaxCRTS= 20
UNET WFStab= 2
UNET SFStab= 1
UNET WFX= 1
UNET SFX= 1
UNET Convert EG Bridges=-1
UNET Use Existing IB Tables=-1
Instantaneous Interval=1HOUR
Write IC File= 0
Write Velocity= 0
Write Detailed= 0

--- Sandy_Run_FINAL.f02 (steady flow) ---

Flow Title=Multi_Profile
Program Version=3.13
Number of Profiles= 7
Profile Names=10-yr,25-yr,50-yr,500-yr,100-yr-10%,100-yr-20%,100-yr-35%
River Rch & RM=Sandy Run,Reach - 1       ,42356.6
     280     412     533    1094    1178    1510    1844
River Rch & RM=Sandy Run,Reach - 1       ,40726.7
     587     842    1072    2096    2278    2920    3568
River Rch & RM=Sandy Run,Reach - 1       ,39936.3
     710    1012    1282    2477    2699    3459    4226
River Rch & RM=Sandy Run,Reach - 1       ,36839.9
     718    1023    1296    2502    2727    3495    4270
River Rch & RM=Sandy Run,Reach - 1       ,34564.6
     753    1072    1356    2609    2845    3647    4456
River Rch & RM=Sandy Run,Reach - 1       ,28346.8
     790    1122    1418    2721    2968    3804    4648
River Rch & RM=Sandy Run,Reach - 1       ,27597.1
     960    1354    1704    3228    3530    4525    5528
River Rch & RM=Sandy Run,Reach - 1       ,22563.6
    1021    1437    1806    3407    3730    4780    5841
River Rch & RM=Sandy Run,Reach - 1       ,18611.5
    1186    1659    2078    3882    4258    5458    6668
River Rch & RM=Sandy Run,Reach - 1       ,17869.2
    1324    1846    2306    4277    4698    6022    7357
River Rch & RM=Sandy Run,Reach - 1       ,16500
    1380    1920    2397    4434    4873    6246    7631
River Rch & RM=Sandy Run,Reach - 1       ,8588.5
    1405    1954    2438    4506    4953    6348    7756
River Rch & RM=Sandy Run,Reach - 1       ,6628.4
    1536    2129    2651    4871    5360    6870    8394
Boundary for River Rch & Prof#=Sandy Run,Reach - 1       , 1
Up Type= 0
Dn Type= 3
Dn Slope=0.000122
Boundary for River Rch & Prof#=Sandy Run,Reach - 1       , 2
Up Type= 0
Dn Type= 3
Dn Slope=0.000122
Boundary for River Rch & Prof#=Sandy Run,Reach - 1       , 3
Up Type= 0
Dn Type= 3
Dn Slope=0.000122
Boundary for River Rch & Prof#=Sandy Run,Reach - 1       , 4
Up Type= 0
Dn Type= 3
Dn Slope=0.000122
Boundary for River Rch & Prof#=Sandy Run,Reach - 1       , 5
Up Type= 0
Dn Type= 3
Dn Slope=0.000122
Boundary for River Rch & Prof#=Sandy Run,Reach - 1       , 6
Up Type= 0
Dn Type= 3
Dn Slope=0.000122
Boundary for River Rch & Prof#=Sandy Run,Reach - 1       , 7
Up Type= 0
Dn Type= 3
Dn Slope=0.000122
DSS Import GetInterval= 0
DSS Import GetPeak= 0
DSS Import FillOption= 0

--- Sandy_Run_FINAL.f01 (steady flow) ---

Flow Title= 100 Year FW
Version=Version 3.0.1  Mar 2001
Number of Profiles= 2
Profile Names=100-Year,100-Year FW
River Rch & RM=Sandy Run,Reach - 1       ,42356.6
     674     674
River Rch & RM=Sandy Run,Reach - 1       ,40726.7
    1334    1334
River Rch & RM=Sandy Run,Reach - 1       ,39936.3
    1590    1590
River Rch & RM=Sandy Run,Reach - 1       ,36839.9
    1607    1607
River Rch & RM=Sandy Run,Reach - 1       ,34564.6
    1679    1679
River Rch & RM=Sandy Run,Reach - 1       ,28346.8
    1754    1754
River Rch & RM=Sandy Run,Reach - 1       ,27597.1
    2099    2099
River Rch & RM=Sandy Run,Reach - 1       ,22563.6
    2222    2222
River Rch & RM=Sandy Run,Reach - 1       ,18611.5
    2548    2548
River Rch & RM=Sandy Run,Reach - 1       ,17869.2
    2821    2821
River Rch & RM=Sandy Run,Reach - 1       ,16500
    2930    2930
River Rch & RM=Sandy Run,Reach - 1       ,8588.5
    2980    2980
River Rch & RM=Sandy Run,Reach - 1       ,6628.4
    3234    3234
Boundary for River Rch & Prof#=Sandy Run,Reach - 1       , 1
Up Type= 0
Dn Type= 1
Dn Known WS=43.8
Boundary for River Rch & Prof#=Sandy Run,Reach - 1       , 2
Up Type= 0
Dn Type= 1
Dn Known WS=44.5
DSS Import GetInterval= 0
DSS Import GetPeak= 0
DSS Import FillOption= 0

--- Sandy_Run_FINAL.g01 (geometry) ---

Geom Title=Geom 01 by CodeH2 for Windows

River Reach=Sandy Run,Reach - 1
Reach XY= 30
   .064307450544   .326490521215   .069806418034   .302851202983
   .109589627559   .281923938969   .130653448918   .263355121674
   .169432753246   .246128025017   .184706006496   .229409589561
   .223529438525   .224088623675   .243959371423   .206943222896
   .252170701721   .188287044680   .270038842683   .177513624286
   .322263380433   .178170471078   .349327972800   .162207573421
   .354583343455   .145653424203   .400698579905   .126011826719
   .443266605152   .118654427067   .458703846480   .080421948438
   .469608755496   .071422282726   .530438791252   .068794597399
   .546336093678   .081210283852   .555992606182   .099341103899
   .584042617817   .097107586279   .594224786650   .087582562397
   .632063097571   .099012829583   .702713932069   .153831956885
   .738449915832   .151729927887   .758118049568   .177514518767
   .787784089170   .195093444391   .863503646074   .180914140701
   .904704905232   .194221624138   .943553970165   .196018451371

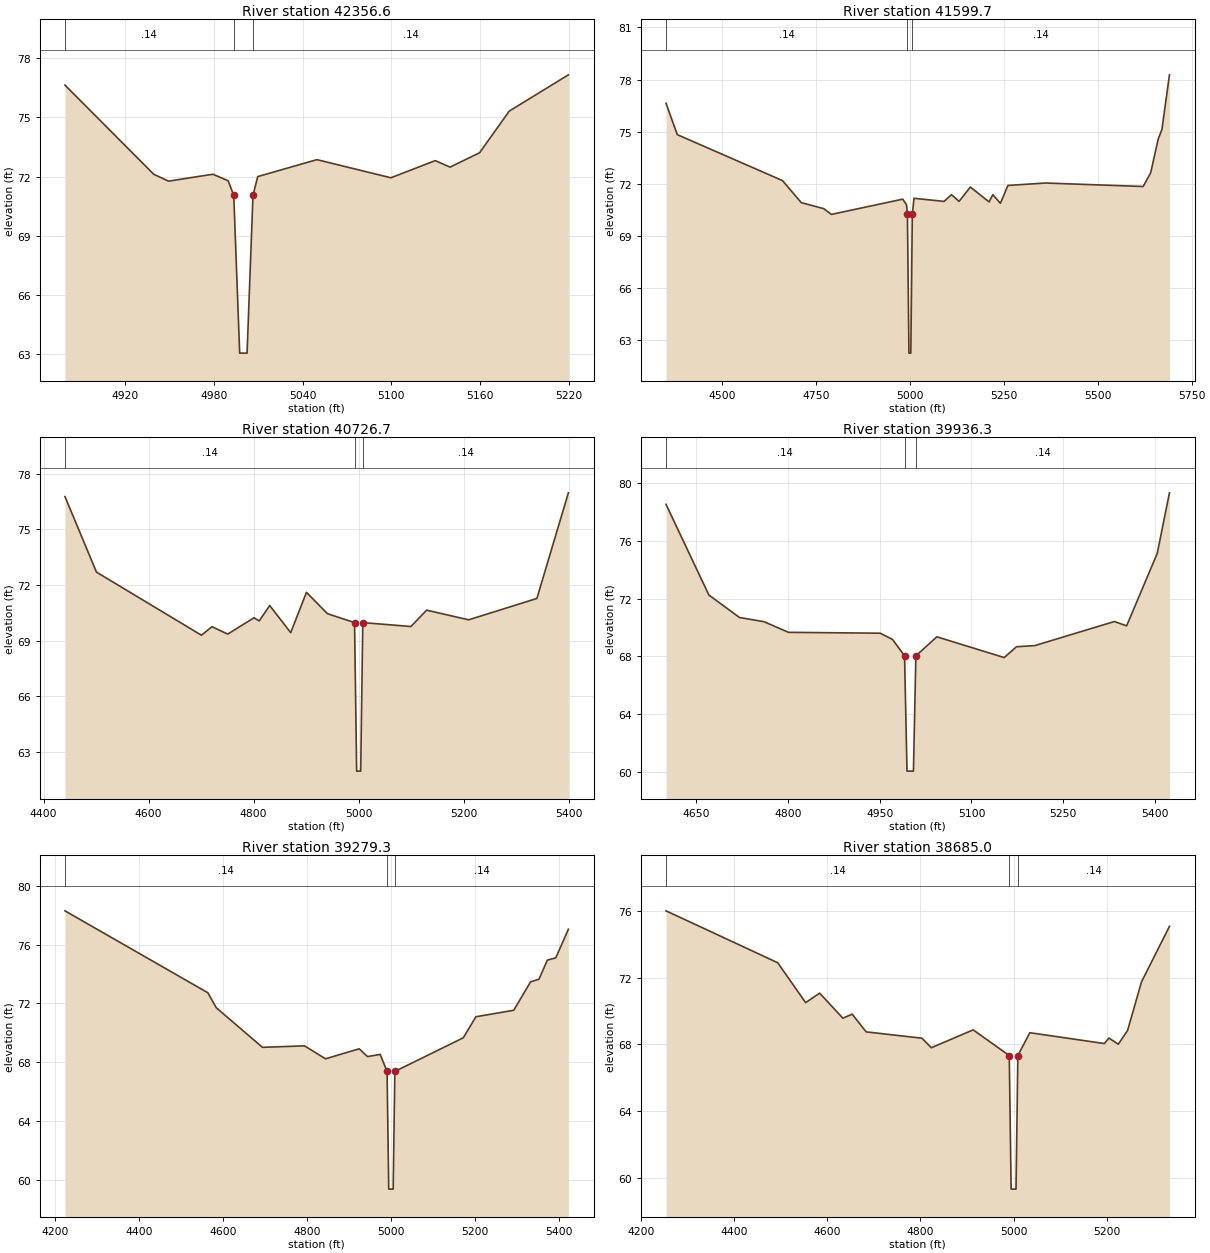
Type RM Length L Ch R = 1 ,42356.6,756.9,756.9,756.9
XS GIS Cut Line= 3
   .075349305619   .330158301079   .064615815853   .326504347116
   .050000000000   .325819230748
BEGIN DESCRIPTION:
Sandy Run 53.0
END DESCRIPTION:
#Sta/Elev= 17
  4879.4   76.64  4939.4   72.12  4949.4   71.77  4979.4   72.12  4989.7   71.79
  4993.5   71.05  4997.5   63.05  5002.5   63.05  5006.5   71.05  5009.7      72
  5049.7   72.86  5099.7   71.94  5129.7   72.81  5139.7   72.48  5159.7   73.21
  5179.7   75.32  5219.7   77.16
#Mann= 3 , 1 , 0
 4879.40    0.14       0  4993.5   0.045       0  5006.5    0.14       0
Bank Sta=4993.50,5006.50
Exp/Cntr=0.3,0.1

Type RM Length L Ch R = 1 ,41599.7,873,873,873
XS GIS Cut Line= 3
   .086996283877   .327646207729   .069640002552   .306407600318
   .055024186699   .289279691116
BEGIN DESCRIPTION:
Sandy Run 52.0
END DESCRIPTION:
#Sta/Elev= 27
    4351   76.63    4381   74.82    4661   72.17    4711    70.9    4771   70.55
    4791   70.22    4981    71.1    4991   70.78  4993.5   70.22  4997.5   62.22
  5002.5   62.22  5006.5   70.22  5010.9   71.15  5090.9   70.97  5110.9   71.36
  5130.9   70.97  5160.9    71.8  5210.9   70.94  5220.9   71.36  5240.9   70.86
  5260.9   71.89  5360.9   72.03  5620.9   71.83  5640.9   72.62  5660.9   74.56
  5670.9   75.12  5690.9   78.27
#Mann= 3 , 1 , 0
 4351.00    0.14       0  4993.5   0.045       0  5006.5    0.14       0
Bank Sta=4993.50,5006.50
Exp/Cntr=0.3,0.1

Type RM Length L Ch R = 1 ,40726.7,790.4,790.4,790.4
XS GIS Cut Line= 3
   .094514155069   .315328177413   .087456947727   .293202030468
   .083829978455   .273374598450
BEGIN DESCRIPTION:
Sandy Run 51.0
END DESCRIPTION:
#Sta/Elev= 20
  4440.6   76.76  4500.6   72.69  4700.6   69.29  4720.6   69.75  4750.6   69.35
  4800.6   70.23  4810.6   70.06  4830.6   70.89  4870.6   69.43  4900.6    71.6
  4940.6   70.45  4992.2   69.97  4996.2   61.97  5003.9   61.97  5007.9   69.97
  5099.5   69.76  5129.5   70.64  5209.5   70.12  5339.5   71.27  5399.5   76.96
#Mann= 3 , 1 , 0
 4440.60    0.14       0  4992.2   0.045       0  5007.9    0.14       0
Bank Sta=4992.20,5007.90
Exp/Cntr=0.3,0.1

Type RM Length L Ch R = 1 ,39936.3,657,657,657
XS GIS Cut Line= 3
   .111709250282   .304581242905   .106435217258   .283386333356
   .103263324861   .271121682758
BEGIN DESCRIPTION:
Sandy Run 50.0
END DESCRIPTION:
#Sta/Elev= 19
    4601   78.55    4671   72.26    4721    70.7    4761   70.41    4801   69.67
    4951   69.61    4971   69.18  4990.7   68.04  4994.7   60.04  5005.2   60.04
  5009.2   68.04  5043.5   69.36  5153.5   67.92  5173.5   68.67  5203.5   68.75
  5333.5   70.42  5353.5   70.12  5403.5   75.14  5423.5   79.35
#Mann= 3 , 1 , 0
 4601.00    0.14       0  4990.7   0.045       0  5009.2    0.14       0
Bank Sta=4990.70,5009.20
Exp/Cntr=0.3,0.1

Type RM Length L Ch R = 1 ,39279.3,594.3,594.3,594.3
XS GIS Cut Line= 3
   .132213964170   .294075505693   .121708846526   .273065270405
   .113944194355   .260048059411
BEGIN DESCRIPTION:
Sandy Run 49.0
END DESCRIPTION:
#Sta/Elev= 21
  4224.3   78.29  4564.3   72.72  4584.3    71.7  4694.3   69.01  4794.3   69.11
  4844.3   68.23  4924.3   68.91  4944.3   68.38  4974.3   68.53  4990.7   67.37
  4994.7   59.37  5005.2   59.37  5009.2   67.37  5172.1   69.66  5202.1   71.09
  5292.1   71.53  5332.1   73.46  5352.1   73.64  5372.1   74.94  5392.1   75.09
  5422.1   77.04
#Mann= 3 , 1 , 0
 4224.30    0.14       0  4990.7   0.045       0  5009.2    0.14       0
Bank Sta=4990.70,5009.20
Exp/Cntr=0.3,0.1

Type RM Length L Ch R = 1 ,38685.0,638,638,638
XS GIS Cut Line= 3
   .144809808566   .287386147692   .134040941152   .262103408516
   .129473498698   .249999686013
BEGIN DESCRIPTION:
Sandy Run 48.0
END DESCRIPTION:
#Sta/Elev= 21
  4253.3      76  4493.3   72.89  4553.3    70.5  4583.3   71.07  4633.3   69.57
  4653.3   69.81  4683.3   68.75  4803.3   68.37  4823.3    67.8  4913.3   68.87
  4990.8   67.33  4994.8   59.33  5005.3   59.33  5009.3   67.33    5035    68.7
    5195   68.05    5205   68.38    5225   68.01    5245   68.83    5275   71.75
    5335   75.07
#Mann= 3 , 1 , 0
 4253.30    0.14       0  4990.8   0.045       0  5009.3    0.14       0
Bank Sta=4990.80,5009.30
Exp/Cntr=0.3,0.1

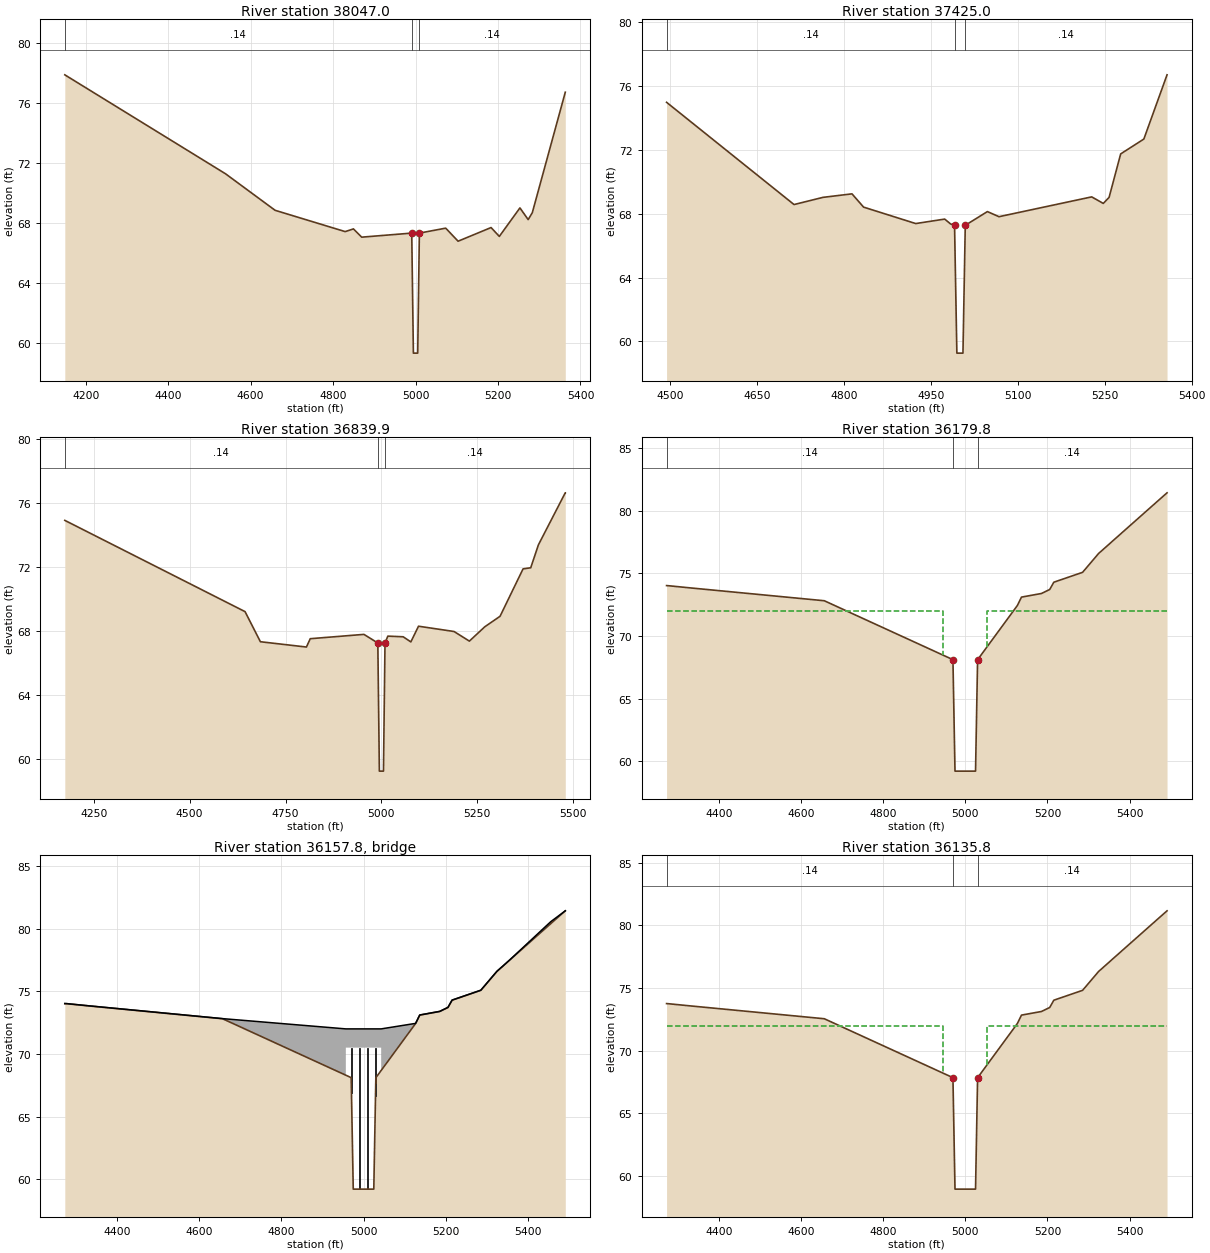
Type RM Length L Ch R = 1 ,38047.0,622,622,622
XS GIS Cut Line= 3
   .155986620454   .283087373890   .149784413337   .254416382805
   .145978142462   .241940272714
BEGIN DESCRIPTION:
Sandy Run 47.0
END DESCRIPTION:
#Sta/Elev= 18
  4149.4   77.85  4539.4   71.25  4659.4   68.82  4829.4    67.4  4849.4   67.58
  4869.4   67.03  4990.8    67.3  4994.8    59.3  5005.3    59.3  5009.3    67.3
  5073.2   67.63  5103.2   66.76  5183.2   67.67  5203.2   67.08  5253.2   68.98
  5273.2    68.2  5283.2   68.66  5363.2   76.69
#Mann= 3 , 1 , 0
 4149.40    0.14       0  4990.8   0.045       0  5009.3    0.14       0
Bank Sta=4990.80,5009.30
Exp/Cntr=0.3,0.1

Type RM Length L Ch R = 1 ,37425.0,585.1,585.1,585.1
XS GIS Cut Line= 3
   .178340244230   .268041665578   .165220956332   .248706976492
   .158242793060   .238768380318
BEGIN DESCRIPTION:
Sandy Run 46.0
END DESCRIPTION:
#Sta/Elev= 20
  4493.8   74.97  4713.8   68.57  4763.8   69.02  4813.8   69.24  4833.8   68.41
  4923.8   67.38  4973.8   67.66  4983.8   67.36  4990.8   67.27  4994.8   59.27
  5005.3   59.27  5009.3   67.27  5047.5   68.13  5067.5   67.81  5227.5   69.05
  5247.5   68.64  5257.5   69.02  5277.5   71.74  5317.5   72.67  5357.5   76.69
#Mann= 3 , 1 , 0
 4493.80    0.14       0  4990.8   0.045       0  5009.3    0.14       0
Bank Sta=4990.80,5009.30
Exp/Cntr=0.3,0.1

Type RM Length L Ch R = 1 ,36839.9,660.1,660.1,660.1
XS GIS Cut Line= 4
   .190376810879   .256864853690   .176377351271   .236737140722
   .172732663046   .232300128970   .165009496839   .228406865157
BEGIN DESCRIPTION:
Sandy Run 45.0
END DESCRIPTION:
#Sta/Elev= 23
  4174.4    74.9  4644.4    69.2  4684.4   67.32  4804.4   66.99  4814.4   67.51
  4954.4   67.78  4990.6   67.24  4994.6   59.24  5005.3   59.24  5009.3   67.24
  5016.7   67.67  5056.7   67.63  5076.7   67.31  5096.7   68.29  5189.3   67.96
  5229.3   67.36  5269.3   68.25  5309.3   68.91  5369.3   71.87  5389.3   71.94
  5409.3   73.37  5479.3   76.62  5479.4   76.62
#Mann= 3 , 1 , 0
 4174.40    0.14       0  4990.6   0.045       0  5009.3    0.14       0
Bank Sta=4990.60,5009.30
Exp/Cntr=0.5,0.3

Type RM Length L Ch R = 1 ,36179.8,44,44,44
XS GIS Cut Line= 3
   .196982478921   .255159166853   .192186664344   .229124744866
   .190588059485   .214737301136
BEGIN DESCRIPTION:
Upstream Section of Bridge/Culvert/Weir
END DESCRIPTION:
#Sta/Elev= 26
  4273.1   74.02  4277.6   74.01  4329.6   73.84  4656.9   72.81 4956.91    68.3
    4957    68.3    4961   68.24    4970    68.1    4975    59.2    5000    59.2
    5025    59.2    5030    68.1    5039    68.5 5042.89   68.68    5043   68.68
  5126.8   72.43  5136.8    73.1  5185.5   73.39  5205.5   73.71  5215.5   74.29
  5285.5   75.08  5324.6   76.59  5338.1   76.98  5355.5   77.49  5455.5    80.4
    5491   81.43
#Mann= 3 , 1 , 0
 4273.10    0.14       0    4970   0.045       0    5030    0.14       0
#XS Ineff= 2 , 0
       0    4946      72    5053       0      72
Bank Sta=4970.00,5030.00
Exp/Cntr=0.5,0.3

Type RM Length L Ch R = 3 ,36157.8,,,
BEGIN DESCRIPTION:
Friendship Church Rd-TOR
Structure ID: Friendship Church Road SR-Bridge
Approximate Survey Structure
END DESCRIPTION:
Bridge Culvert--1,0,-1,-1, 0
Deck Dist Width WeirC Skew NumUp NumDn MinLoCord MaxHiCord MaxSubmerge Is_Ogee
10,24,2.6,,26,26,,,0.95,0,1,1,,
  4273.1  4277.6  4329.6  4656.9 4956.91    4957    4961    4970    4975    5000
    5025    5030    5039 5042.89    5043  5126.8  5136.8  5185.5  5205.5  5215.5
  5285.5  5324.6  5338.1  5355.5  5455.5    5491
   74.02   74.02   73.85   72.82      72      72      72      72      72      72
      72      72      72      72      72   72.44   73.11    73.4   73.72    74.3
   75.09    76.6   76.99    77.5   80.56   81.43
   74.02   74.01   73.84   72.81    68.3    70.5    70.5    70.5    70.5    70.5
    70.5    70.5    70.5    70.5   68.68   72.43    73.1   73.39   73.71   74.29
   75.08   76.59   76.98   77.49    80.4   81.43
  4273.1  4277.6  4329.6  4656.9 4956.91    4957    4961    4970    4975    5000
    5025    5030    5039 5042.89    5043  5126.8  5136.8  5185.5  5205.5  5215.5
  5285.5  5324.6  5338.1  5355.5  5455.5    5491
   74.02   74.02   73.85   72.82      72      72      72      72      72      72
      72      72      72      72      72   72.44   73.11    73.4   73.72    74.3
   75.09    76.6   76.99    77.5   80.56   81.43
   73.77   73.76   73.59   72.56   68.05   70.25   70.25   70.25   70.25   70.25
   70.25   70.25   70.25   70.25   68.43   72.18   72.85   73.14   73.46   74.04
   74.83   76.34   76.73   77.24   80.15   81.18
Pier Skew, UpSta & Num, DnSta & Num=,4970.7, 2 ,4970.7, 2 , 0 , 0 , 0 ,,
       1       1
   64.96    71.5
       1       1
   64.71   71.25
Pier Skew, UpSta & Num, DnSta & Num=,4990.2, 2 ,4990.2, 2 , 0 , 0 , 0 ,,
       1       1
    58.2    71.5
       1       1
   57.95   71.25
Pier Skew, UpSta & Num, DnSta & Num=,5009.7, 2 ,5009.7, 2 , 0 , 0 , 0 ,,
       1       1
    58.2    71.5
       1       1
   57.95   71.25
Pier Skew, UpSta & Num, DnSta & Num=,5029.2, 2 ,5029.2, 2 , 0 , 0 , 0 ,,
       1       1
   64.79    71.5
       1       1
   64.54   71.25
Abutment Skew #Up #Dn=, 2 , 2
 4956.80 4961.00
   70.50   68.24
 4956.80 4961.00
   70.25   67.99
Abutment Skew #Up #Dn=, 2 , 2
 5039.00 5043.09
   68.50   70.50
 5039.00 5043.09
   68.25   70.25
BR Coef= 1 , 1 , 0 ,1.25, 0 ,,,0.8,0,2,0,
Wspro=,,,, 1 ,,,, 0 ,,,, 0 ,,,,-1 ,-1 ,-1 , 0 , 0 , 0 , 0 , 0
BC Design=,, 0 ,, 0 ,,,,,,
BR U #Sta/Elev= 26
  4273.1   74.02  4277.6   74.01  4329.6   73.84  4656.9   72.81 4956.91    68.3
    4957    68.3    4961   68.24    4970    68.1    4975    59.2    5000    59.2
    5025    59.2    5030    68.1    5039    68.5 5042.89   68.68    5043   68.68
  5126.8   72.43  5136.8    73.1  5185.5   73.39  5205.5   73.71  5215.5   74.29
  5285.5   75.08  5324.6   76.59  5338.1   76.98  5355.5   77.49  5455.5    80.4
    5491   81.43
BR U #Mann= 3
 4273.10    0.14    4970   0.045    5030    0.14
BR U Banks=4970.00,5030.00
BR D #Sta/Elev= 26
  4273.1   73.77  4277.6   73.76  4329.6   73.59  4656.9   72.56 4956.91   68.05
    4957   68.05    4961   67.99    4970   67.85    4975   58.95    5000   58.95
    5025   58.95    5030   67.85    5039   68.25 5042.89   68.43    5043   68.43
  5126.8   72.18  5136.8   72.85  5185.5   73.14  5205.5   73.46  5215.5   74.04
  5285.5   74.83  5324.6   76.34  5338.1   76.73  5355.5   77.24  5455.5   80.15
    5491   81.18
BR D #Mann= 3
 4273.10    0.14    4970   0.045    5030    0.14
BR D Banks=4970.00,5030.00

Type RM Length L Ch R = 1 ,36135.8,561.9,561.9,561.9
XS GIS Cut Line= 3
   .198074303601   .254431834325   .193278489025   .228397412338
   .191679884166   .214009968608
BEGIN DESCRIPTION:
Downstream Section of Bridge/Culvert/Weir
END DESCRIPTION:
#Sta/Elev= 26
  4273.1   73.75  4277.6   73.74  4329.6   73.57  4656.9   72.54 4956.91   68.03
    4957   68.03    4961   67.97    4970   67.83    4975   58.93    5000   58.93
    5025   58.93    5030   67.83    5039   68.23 5042.89   68.41    5043   68.41
  5126.8   72.16  5136.8   72.83  5185.5   73.12  5205.5   73.44  5215.5   74.02
  5285.5   74.81  5324.6   76.32  5338.1   76.71  5355.5   77.22  5455.5   80.13
    5491   81.16
#Mann= 3 , 1 , 0
 4273.10    0.14       0    4970   0.045       0    5030    0.14       0
#XS Ineff= 2 , 0
       0    4946      72    5053       0      72
Bank Sta=4970.00,5030.00
Exp/Cntr=0.5,0.3

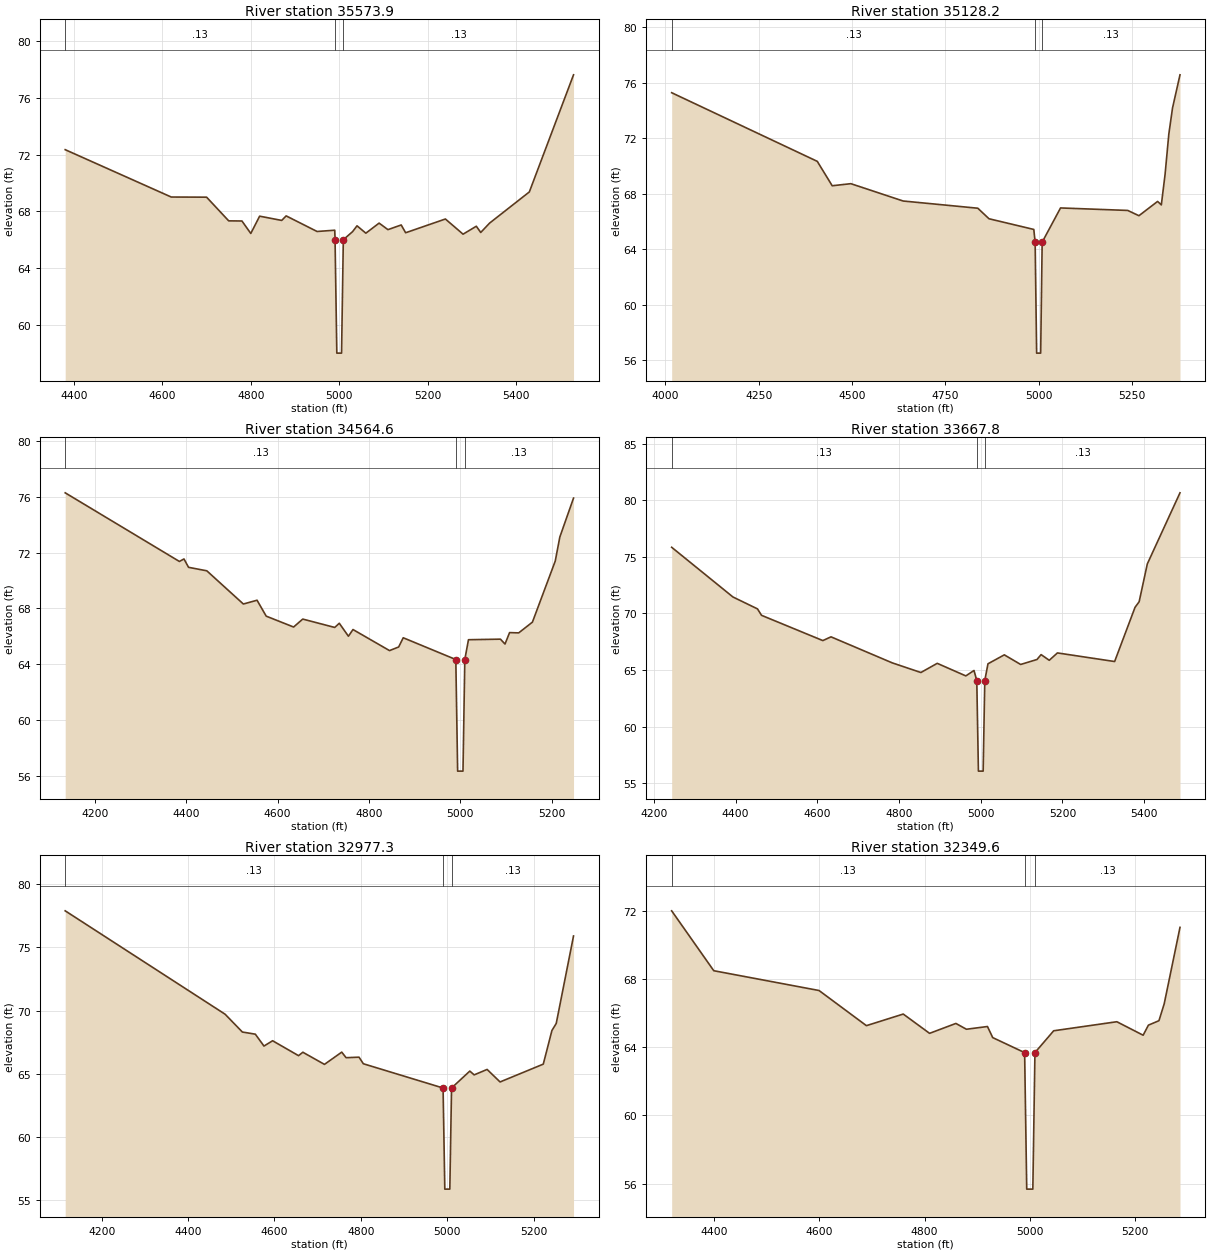
Type RM Length L Ch R = 1 ,35573.9,445.7,445.7,445.7
XS GIS Cut Line= 3
   .213742811973   .252055035117   .207576764660   .228075962234
   .205293043433   .209349448173
BEGIN DESCRIPTION:
Sandy Run 44.0
END DESCRIPTION:
#Sta/Elev= 29
    4380   72.35    4620   69.01    4700      69    4750   67.33    4780   67.32
    4800   66.44    4820   67.66    4870   67.36    4880   67.68    4950   66.58
    4990   66.67  4990.7      66  4994.7      58  5005.4      58  5009.4      66
  5030.4   66.57  5040.4   66.98  5060.4   66.46  5090.4   67.17  5110.4   66.71
  5140.4   67.04  5150.4   66.49  5240.4   67.46  5280.4   66.39  5310.4   66.95
  5320.4   66.51  5340.4   67.17  5430.4   69.37  5530.4   77.63
#Mann= 3 , 1 , 0
 4380.00    0.13       0  4990.7   0.045       0  5009.4    0.13       0
Bank Sta=4990.70,5009.40
Exp/Cntr=0.3,0.1

Type RM Length L Ch R = 1 ,35128.2,563.6,563.6,563.6
XS GIS Cut Line= 3
   .228358627825   .253425267853   .220137231408   .225335496762
   .216940021690   .209121076050
BEGIN DESCRIPTION:
Sandy Run 43.0
END DESCRIPTION:
#Sta/Elev= 21
    4017   75.29    4407   70.34    4447   68.58    4497   68.73    4637   67.48
    4837   66.96    4867    66.2    4987   65.43  4990.6   64.51  4994.6   56.51
  5005.4   56.51  5009.4   64.51  5058.6   66.98  5238.6    66.8  5268.6   66.42
  5318.6   67.45  5328.6    67.2  5338.6   69.39  5348.6   72.29  5358.6   74.19
  5378.6   76.58
#Mann= 3 , 1 , 0
 4017.00    0.13       0  4990.6   0.045       0  5009.4    0.13       0
Bank Sta=4990.60,5009.40
Exp/Cntr=0.3,0.1

Type RM Length L Ch R = 1 ,34564.6,896.8,896.8,896.8
XS GIS Cut Line= 3
   .249699889363   .235370984675   .233099453608   .215719295573
   .226121290337   .207683834836
BEGIN DESCRIPTION:
Sandy Run 42.0
END DESCRIPTION:
#Sta/Elev= 30
  4135.1   76.29  4385.1   71.37  4395.1   71.55  4405.1   70.95  4445.1    70.7
  4525.1   68.32  4555.1   68.59  4575.1   67.45  4635.1   66.67  4655.1   67.24
  4725.1   66.64  4735.1   66.94  4755.1   66.01  4765.1   66.49  4845.1   64.98
  4865.1   65.24  4875.1    65.9  4990.2   64.34  4994.2   56.34  5005.9   56.34
  5009.9   64.34  5017.9   65.76  5087.9    65.8  5097.9   65.45  5107.9   66.27
  5127.9   66.25  5157.9   67.02  5207.9    71.4  5217.9   73.12  5247.9   75.91
#Mann= 3 , 1 , 0
 4135.10    0.13       0  4990.2   0.045       0  5009.9    0.13       0
Bank Sta=4990.20,5009.90
Exp/Cntr=0.3,0.1

Type RM Length L Ch R = 1 ,33667.8,690.5,690.5,690.5
XS GIS Cut Line= 3
   .266465107195   .210867973997   .246632861165   .199648374099
   .230561939691   .198591076634
BEGIN DESCRIPTION:
Sandy Run 41.0
END DESCRIPTION:
#Sta/Elev= 27
  4243.4   75.84  4393.4   71.45  4453.4    70.4  4463.4   69.83  4613.4    67.6
  4633.4   67.93  4783.4   65.63  4853.4   64.78  4893.4   65.59  4963.4   64.48
  4983.4   64.96  4990.2   64.07  4994.2   56.07  5005.8   56.07  5009.8   64.07
  5017.6   65.55  5057.6   66.34  5097.6   65.49  5137.6   65.93  5147.6   66.36
  5167.6   65.86  5187.6   66.51  5327.6   65.75  5377.6   70.54  5387.6   71.03
  5407.6   74.37  5487.6   80.65
#Mann= 3 , 1 , 0
 4243.40    0.13       0  4990.2   0.045       0  5009.8    0.13       0
Bank Sta=4990.20,5009.80
Exp/Cntr=0.3,0.1

Type RM Length L Ch R = 1 ,32977.3,627.7,627.7,627.7
XS GIS Cut Line= 3
   .269044371477   .212587483518   .257840214298   .188652480459
   .250495661642   .172285313522
BEGIN DESCRIPTION:
Sandy Run 40.0
END DESCRIPTION:
#Sta/Elev= 25
  4115.7   77.89  4485.7   69.71  4525.7    68.3  4555.7   68.13  4575.7   67.19
  4595.7   67.61  4655.7   66.43  4665.7    66.7  4715.7   65.74  4755.7   66.71
  4765.7   66.27  4795.7   66.31  4805.7   65.79  4990.2   63.87  4994.2   55.87
  5005.8   55.87  5009.8   63.87  5052.1   65.21  5062.1   64.91  5092.1   65.34
  5122.1   64.35  5222.1   65.76  5242.1   68.42  5252.1   68.98  5292.1    75.9
#Mann= 3 , 1 , 0
 4115.70    0.13       0  4990.2   0.045       0  5009.8    0.13       0
Bank Sta=4990.20,5009.80
Exp/Cntr=0.3,0.1

Type RM Length L Ch R = 1 ,32349.6,564.4,564.4,564.4
XS GIS Cut Line= 3
   .273773022660   .211297851377   .271162162361   .177233667833
   .270673212510   .160405073291
BEGIN DESCRIPTION:
Sandy Run 39.0
END DESCRIPTION:
#Sta/Elev= 21
  4319.6   71.99  4399.6   68.48  4599.6   67.32  4689.6   65.26  4759.6   65.94
  4809.6   64.81  4859.6   65.39  4879.6   65.05  4919.6   65.21  4929.6   64.56
  4990.2   63.68  4994.2   55.68  5005.8   55.68  5009.8   63.68  5045.4   64.96
  5165.4   65.49  5215.4    64.7  5225.4   65.29  5245.4   65.55  5255.4   66.54
  5285.4   71.02
#Mann= 3 , 1 , 0
 4319.60    0.13       0  4990.2   0.045       0  5009.8    0.13       0
Bank Sta=4990.20,5009.80
Exp/Cntr=0.3,0.1

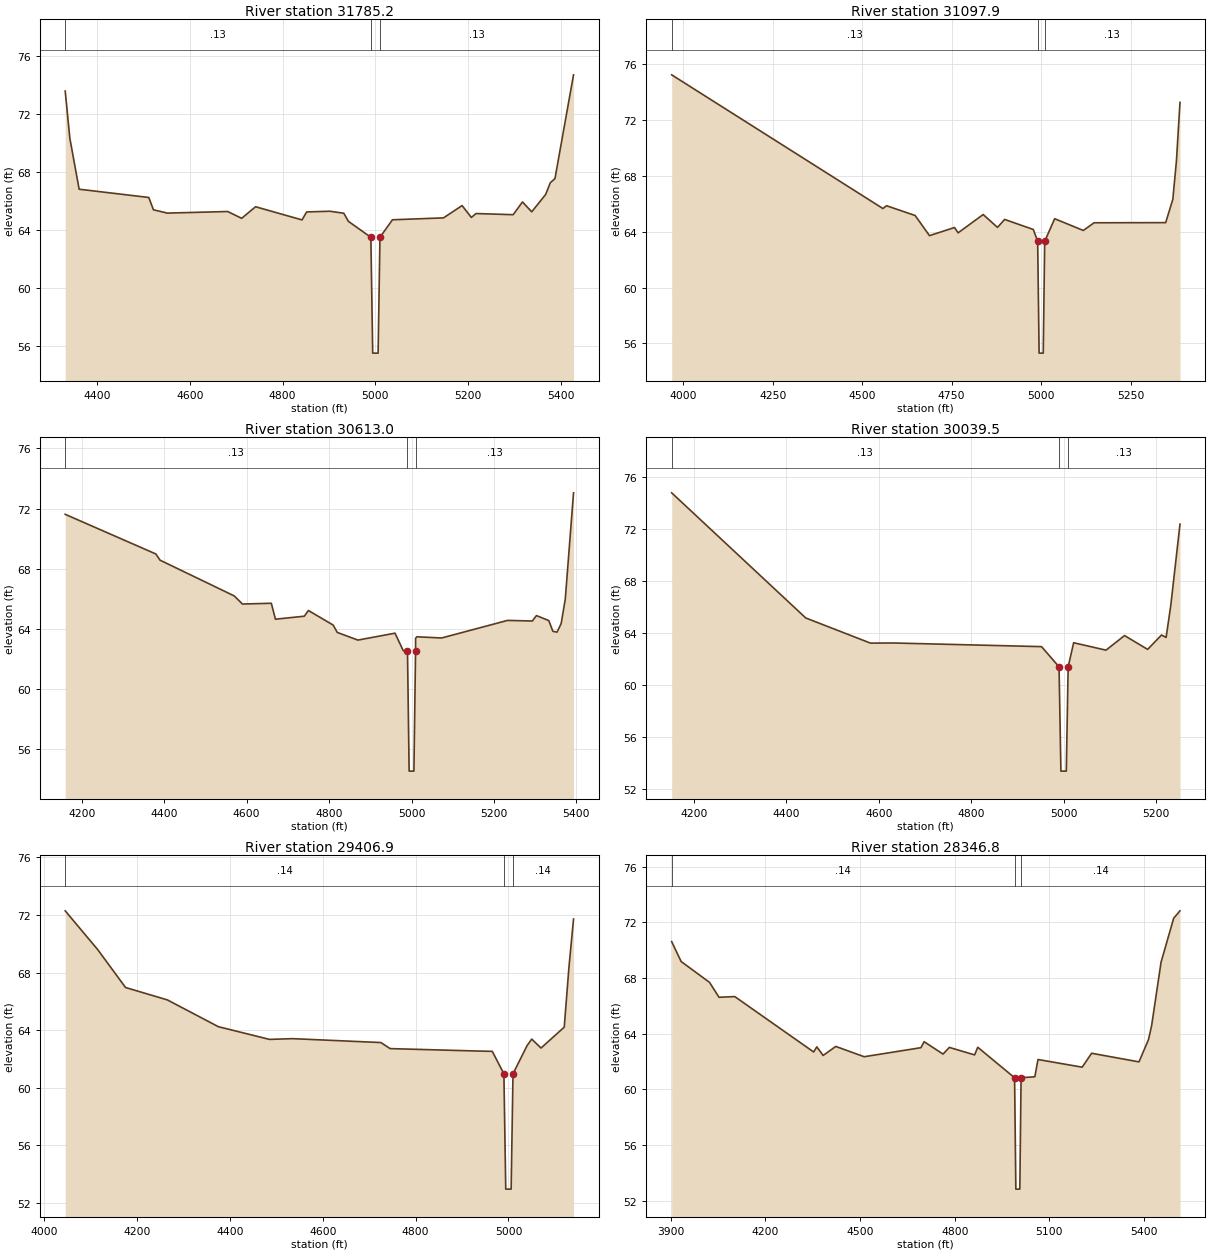
Type RM Length L Ch R = 1 ,31785.2,687.3,687.3,687.3
XS GIS Cut Line= 3
   .283230325027   .209578341856   .286598705356   .176810748847
   .288078921807   .159471070415
BEGIN DESCRIPTION:
Sandy Run 38.0
END DESCRIPTION:
#Sta/Elev= 30
  4331.9   73.61  4341.9   70.35  4361.9   66.83  4511.9   66.26  4521.9   65.41
  4551.9   65.18  4681.9   65.29  4711.9   64.82  4741.9   65.62  4841.9   64.71
  4851.9   65.26  4901.9   65.31  4931.9   65.17  4941.9   64.61  4990.2   63.51
  4994.2   55.51  5005.8   55.51  5009.8   63.51  5036.7   64.72  5146.7   64.85
  5186.7    65.7  5206.7   64.88  5216.7   65.15  5296.7   65.07  5316.7   65.95
  5336.7   65.27  5366.7   66.47  5376.7   67.28  5386.7   67.56  5426.7   74.73
#Mann= 3 , 1 , 0
 4331.90    0.13       0  4990.2   0.045       0  5009.8    0.13       0
Bank Sta=4990.20,5009.80
Exp/Cntr=0.3,0.1

Type RM Length L Ch R = 1 ,31097.9,484.9,484.9,484.9
XS GIS Cut Line= 3
   .302574807141   .212157606138   .303938383788   .178502424792
   .303304005309   .157145015991
BEGIN DESCRIPTION:
Sandy Run 37.0
END DESCRIPTION:
#Sta/Elev= 22
    3968   75.23    4558   65.66    4568   65.86    4648   65.16    4688   63.72
    4758    64.3    4768   63.92    4838   65.23    4878   64.31    4898   64.88
    4978   64.16  4990.2   63.31  4994.2   55.31  5005.8   55.31  5009.8   63.31
  5037.7   64.93  5117.7   64.09  5147.7   64.64  5347.7   64.65  5367.7   66.32
  5377.7   69.05  5387.7   73.26
#Mann= 3 , 1 , 0
 3968.00    0.13       0  4990.2   0.045       0  5009.8    0.13       0
Bank Sta=4990.20,5009.80
Exp/Cntr=0.3,0.1

Type RM Length L Ch R = 1 ,30613.0,573.5,573.5,573.5
XS GIS Cut Line= 3
   .315471128550   .209578341856   .315554120051   .179074022226
   .311759213545   .157660615411
BEGIN DESCRIPTION:
Sandy Run 36.0
END DESCRIPTION:
#Sta/Elev= 30
  4159.9   71.62  4379.9   68.98  4389.9   68.57  4569.9   66.19  4589.9   65.65
  4659.9    65.7  4669.9   64.64  4739.9   64.84  4749.9   65.22  4809.9   64.25
  4819.9   63.76  4869.9   63.25  4959.9   63.71  4979.9   62.55  4990.2   62.53
  4994.2   54.53  5005.8   54.53  5009.8   62.53  5009.9   63.37    5013   63.47
    5073   63.39    5233   64.56    5293   64.52    5303   64.88    5333   64.55
    5343   63.83    5353   63.78    5363   64.35    5373   65.98    5393   73.05
#Mann= 3 , 1 , 0
 4159.90    0.13       0  4990.2   0.045       0  5009.8    0.13       0
Bank Sta=4990.20,5009.80
Exp/Cntr=0.3,0.1

Type RM Length L Ch R = 1 ,30039.5,632.6,632.6,632.6
XS GIS Cut Line= 3
   .335245488045   .199691162109   .330516836862   .173898519290
   .325556543709   .153100480865
BEGIN DESCRIPTION:
Sandy Run 35.0
END DESCRIPTION:
#Sta/Elev= 17
  4152.2   74.75  4442.2   65.15  4582.2   63.22  4632.2   63.23  4952.2   62.95
  4990.1    61.4  4994.1    53.4  5005.8    53.4  5009.8    61.4  5021.7   63.25
  5091.7   62.68  5131.7    63.8  5181.7   62.74  5211.7   63.84  5221.7   63.66
  5231.7   66.09  5251.7   72.35
#Mann= 3 , 1 , 0
 4152.20    0.13       0  4990.1   0.045       0  5009.8    0.13       0
Bank Sta=4990.10,5009.80
Exp/Cntr=0.3,0.1

Type RM Length L Ch R = 1 ,29406.9,1060.1,1060.1,1060.1
XS GIS Cut Line= 3
   .364477149906   .192383246643   .345726158733   .164930879094
   .328377236491   .141547549115
BEGIN DESCRIPTION:
Sandy Run 34.0
END DESCRIPTION:
#Sta/Elev= 21
  4045.2   72.28  4115.2   69.59  4175.2   66.96  4265.2    66.1  4375.2   64.24
  4485.2   63.36  4535.2   63.41  4725.2   63.14  4745.2   62.72  4935.2   62.55
  4965.2   62.53  4990.2   60.97  4994.2   52.97  5005.8   52.97  5009.8   60.97
  5040.2   62.93  5050.2   63.38  5070.2   62.76  5120.2   64.21  5130.2   68.32
  5140.2   71.71
#Mann= 3 , 1 , 0
 4045.20    0.14       0  4990.2   0.045       0  5009.8    0.14       0
Bank Sta=4990.20,5009.80
Exp/Cntr=0.3,0.1

Type RM Length L Ch R = 1 ,28346.8,749.7,749.7,749.7
XS GIS Cut Line= 3
   .372644820132   .184215576417   .362320780009   .143433301532
   .358494933001   .126060470510
BEGIN DESCRIPTION:
Sandy Run 33.0
END DESCRIPTION:
#Sta/Elev= 30
    3903   70.61    3933   69.18    4023   67.68    4053   66.61    4103   66.66
    4353   62.68    4363   63.05    4383   62.43    4423   63.08    4513   62.34
    4693   62.99    4703   63.42    4763   62.53    4783   63.01    4863   62.47
    4873   63.02  4989.7   60.83  4993.7   52.83  5006.3   52.83  5010.3   60.83
  5053.9    60.9  5063.9   62.14  5203.9   61.59  5233.9   62.59  5383.9   61.97
  5413.9   63.56  5423.9   64.56  5453.9   69.13  5493.9   72.29  5513.9   72.82
#Mann= 3 , 1 , 0
 3903.00    0.14       0  4989.7   0.045       0  5010.3    0.14       0
Bank Sta=4989.70,5010.30
Exp/Cntr=0.3,0.1