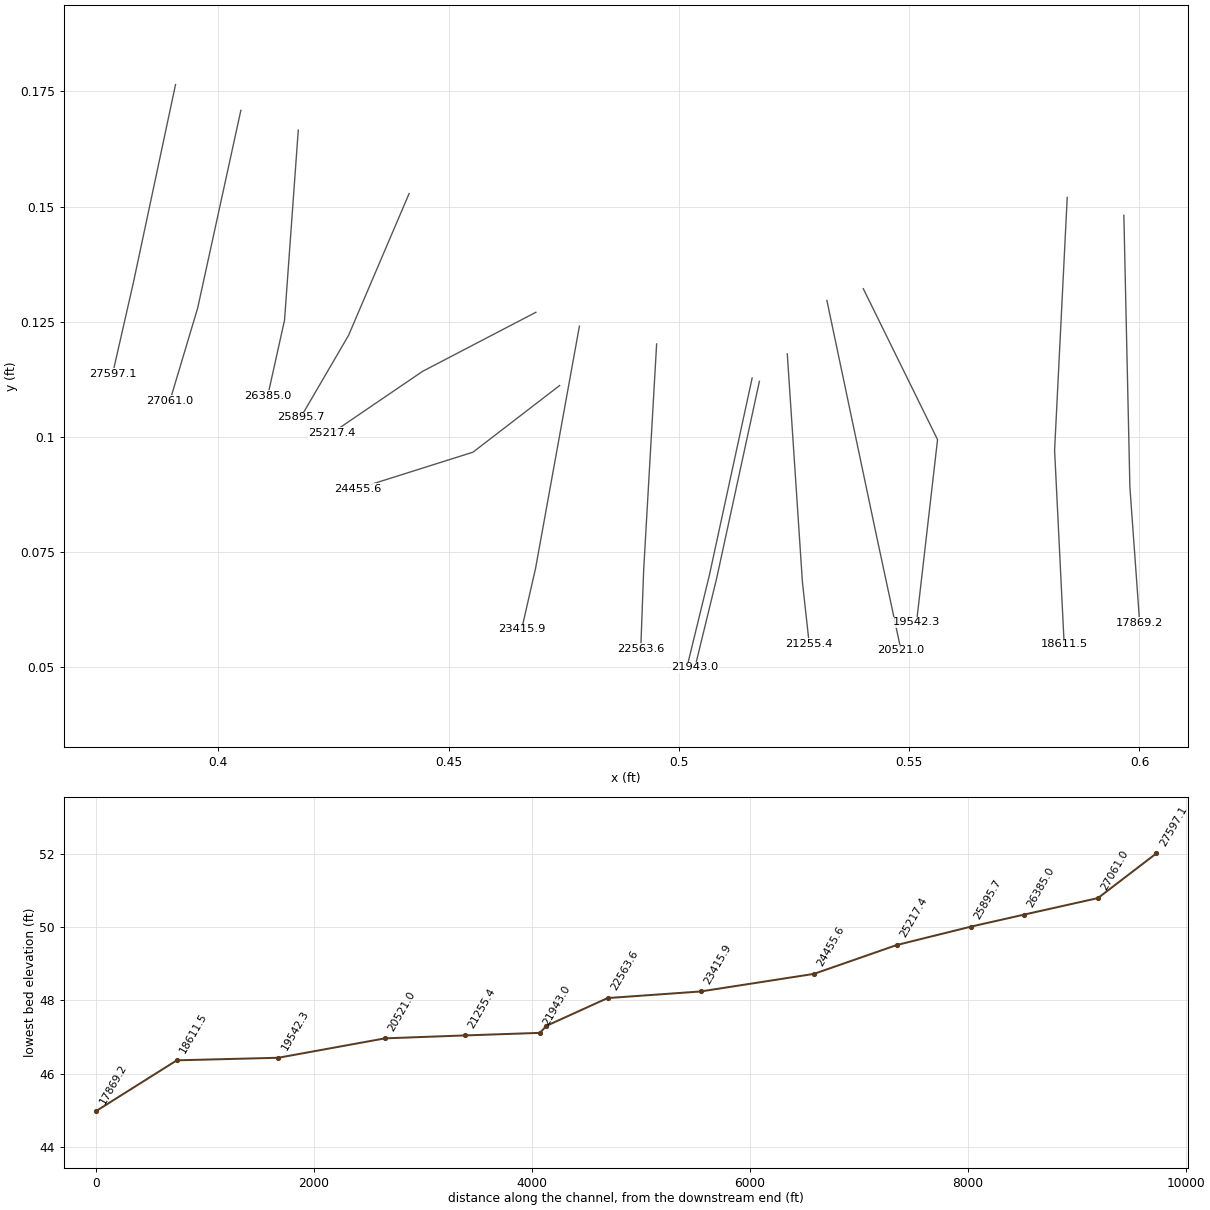
HEC-RAS study Sandy_Run_FINAL.prj: Sandy Run

--- Sandy_Run_FINAL.g01 (geometry) --- (continued)

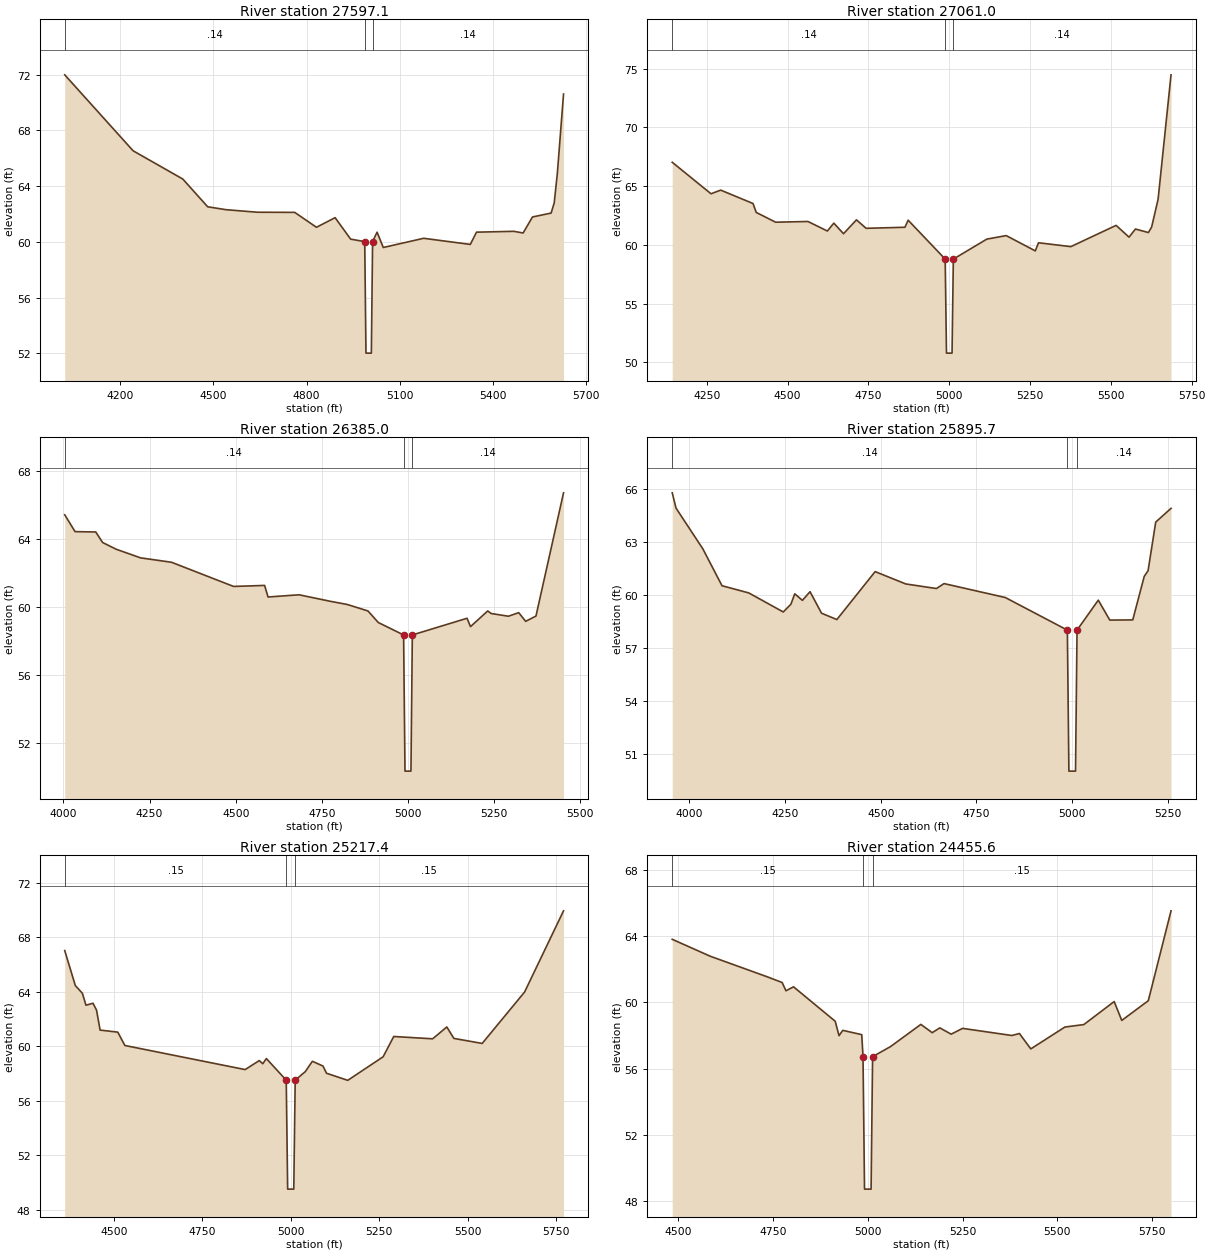
Type RM Length L Ch R = 1 ,27597.1,536.1,536.1,536.1
XS GIS Cut Line= 3
   .390699670106   .176477783572   .381544017746   .133461552767
   .377029648866   .113638413333
BEGIN DESCRIPTION:
Sandy Run 32.0
END DESCRIPTION:
#Sta/Elev= 26
    4022   71.98    4242   66.53    4402    64.5    4482   62.51    4542    62.3
    4642   62.12    4762   62.11    4832   61.04    4892   61.73    4942   60.19
  4987.3   60.01  4991.3   52.01  5008.6   52.01  5012.6   60.01    5027   60.69
    5047   59.59    5177   60.25    5327   59.81    5347   60.69    5467   60.75
    5497   60.63    5527   61.78    5587   62.06    5597   62.79    5607   64.89
    5627    70.6
#Mann= 3 , 1 , 0
 4022.00    0.14       0  4987.3   0.045       0  5012.6    0.14       0
Bank Sta=4987.30,5012.60
Exp/Cntr=0.3,0.1

Type RM Length L Ch R = 1 ,27061.0,676,676,676
XS GIS Cut Line= 3
   .404885623656   .170889377628   .395510022559   .127970131708
   .389475614823   .107792580839
BEGIN DESCRIPTION:
Sandy Run 31.0
END DESCRIPTION:
#Sta/Elev= 30
  4142.8   67.03  4262.8   64.35  4292.8   64.66  4392.8   63.52  4402.8   62.76
  4462.8   61.93  4562.8   61.99  4622.8   61.18  4642.8   61.85  4672.8   60.95
  4712.8   62.13  4742.8   61.41  4862.8    61.5  4872.8    62.1  4987.4   58.79
  4991.4   50.79  5008.6   50.79  5012.6   58.79  5116.2   60.49  5176.2   60.79
  5266.2   59.49  5276.2   60.18  5376.2   59.85  5516.2   61.66  5556.2   60.66
  5576.2   61.35  5616.2   61.05  5626.2   61.52  5646.2   63.89  5686.2   74.47
#Mann= 3 , 1 , 0
 4142.80    0.14       0  4987.4   0.045       0  5012.6    0.14       0
Bank Sta=4987.40,5012.60
Exp/Cntr=0.3,0.1

Type RM Length L Ch R = 1 ,26385.0,489.3,489.3,489.3
XS GIS Cut Line= 3
   .417352067685   .166590603824   .414367546736   .125330078323
   .410737631871   .108963626147
BEGIN DESCRIPTION:
Sandy Run 30.0
END DESCRIPTION:
#Sta/Elev= 28
  4003.9    65.4  4033.9   64.41  4093.9   64.39  4113.9   63.77  4153.9   63.37
  4223.9   62.87  4313.9   62.61  4493.9   61.19  4583.9   61.25  4593.9   60.57
  4683.9    60.7  4773.9   60.32  4823.9   60.13  4883.9   59.75  4913.9   59.07
  4987.3   58.34  4991.3   50.34  5008.6   50.34  5012.6   58.34  5171.4   59.32
  5181.4   58.83  5231.4   59.75  5241.4    59.6  5291.4   59.44  5321.4   59.65
  5341.4   59.14  5371.4   59.45  5451.4   66.69
#Mann= 3 , 1 , 0
 4003.90    0.14       0  4987.3   0.045       0  5012.6    0.14       0
Bank Sta=4987.30,5012.60
Exp/Cntr=0.3,0.1

Type RM Length L Ch R = 1 ,25895.7,678.3,678.3,678.3
XS GIS Cut Line= 3
   .441425200982   .152834527654   .428276565715   .122042740141
   .417915050554   .104280142723
BEGIN DESCRIPTION:
Sandy Run 29.0
END DESCRIPTION:
#Sta/Elev= 28
  3955.3    65.8  3965.3   64.93  4035.3   62.62  4085.3   60.53  4155.3   60.12
  4245.3   59.04  4265.3   59.48  4275.3   60.07  4295.3    59.7  4315.3   60.19
  4345.3   58.97  4385.3   58.61  4485.3   61.33  4565.3   60.63  4645.3   60.37
  4665.3   60.65  4825.3   59.86  4987.4   58.01  4991.4   50.01  5008.7   50.01
  5012.7   58.01  5068.2   59.71  5098.2   58.58  5158.2   58.59  5188.2   61.06
  5198.2   61.38  5218.2   64.14  5258.2   64.92
#Mann= 3 , 1 , 0
 3955.30    0.14       0  4987.4   0.045       0  5012.7    0.14       0
Bank Sta=4987.40,5012.70
Exp/Cntr=0.3,0.1

Type RM Length L Ch R = 1 ,25217.4,761.8,761.8,761.8
XS GIS Cut Line= 3
   .468937353323   .127041884835   .444347487188   .114218738897
   .424659983150   .100819364636
BEGIN DESCRIPTION:
Sandy Run 28.0
END DESCRIPTION:
#Sta/Elev= 30
  4361.1   67.03  4391.1   64.46  4411.1   63.89  4421.1   63.02  4441.1   63.16
  4451.1   62.65  4461.1   61.19  4511.1   61.04  4531.1   60.06  4871.1   58.29
  4911.1   58.95  4921.1   58.72  4931.1    59.1  4987.3   57.51  4991.3   49.51
  5008.6   49.51  5012.6   57.51  5041.2   58.14  5061.2    58.9  5091.2   58.55
  5101.2   58.02  5161.2    57.5  5261.2   59.23  5291.2   60.72  5401.2   60.55
  5441.2   61.42  5461.2   60.58  5541.2   60.21  5661.2   63.99  5771.2   69.95
#Mann= 3 , 1 , 0
 4361.10    0.15       0  4987.3    0.05       0  5012.6    0.15       0
Bank Sta=4987.30,5012.60
Exp/Cntr=0.3,0.1

Type RM Length L Ch R = 1 ,24455.6,1039.7,1039.7,1039.7
XS GIS Cut Line= 3
   .474095881886   .111136421764   .455288374199   .096666641575
   .430207867044   .088746481420
BEGIN DESCRIPTION:
Sandy Run 27.0
END DESCRIPTION:
#Sta/Elev= 29
  4484.1   63.81  4584.1   62.79  4734.1   61.55  4774.1    61.2  4784.1    60.7
  4804.1   60.94  4914.1   58.86  4924.1   57.99  4934.1   58.31  4984.1   58.05
  4987.4   56.72  4991.4   48.72  5008.7   48.72  5012.7   56.72    5060   57.33
    5140   58.67    5170   58.17    5190   58.46    5220   58.08    5250   58.43
    5380      58    5400   58.12    5430   57.19    5520   58.51    5570   58.66
    5650   60.05    5670   58.91    5740    60.1    5800   65.53
#Mann= 3 , 1 , 0
 4484.10    0.15       0  4987.4    0.05       0  5012.7    0.15       0
Bank Sta=4987.40,5012.70
Exp/Cntr=0.3,0.1

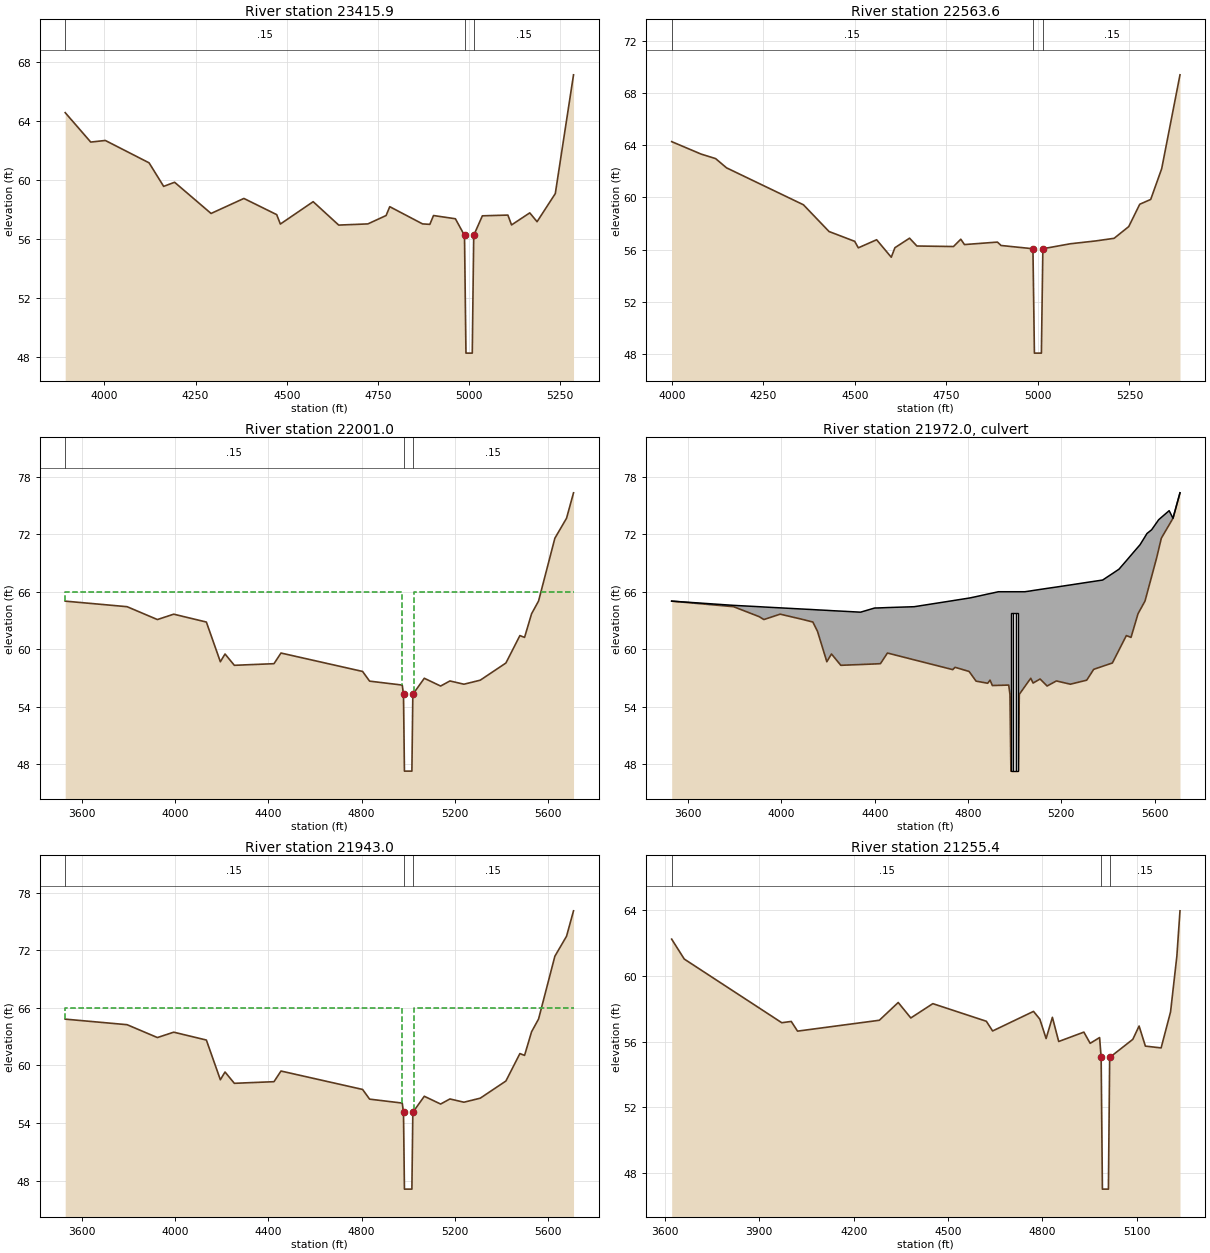
Type RM Length L Ch R = 1 ,23415.9,852.3,852.3,852.3
XS GIS Cut Line= 3
   .478394655690   .124032743173   .468865791606   .071397559178
   .465848587738   .058197292255
BEGIN DESCRIPTION:
Sandy Run 26.0
END DESCRIPTION:
#Sta/Elev= 30
  3892.4   64.58  3962.4   62.58  4002.4   62.69  4122.4   61.17  4162.4   59.57
  4192.4   59.85  4292.4   57.73  4382.4   58.75  4472.4   57.65  4482.4   57.01
  4572.4   58.53  4642.4   56.94  4722.4   57.02  4772.4   57.59  4782.4   58.19
  4872.4   57.02  4892.4   56.99  4902.4   57.59  4962.4   57.37  4987.4   56.24
  4991.4   48.24  5008.7   48.24  5012.7   56.24  5036.4   57.57  5106.4   57.62
  5116.4   56.95  5166.4   57.77  5186.4   57.17  5236.4   59.08  5286.4   67.15
#Mann= 3 , 1 , 0
 3892.40    0.15       0  4987.4    0.05       0  5012.7    0.15       0
Bank Sta=4987.40,5012.70
Exp/Cntr=0.3,0.1

Type RM Length L Ch R = 1 ,22563.6,562.6,562.6,562.6
XS GIS Cut Line= 3
   .495159873522   .120163846750   .492348792116   .071081002311
   .491714413637   .053952783371
BEGIN DESCRIPTION:
Sandy Run 25.0
END DESCRIPTION:
#Sta/Elev= 30
  3999.3   64.27  4079.3   63.32  4119.3   62.97  4149.3   62.26  4359.3   59.43
  4429.3   57.38  4499.3   56.63  4509.3   56.13  4559.3   56.75  4599.3   55.41
  4609.3   56.14  4649.3   56.87  4669.3   56.27  4769.3   56.23  4789.3   56.79
  4799.3   56.38  4889.3   56.57  4899.3   56.31  4986.4   56.06  4990.4   48.06
  5009.5   48.06  5013.5   56.06  5088.2   56.44  5158.2   56.66  5208.2   56.86
  5248.2   57.76  5278.2   59.47  5308.2   59.84  5338.2    62.2  5388.2   69.39
#Mann= 3 , 1 , 0
 3999.30    0.15       0  4986.4    0.05       0  5013.5    0.15       0
Bank Sta=4986.40,5013.50
Exp/Cntr=0.5,0.3

Type RM Length L Ch R = 1 ,22001.0,58,58,58
XS GIS Cut Line= 3
   .515901810619   .112769953646   .506620421197   .069985391351
   .501923223674   .050715943979
BEGIN DESCRIPTION:
Upstream Section of Bridge/Culvert/Weir
END DESCRIPTION:
#Sta/Elev= 30
  3529.2   65.02  3794.6   64.44  3924.6    63.1  3994.6   63.66  4134.6   62.84
  4194.6    58.7  4214.6   59.51  4254.6   58.33  4424.6    58.5  4454.6   59.61
  4804.6   57.69  4834.6   56.68  4974.6   56.27    4980    55.3    4984    47.3
    5016    47.3    5020    55.3  5069.2   56.98  5139.2   56.17  5179.2    56.7
  5239.2   56.36  5309.2   56.78  5419.2   58.57  5479.2   61.43  5499.2   61.24
  5529.2    63.7  5559.2   65.03  5629.2   71.58  5679.2   73.66  5709.2   76.31
#Mann= 3 , 1 , 0
 3529.20    0.15       0    4980    0.05       0    5020    0.15       0
#XS Ineff= 2 , 0
       0    4974      66    5026       0      66
Bank Sta=4980.00,5020.00
Exp/Cntr=0.5,0.3

Type RM Length L Ch R = 2 ,21972.0,,,
BEGIN DESCRIPTION:
HWY 13/258-TOR
Structure ID: HWY 13/258 SR-Culvert
Approximate Survey Structure
END DESCRIPTION:
Bridge Culvert--1,0,-1,-1, 0
Deck Dist Width WeirC Skew NumUp NumDn MinLoCord MaxHiCord MaxSubmerge Is_Ogee
10,38,3,,56,56,,,0.95,0,1,1,,
  3529.2  3794.6  3904.6  3924.6  3994.6  4094.6  4134.6  4154.6  4194.6  4214.6
  4254.6  4339.2  4399.2  4424.6  4454.6  4569.2  4734.6  4744.6  4804.6  4809.2
  4834.6  4884.6  4894.6  4904.6  4930.3  4974.6    4980    4984    5000    5016
    5020  5043.9  5069.2  5079.2  5109.2  5139.2  5179.2  5239.2  5309.2  5339.2
  5377.5  5419.2  5447.5  5479.2  5499.2  5529.2  5537.5  5559.2  5567.5  5587.5
  5609.2  5617.5  5629.2  5662.7  5679.2  5709.2
   65.02   64.58   64.44   64.41   64.32   64.19   64.14   64.11   64.06   64.03
   63.98   63.87    64.3   64.32   64.35   64.44   65.07   65.11   65.34   65.36
   65.49   65.76   65.81   65.86      66      66      66      66      66      66
      66      66   66.09   66.13   66.24   66.35   66.49   66.71   66.97   67.08
   67.22   67.89   68.35   69.24   69.81   70.66   70.89   71.74   72.07   72.46
   73.21    73.5   73.75   74.45   73.66   76.31
   65.02   64.44    63.4    63.1   63.66   63.09   62.84   61.87    58.7   59.51
   58.33   58.41   58.47    58.5   59.61    58.9   57.88   58.12   57.69   57.54
   56.68   56.46   56.78   56.22   56.24   56.27    55.3    47.3    47.3    47.3
    55.3   56.12   56.98   56.48    56.9   56.17    56.7   56.36   56.78   57.91
   58.23   58.57   59.92   61.43   61.24    63.7   64.07   65.03   65.78   67.58
   69.54   70.39   71.58   72.97   73.66   76.31
  3529.2  3794.6  3904.6  3924.6  3994.6  4094.6  4134.6  4154.6  4194.6  4214.6
  4254.6  4339.2  4399.2  4424.6  4454.6  4569.2  4734.6  4744.6  4804.6  4809.2
  4834.6  4884.6  4894.6  4904.6  4930.3  4974.6    4980    4984    5000    5016
    5020  5043.9  5069.2  5079.2  5109.2  5139.2  5179.2  5239.2  5309.2  5339.2
  5377.5  5419.2  5447.5  5479.2  5499.2  5529.2  5537.5  5559.2  5567.5  5587.5
  5609.2  5617.5  5629.2  5662.7  5679.2  5709.2
   64.93   64.58   64.44   64.41   64.32   64.19   64.14   64.11   64.06   64.03
   63.98   63.87    64.3   64.32   64.35   64.44   65.07   65.11   65.34   65.36
   65.49   65.76   65.81   65.86      66      66      66      66      66      66
      66      66   66.09   66.13   66.24   66.35   66.49   66.71   66.97   67.08
   67.22   67.89   68.35   69.24   69.81   70.66   70.89   71.74   72.07   72.46
   73.21    73.5   73.75   74.45   73.57   76.22
   64.83   64.25   63.21   62.91   63.47    62.9   62.65   61.68   58.51   59.32
   58.14   58.22   58.28   58.31   59.42   58.71   57.69   57.93    57.5   57.35
   56.49   56.27   56.59   56.03   56.05   56.08   55.11   47.11   47.11   47.11
   55.11   55.93   56.79   56.29   56.71   55.98   56.51   56.17   56.59   57.72
   58.04   58.38   59.73   61.24   61.05   63.51   63.88   64.84   65.59   67.39
   69.35    70.2   71.39   72.78   73.47   76.12
BR Coef= 1 , 0 , 0 ,1.25, 0 ,,,0.8,-1,2,0,
Wspro=,,,, 1 ,,,, 0 ,,,, 0 ,,,,-1 ,-1 ,-1 , 0 , 0 , 0 , 0 , 0
Culvert=2,16.5,10.0,38.0,0.015,0.4,1.0,8,1,47.30,4989.02,47.11,4989.02,Culvert #1  ,0,10
Culvert=2,16.5,10.0,38.0,0.015,0.4,1.0,8,1,47.30,5000.02,47.11,5000.02,Culvert #2  ,0,10
Culvert=2,16.5,10.0,38.0,0.015,0.4,1.0,8,1,47.30,5011.02,47.11,5011.02,Culvert #3  ,0,10
BC Design=,, 0 ,, 0 ,,,,,,
BR U #Sta/Elev= 56
  3529.2   65.02  3794.6   64.44  3904.6    63.4  3924.6    63.1  3994.6   63.66
  4094.6   63.09  4134.6   62.84  4154.6   61.87  4194.6    58.7  4214.6   59.51
  4254.6   58.33  4339.2   58.41  4399.2   58.47  4424.6    58.5  4454.6   59.61
  4569.2    58.9  4734.6   57.88  4744.6   58.12  4804.6   57.69  4809.2   57.54
  4834.6   56.68  4884.6   56.46  4894.6   56.78  4904.6   56.22  4930.3   56.24
  4974.6   56.27    4980    55.3    4984    47.3    5000    47.3    5016    47.3
    5020    55.3  5043.9   56.12  5069.2   56.98  5079.2   56.48  5109.2    56.9
  5139.2   56.17  5179.2    56.7  5239.2   56.36  5309.2   56.78  5339.2   57.91
  5377.5   58.23  5419.2   58.57  5447.5   59.92  5479.2   61.43  5499.2   61.24
  5529.2    63.7  5537.5   64.07  5559.2   65.03  5567.5   65.78  5587.5   67.58
  5609.2   69.54  5617.5   70.39  5629.2   71.58  5662.7   72.97  5679.2   73.66
  5709.2   76.31
BR U #Mann= 3
 3529.20    0.15    4980    0.05    5020    0.15
BR U Banks=4980.00,5020.00
BR D #Sta/Elev= 56
  3529.2   64.83  3794.6   64.25  3904.6   63.21  3924.6   62.91  3994.6   63.47
  4094.6    62.9  4134.6   62.65  4154.6   61.68  4194.6   58.51  4214.6   59.32
  4254.6   58.14  4339.2   58.22  4399.2   58.28  4424.6   58.31  4454.6   59.42
  4569.2   58.71  4734.6   57.69  4744.6   57.93  4804.6    57.5  4809.2   57.35
  4834.6   56.49  4884.6   56.27  4894.6   56.59  4904.6   56.03  4930.3   56.05
  4974.6   56.08    4980   55.11    4984   47.11    5000   47.11    5016   47.11
    5020   55.11  5043.9   55.93  5069.2   56.79  5079.2   56.29  5109.2   56.71
  5139.2   55.98  5179.2   56.51  5239.2   56.17  5309.2   56.59  5339.2   57.72
  5377.5   58.04  5419.2   58.38  5447.5   59.73  5479.2   61.24  5499.2   61.05
  5529.2   63.51  5537.5   63.88  5559.2   64.84  5567.5   65.59  5587.5   67.39
  5609.2   69.35  5617.5    70.2  5629.2   71.39  5662.7   72.78  5679.2   73.47
  5709.2   76.12
BR D #Mann= 3
 3529.20    0.15    4980    0.05    5020    0.15
BR D Banks=4980.00,5020.00

Type RM Length L Ch R = 1 ,21943.0,687.6,687.6,687.6
XS GIS Cut Line= 3
   .517475977825   .112054009668   .508194588402   .069269447373
   .503497390879   .050000000000
BEGIN DESCRIPTION:
Downstream Section of Bridge/Culvert/Weir
END DESCRIPTION:
#Sta/Elev= 30
  3529.2   64.83  3794.6   64.25  3924.6   62.91  3994.6   63.47  4134.6   62.65
  4194.6   58.51  4214.6   59.32  4254.6   58.14  4424.6   58.31  4454.6   59.42
  4804.6    57.5  4834.6   56.49  4974.6   56.08    4980   55.11    4984   47.11
    5016   47.11    5020   55.11  5069.2   56.79  5139.2   55.98  5179.2   56.51
  5239.2   56.17  5309.2   56.59  5419.2   58.38  5479.2   61.24  5499.2   61.05
  5529.2   63.51  5559.2   64.84  5629.2   71.39  5679.2   73.47  5709.2   76.12
#Mann= 3 , 1 , 0
 3529.20    0.15       0    4980    0.05       0    5020    0.15       0
#XS Ineff= 2 , 0
       0    4974      66    5026       0      66
Bank Sta=4980.00,5020.00
Exp/Cntr=0.5,0.3

Type RM Length L Ch R = 1 ,21255.4,734.4,734.4,734.4
XS GIS Cut Line= 3
   .523531780622   .118014459849   .526816689487   .068464191084
   .528300126140   .055012582510
BEGIN DESCRIPTION:
Sandy Run 24.0
END DESCRIPTION:
#Sta/Elev= 30
  3621.6   62.23  3661.6   61.02  3971.6   57.15  4001.6   57.23  4021.6   56.64
  4281.6    57.3  4341.6   58.38  4381.6   57.44  4451.6   58.31  4621.6   57.24
  4641.6   56.65  4771.6   57.84  4791.6   57.37  4811.6   56.19  4831.6   57.48
  4851.6   56.01  4931.6   56.58  4951.6    55.9  4981.6   56.25  4986.5   55.04
  4990.5   47.04  5009.6   47.04  5013.6   55.04  5087.1   56.14  5107.1   56.95
  5127.1   55.73  5177.1   55.62  5207.1   57.81  5227.1   61.19  5237.1   63.95
#Mann= 3 , 1 , 0
 3621.60    0.15       0  4986.5    0.05       0  5013.6    0.15       0
Bank Sta=4986.50,5013.60
Exp/Cntr=0.3,0.1

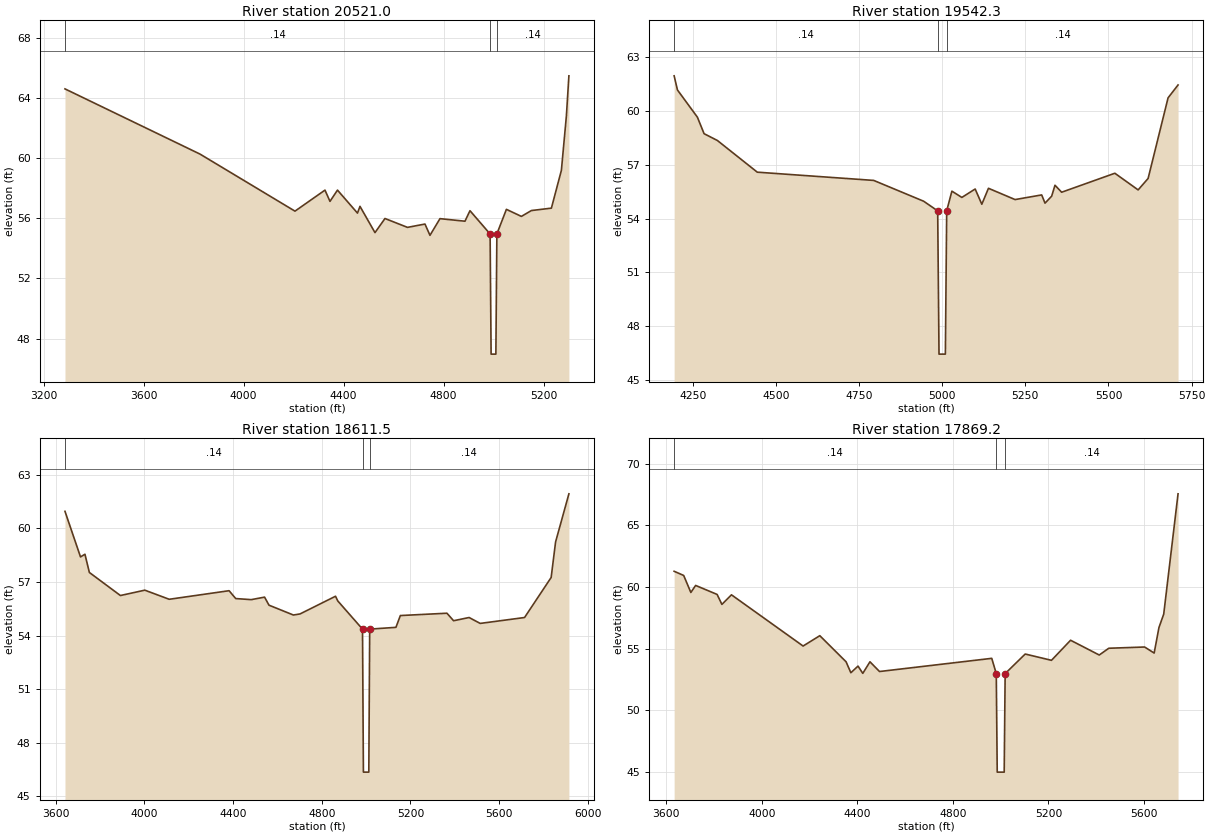
Type RM Length L Ch R = 1 ,20521.0,978.7,978.7,978.7
XS GIS Cut Line= 3
   .532129328229   .129621149117   .542676151467   .079565814470
   .548226963161   .053662026569
BEGIN DESCRIPTION:
Sandy Run 23.0
END DESCRIPTION:
#Sta/Elev= 27
  3285.9   64.62  3825.9   60.28  4205.9   56.48  4325.9   57.88  4345.9   57.13
  4375.9   57.88  4455.9   56.35  4465.9    56.8  4525.9   55.05  4565.9   55.99
  4655.9    55.4  4725.9   55.62  4745.9   54.87  4785.9   55.98  4885.9   55.81
  4905.9   56.51  4986.4   54.96  4990.4   46.96  5009.5   46.96  5013.5   54.96
  5051.6    56.6  5111.6   56.13  5151.6   56.52  5231.6   56.68  5271.6    59.2
  5291.6   62.83  5301.6   65.49
#Mann= 3 , 1 , 0
 3285.90    0.14       0  4986.4    0.05       0  5013.5    0.14       0
Bank Sta=4986.40,5013.50
Exp/Cntr=0.3,0.1

Type RM Length L Ch R = 1 ,19542.3,930.8,930.8,930.8
XS GIS Cut Line= 3
   .540032907804   .132166363372   .556156694151   .099390141946
   .551593617650   .059706533079
BEGIN DESCRIPTION:
Sandy Run 22.0
END DESCRIPTION:
#Sta/Elev= 28
  4194.1   61.97  4204.1   61.18  4264.1   59.66  4284.1   58.74  4324.1   58.36
  4444.1   56.59  4794.1   56.13  4944.1   54.97  4986.5   54.43  4990.5   46.43
  5009.6   46.43  5013.6   54.43  5029.2   55.53  5059.2   55.18  5099.2   55.65
  5119.2    54.8  5139.2   55.69  5219.2   55.06  5299.2   55.32  5309.2   54.86
  5329.2   55.25  5339.2   55.86  5359.2   55.47  5519.2   56.53  5589.2    55.6
  5619.2   56.24  5679.2   60.74  5709.2   61.46
#Mann= 3 , 1 , 0
 4194.10    0.14       0  4986.5    0.05       0  5013.6    0.14       0
Bank Sta=4986.50,5013.60
Exp/Cntr=0.3,0.1

Type RM Length L Ch R = 1 ,18611.5,742.3,742.3,742.3
XS GIS Cut Line= 3
   .584312326890   .151963622580   .581572336461   .097099343639
   .583646428250   .054983648400
BEGIN DESCRIPTION:
Sandy Run 21.0
END DESCRIPTION:
#Sta/Elev= 30
  3642.1   60.95  3712.1    58.4  3732.1   58.55  3752.1   57.53  3892.1   56.24
  4002.1   56.54  4112.1   56.03  4382.1   56.51  4412.1   56.07  4482.1   56.01
  4542.1   56.15  4562.1    55.7  4672.1   55.15  4702.1   55.21  4862.1    56.2
  4872.1   55.94  4983.8   54.36  4987.8   46.36  5012.2   46.36  5016.2   54.36
  5134.5   54.46  5154.5   55.12  5364.5   55.25  5394.5   54.83  5464.5   55.01
  5514.5   54.68  5714.5   55.01  5834.5   57.25  5854.5   59.24  5914.5   61.93
#Mann= 3 , 1 , 0
 3642.10    0.14       0  4983.8    0.05       0  5016.2    0.14       0
Bank Sta=4983.80,5016.20
Exp/Cntr=0.3,0.1

Type RM Length L Ch R = 1 ,17869.2,820,820,820
XS GIS Cut Line= 3
   .596610935276   .148105876471   .597919944033   .089081491658
   .600043095470   .059642062716
BEGIN DESCRIPTION:
Sandy Run 20.0
END DESCRIPTION:
#Sta/Elev= 30
  3632.5   61.28  3672.5   60.94  3702.5   59.56  3722.5   60.13  3812.5    59.4
  3832.5   58.59  3872.5   59.37  4172.5   55.21  4242.5   56.05  4352.5   53.93
  4372.5   53.04  4402.5   53.58  4422.5   52.99  4452.5   53.93  4492.5   53.14
  4962.5   54.21  4981.4   52.97  4985.4   44.97  5014.6   44.97  5018.6   52.97
  5102.6   54.56  5212.6   54.05  5292.6   55.68  5412.6   54.48  5452.6   55.03
  5602.6   55.13  5642.6   54.64  5662.6   56.71  5682.6    57.8  5742.6   67.57
#Mann= 3 , 1 , 0
 3632.50    0.14       0  4981.4    0.05       0  5018.6    0.14       0
Bank Sta=4981.40,5018.60
Exp/Cntr=0.3,0.1