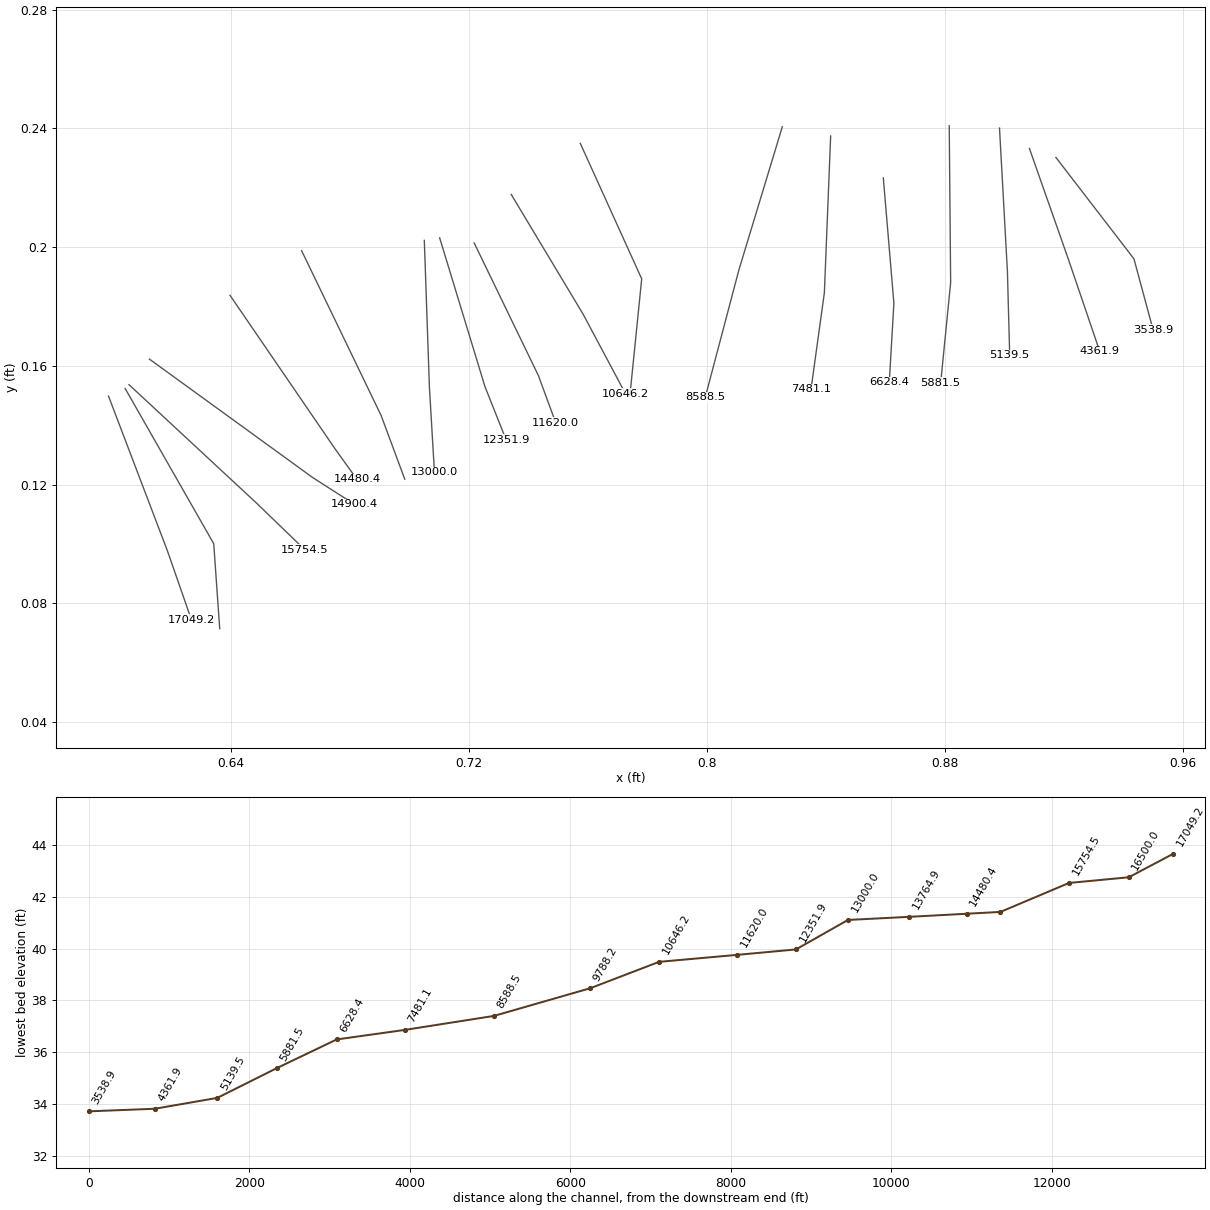
HEC-RAS study Sandy_Run_FINAL.prj: Sandy Run

--- Sandy_Run_FINAL.g01 (geometry) --- (continued)

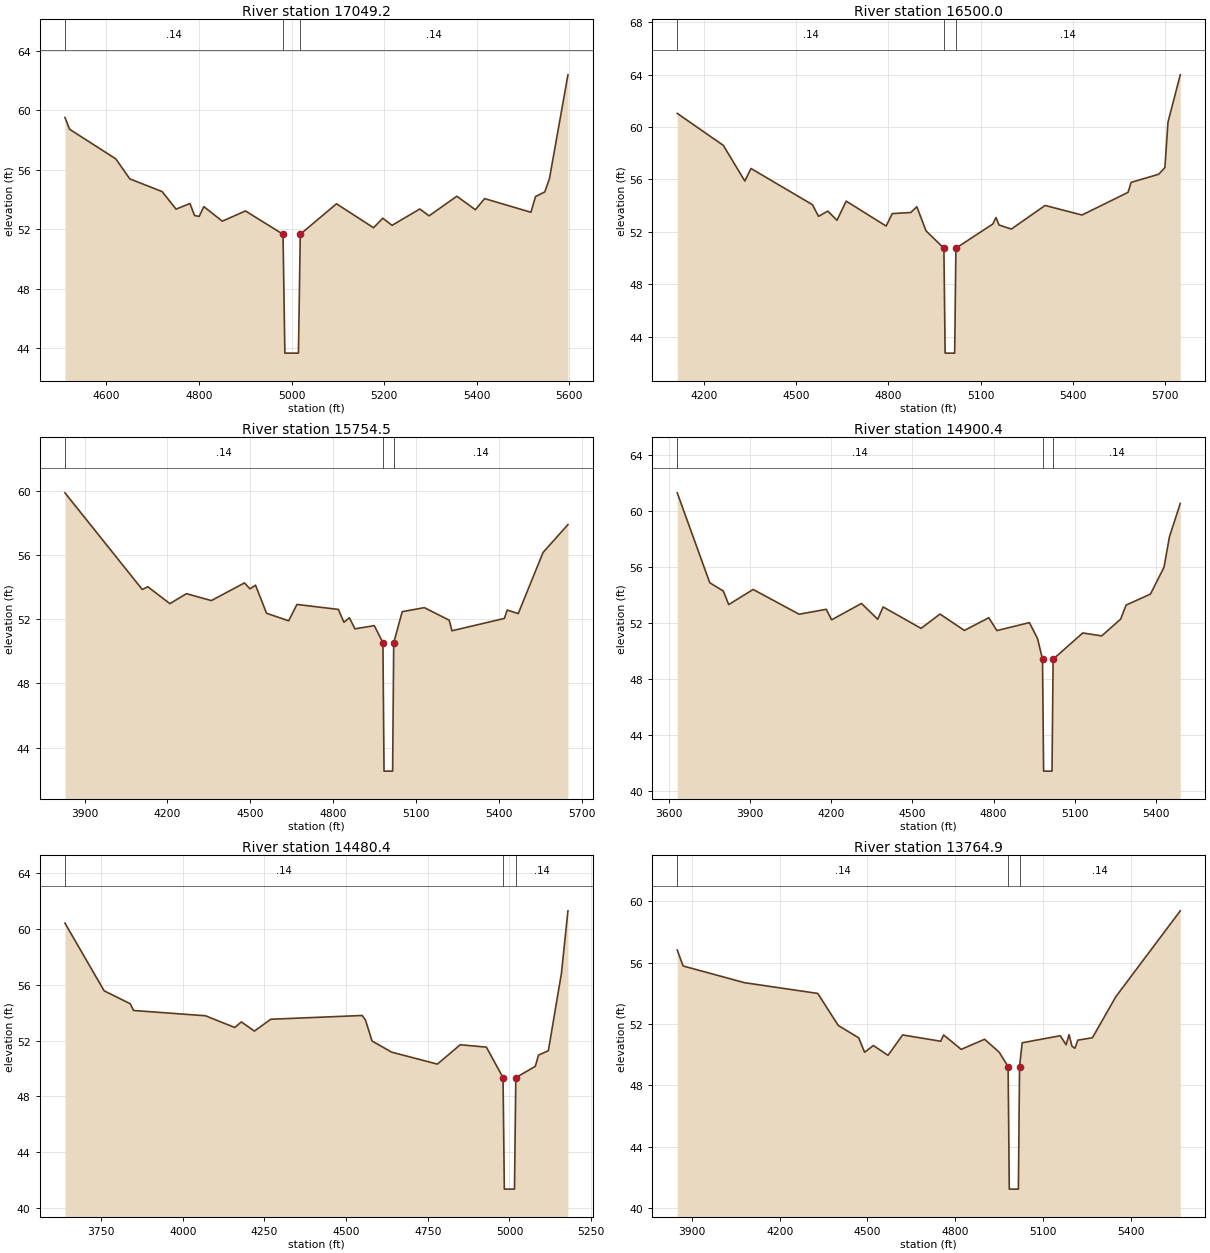
Type RM Length L Ch R = 1 ,17049.2,549.2,549.2,549.2
XS GIS Cut Line= 3
   .598760322178   .149825385992   .618537244608   .097804195748
   .626604885040   .074599186940
BEGIN DESCRIPTION:
Sandy Run 19.0
END DESCRIPTION:
#Sta/Elev= 30
  4510.3   59.52  4520.3   58.73  4620.3   56.73  4650.3   55.39  4720.3   54.53
  4750.3   53.35  4780.3   53.73  4790.3   52.92  4800.3   52.86  4810.3   53.52
  4850.3   52.54  4900.3   53.23  4981.4   51.66  4985.4   43.66  5014.7   43.66
  5018.7   51.66  5096.9   53.71  5176.9    52.1  5196.9   52.74  5216.9   52.26
  5276.9   53.36  5296.9    52.9  5356.9   54.22  5396.9   53.31  5416.9   54.06
  5516.9   53.14  5526.9    54.2  5546.9   54.51  5556.9    55.4  5596.9   62.39
#Mann= 3 , 1 , 0
 4510.30    0.14       0  4981.4    0.05       0  5018.7    0.14       0
Bank Sta=4981.40,5018.70
Exp/Cntr=0.3,0.1

Type RM Length L Ch R = 1 ,16500.0,745.5,745.5,745.5
XS GIS Cut Line= 3
   .604348728122   .152404650274   .634134228090   .100138456698
   .636146498769   .071504609514
BEGIN DESCRIPTION:
Sandy Run 18.0
END DESCRIPTION:
#Sta/Elev= 30
  4112.4   61.04  4262.4    58.6  4332.4   55.88  4352.4   56.84  4552.4   54.08
  4572.4   53.19  4602.4   53.59  4632.4   52.89  4662.4   54.35  4792.4   52.45
  4812.4    53.4  4872.4   53.48  4892.4   53.92  4922.4   52.08  4980.5   50.76
  4984.5   42.76  5015.6   42.76  5019.6   50.76    5140   52.61    5150    53.1
    5160   52.53    5200   52.22    5310   54.02    5430   53.29    5580   55.02
    5590   55.78    5680    56.4    5700   56.91    5710   60.37    5750   63.98
#Mann= 3 , 1 , 0
 4112.40    0.14       0  4980.5    0.05       0  5019.6    0.14       0
Bank Sta=4980.50,5019.60
Exp/Cntr=0.3,0.1

Type RM Length L Ch R = 1 ,15754.5,854.1,854.1,854.1
XS GIS Cut Line= 3
   .605638360262   .153694282415   .648670222371   .113663657728
   .664794008717   .098068520114
BEGIN DESCRIPTION:
Sandy Run 17.0
END DESCRIPTION:
#Sta/Elev= 30
  3829.1   59.87  4109.1   53.85  4129.1   54.02  4209.1   52.97  4269.1   53.59
  4359.1   53.16  4479.1   54.26  4499.1   53.89  4519.1   54.12  4559.1   52.37
  4639.1    51.9  4669.1   52.92  4819.1   52.61  4839.1   51.81  4859.1   52.09
  4879.1    51.4  4949.1    51.6  4980.4   50.54  4984.4   42.54  5015.5   42.54
  5019.5   50.54  5050.3   52.47  5130.3   52.72  5220.3   51.94  5230.3   51.28
  5420.3   52.05  5430.3   52.57  5470.3   52.35  5560.3   56.16  5650.3   57.89
#Mann= 3 , 1 , 0
 3829.10    0.14       0  4980.4    0.05       0  5019.5    0.14       0
Bank Sta=4980.40,5019.50
Exp/Cntr=0.3,0.1

Type RM Length L Ch R = 1 ,14900.4,420,420,420
XS GIS Cut Line= 3
   .612516398347   .162291830021   .667437252381   .122386361818
   .681446443797   .113399333362
BEGIN DESCRIPTION:
Sandy Run 16.0
END DESCRIPTION:
#Sta/Elev= 30
  3632.1   61.32  3752.1   54.89  3802.1    54.3  3822.1   53.33  3912.1   54.41
  4082.1   52.64  4182.1   52.99  4202.1   52.24  4312.1   53.41  4372.1   52.28
  4392.1   53.16  4532.1   51.63  4602.1   52.65  4692.1   51.48  4782.1   52.39
  4812.1   51.47  4932.1   52.04  4962.1    50.9  4980.5   49.42  4984.5   41.42
  5015.6   41.42  5019.6   49.42    5129    51.3    5199   51.09    5269   52.29
    5289   53.29    5379   54.08    5429      56    5449   58.17    5489   60.56
#Mann= 3 , 1 , 0
 3632.10    0.14       0  4980.5    0.05       0  5019.6    0.14       0
Bank Sta=4980.50,5019.60
Exp/Cntr=0.3,0.1

Type RM Length L Ch R = 1 ,14480.4,715.5,715.5,715.5
XS GIS Cut Line= 3
   .639598673307   .183785699037   .675086598041   .131848869314
   .682307278701   .121791492680
BEGIN DESCRIPTION:
Sandy Run 15.0
END DESCRIPTION:
#Sta/Elev= 25
  3639.4   60.44  3759.4   55.58  3839.4   54.65  3849.4   54.17  4069.4   53.79
  4159.4   52.95  4179.4   53.35  4219.4   52.69  4269.4   53.54  4549.4   53.81
  4559.4   53.48  4579.4   51.98  4639.4   51.18  4779.4   50.32  4849.4   51.71
  4929.4   51.54  4980.4   49.35  4984.4   41.35  5015.5   41.35  5019.5   49.35
  5079.1   50.16  5089.1   50.97  5119.1   51.28  5159.1   56.83  5179.1   61.32
#Mann= 3 , 1 , 0
 3639.40    0.14       0  4980.4    0.05       0  5019.5    0.14       0
Bank Sta=4980.40,5019.50
Exp/Cntr=0.3,0.1

Type RM Length L Ch R = 1 ,13764.9,764.9,764.9,764.9
XS GIS Cut Line= 3
   .663671806605   .198831407348   .690433472252   .143267986758
   .698363203243   .121857713085
BEGIN DESCRIPTION:
Sandy Run 14.0
END DESCRIPTION:
#Sta/Elev= 29
  3850.1   56.83  3870.1   55.79  4080.1    54.7  4330.1      54  4400.1   51.91
  4470.1    51.1  4490.1   50.16  4520.1    50.6  4570.1   49.96  4620.1   51.29
  4750.1   50.88  4760.1   51.29  4820.1   50.35  4900.1   51.01  4950.1   50.16
  4980.4   49.23  4984.4   41.23  5015.5   41.23  5019.5   49.23  5028.5   50.78
  5158.5   51.24  5178.5   50.65  5188.5   51.31  5198.5   50.56  5208.5   50.42
  5218.5   50.95  5268.5   51.11  5348.5   53.79  5568.5   59.39
#Mann= 3 , 1 , 0
 3850.10    0.14       0  4980.4    0.05       0  5019.5    0.14       0
Bank Sta=4980.40,5019.50
Exp/Cntr=0.3,0.1

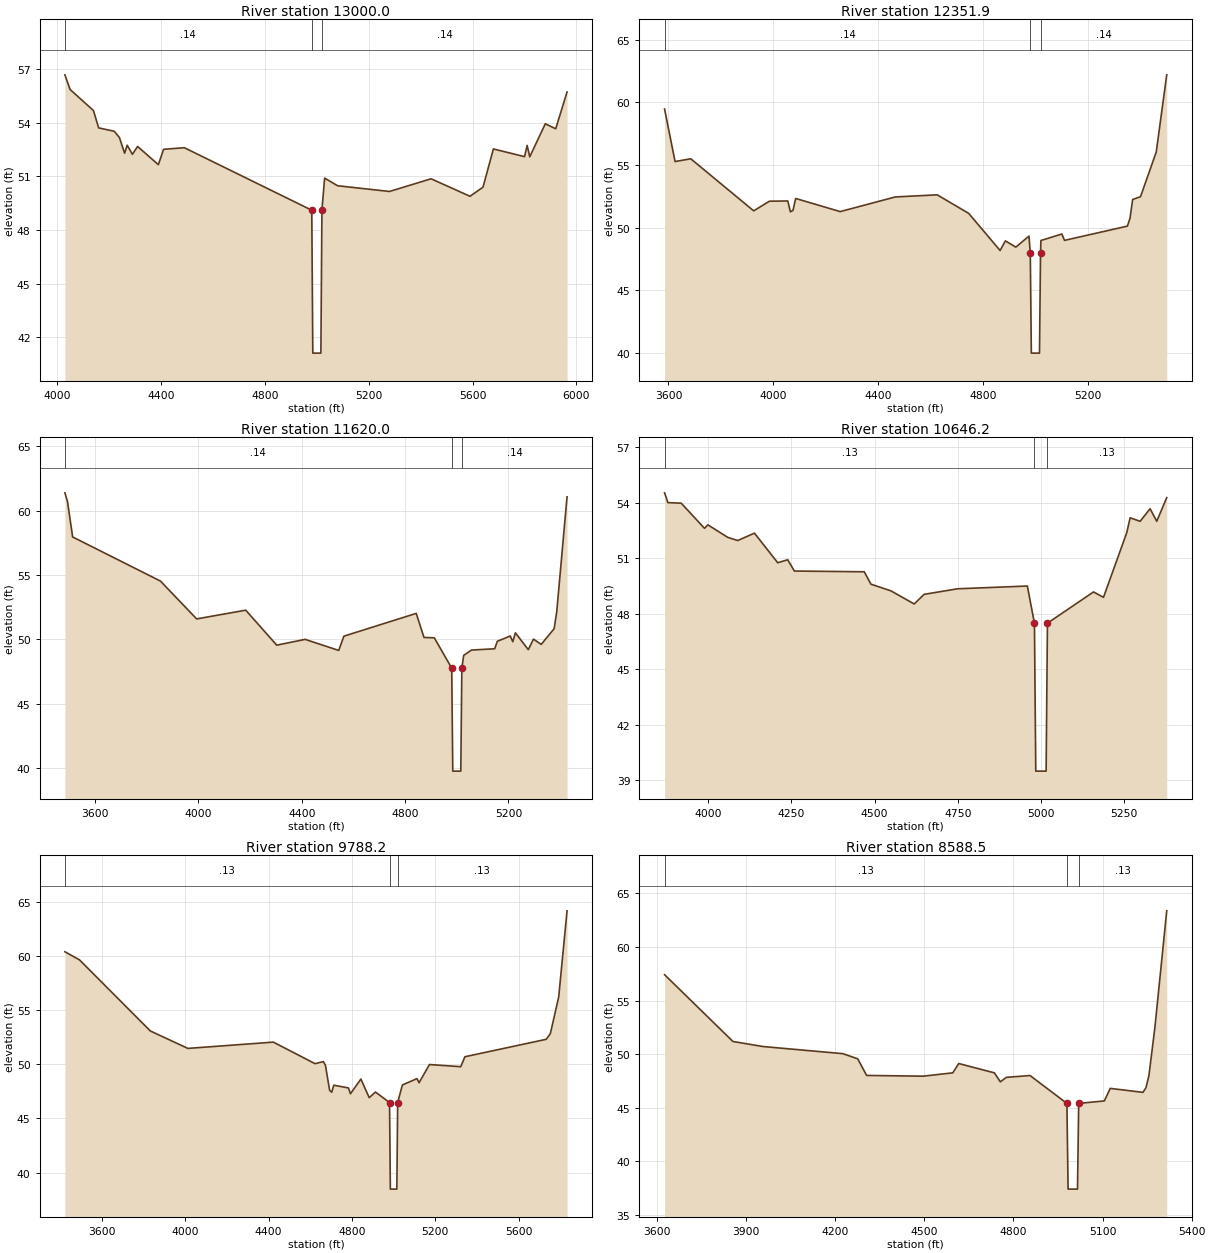
Type RM Length L Ch R = 1 ,13000.0,648.1,648.1,648.1
XS GIS Cut Line= 3
   .704940035115   .202270426391   .706652979512   .152795512065
   .708353305366   .124112425750
BEGIN DESCRIPTION:
Sandy Run 13.0
END DESCRIPTION:
#Sta/Elev= 30
  4029.7   56.69  4049.7   55.87  4139.7   54.69  4159.7   53.72  4219.7   53.53
  4239.7   53.18  4259.7    52.3  4269.7   52.75  4289.7   52.24  4309.7   52.68
  4389.7   51.66  4409.7   52.52  4489.7   52.61  4980.5   49.11  4984.5   41.11
  5015.6   41.11  5019.6   49.11    5030   50.91    5080   50.48    5280   50.16
    5440   50.87    5590   49.89    5640    50.4    5680   52.54    5800   52.11
    5810   52.74    5820    52.1    5880   53.95    5920   53.67  5963.7   55.73
#Mann= 3 , 1 , 0
 4029.70    0.14       0  4980.5    0.05       0  5019.6    0.14       0
Bank Sta=4980.50,5019.60
Exp/Cntr=0.3,0.1

Type RM Length L Ch R = 1 ,12351.9,731.9,731.9,731.9
XS GIS Cut Line= 3
   .710098563679   .203130181151   .725324288610   .153047988313
   .732461046501   .135073931402
BEGIN DESCRIPTION:
Sandy Run 12.0
END DESCRIPTION:
#Sta/Elev= 30
  3585.3   59.48  3625.3   55.28  3685.3    55.5  3925.3   51.34  3985.3   52.11
  4055.3   52.13  4065.3   51.26  4075.3   51.38  4085.3   52.33  4255.3   51.28
  4465.3   52.45  4625.3   52.62  4745.3   51.14  4865.3   48.17  4885.3   48.94
  4925.3   48.44  4975.3   49.32  4980.4   47.97  4984.4   39.97  5015.5   39.97
  5019.5   47.97  5020.9   48.97  5100.9   49.49  5110.9   48.98  5350.9   50.12
  5360.9   50.76  5370.9   52.25  5400.9   52.47  5460.9   56.04  5500.9   62.21
#Mann= 3 , 1 , 0
 3585.30    0.14       0  4980.4    0.05       0  5019.5    0.14       0
Bank Sta=4980.40,5019.50
Exp/Cntr=0.3,0.1

Type RM Length L Ch R = 1 ,11620.0,973.8,973.8,973.8
XS GIS Cut Line= 3
   .721705252947   .201410671630   .743298345521   .156748529442
   .749113481580   .140889067461
BEGIN DESCRIPTION:
Sandy Run 11.0
END DESCRIPTION:
#Sta/Elev= 30
  3483.1   61.39  3493.1   60.72  3513.1   57.96  3853.1   54.53  3993.1   51.59
  4183.1   52.27  4303.1   49.55  4413.1      50  4543.1   49.14  4563.1   50.25
  4843.1   52.02  4873.1   50.15  4913.1   50.12  4980.5   47.76  4984.5   39.76
  5015.6   39.76  5019.6   47.76  5026.9   48.76  5056.9   49.17  5146.9   49.27
  5156.9   49.85  5206.9   50.26  5216.9   49.82  5226.9   50.51  5276.9    49.2
  5296.9   50.02  5326.9   49.61  5376.9   50.83  5386.9   52.13  5426.9   61.08
#Mann= 3 , 1 , 0
 3483.10    0.14       0  4980.5    0.05       0  5019.6    0.14       0
Bank Sta=4980.50,5019.60
Exp/Cntr=0.3,0.1

Type RM Length L Ch R = 1 ,10646.2,858,858,858
XS GIS Cut Line= 3
   .734171696976   .217746012082   .758364834402   .177365830016
   .772565786948   .150674215320
BEGIN DESCRIPTION:
Sandy Run 10.0
END DESCRIPTION:
#Sta/Elev= 30
  3869.2   54.54  3879.2   54.01  3919.2   53.98  3989.2   52.62  3999.2   52.81
  4059.2   52.13  4089.2   51.96  4139.2   52.36  4209.2   50.76  4239.2   50.92
  4259.2   50.31  4469.2   50.27  4489.2    49.6  4549.2   49.24  4619.2   48.53
  4649.2   49.05  4749.2   49.35  4959.2    49.5  4980.5   47.49  4984.5   39.49
  5015.6   39.49  5019.6   47.49    5158   49.18    5188   48.89    5258   52.39
    5268   53.19    5298      53    5328   53.68    5348      53    5378   54.28
#Mann= 3 , 1 , 0
 3869.20    0.13       0  4980.5    0.05       0  5019.6    0.13       0
Bank Sta=4980.50,5019.60
Exp/Cntr=0.3,0.1

Type RM Length L Ch R = 1 ,9788.2,1199.7,1199.7,1199.7
XS GIS Cut Line= 3
   .757385075513   .234941107294   .778029088378   .189330597111
   .774068481515   .150054579054
BEGIN DESCRIPTION:
Sandy Run 8.0
END DESCRIPTION:
#Sta/Elev= 30
    3423    60.4    3493   59.65    3833   53.08    4013   51.47    4423   52.05
    4623   50.06    4663   50.25    4673   49.91    4693    47.6    4703   47.42
    4713   48.07    4783   47.82    4793   47.28    4843   48.64    4883   46.92
    4913   47.44  4980.4   46.47  4984.4   38.47  5015.5   38.47  5019.5   46.47
  5042.1   48.09  5112.1   48.68  5122.1    48.3  5172.1   49.98  5322.1   49.78
  5342.1    50.7  5732.1   52.31  5752.1   52.84  5792.1   56.23  5832.1   64.18
#Mann= 3 , 1 , 0
 3423.00    0.13       0  4980.4    0.05       0  5019.5    0.13       0
Bank Sta=4980.40,5019.50
Exp/Cntr=0.3,0.1

Type RM Length L Ch R = 1 ,8588.5,1107.4,1107.4,1107.4
XS GIS Cut Line= 3
   .825305701603   .240529513239   .810704094996   .192301052257
   .799385457970   .149384808059
BEGIN DESCRIPTION:
Sandy Run 7.0
END DESCRIPTION:
#Sta/Elev= 24
  3626.1   57.41  3856.1   51.18  3956.1   50.71  4226.1   50.04  4276.1   49.56
  4306.1   48.01  4496.1   47.94  4596.1   48.25  4616.1   49.12  4736.1   48.25
  4756.1   47.41  4776.1   47.83  4856.1      48  4980.1    45.4  4984.1    37.4
  5015.8    37.4  5019.8    45.4  5106.1   45.63  5126.1    46.8  5236.1   46.43
  5246.1   46.86  5256.1   47.98  5276.1   52.44  5316.1   63.37
#Mann= 3 , 1 , 0
 3626.10    0.13       0  4980.1    0.05       0  5019.8    0.13       0
Bank Sta=4980.10,5019.80
Exp/Cntr=0.3,0.1

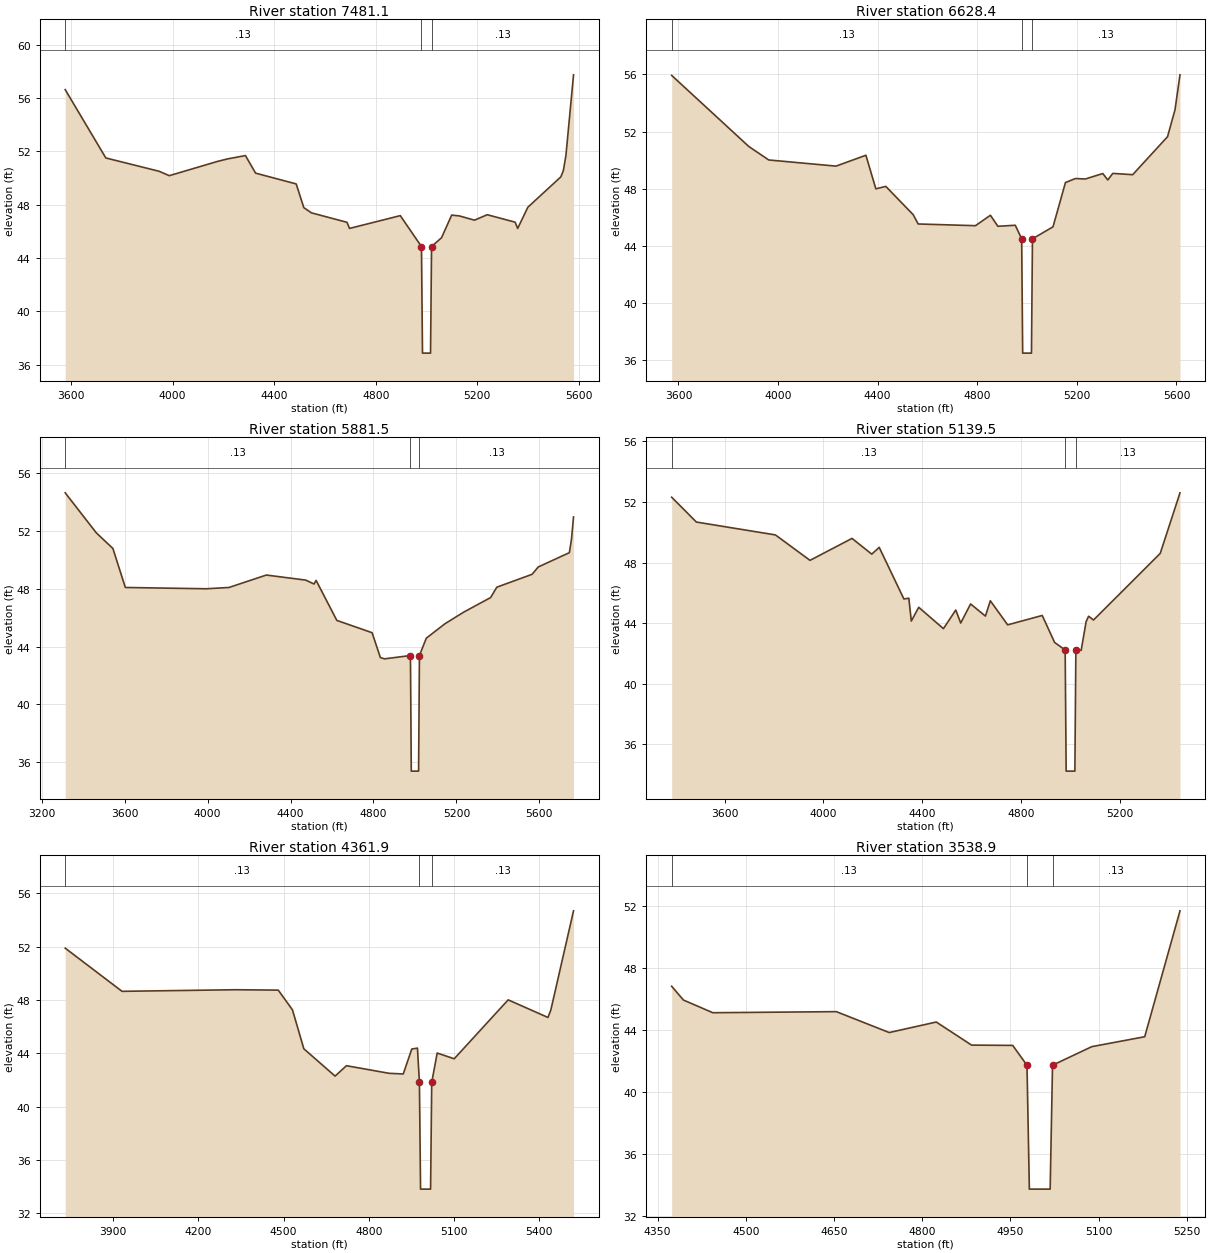
Type RM Length L Ch R = 1 ,7481.1,852.7,852.7,852.7
XS GIS Cut Line= 3
   .841563823468   .237451970493   .839451499808   .184643878990
   .834962812030   .152166902714
BEGIN DESCRIPTION:
Sandy Run 6.0
END DESCRIPTION:
#Sta/Elev= 30
  3576.6   56.64  3736.6   51.51  3946.6   50.51  3986.6   50.18  4176.6   51.25
  4216.6   51.44  4286.6   51.69  4326.6   50.37  4486.6   49.56  4516.6   47.78
  4546.6   47.39  4686.6   46.68  4696.6   46.22  4896.6   47.18  4980.1   44.86
  4984.1   36.86  5015.8   36.86  5019.8   44.86  5059.1   45.52  5099.1   47.22
  5129.1   47.16  5189.1   46.84  5239.1   47.25  5349.1   46.69  5359.1   46.22
  5399.1   47.81  5529.1   50.09  5539.1   50.57  5549.1   51.69  5579.1   57.75
#Mann= 3 , 1 , 0
 3576.60    0.13       0  4980.1    0.05       0  5019.8    0.13       0
Bank Sta=4980.10,5019.80
Exp/Cntr=0.3,0.1

Type RM Length L Ch R = 1 ,6628.4,746.9,746.9,746.9
XS GIS Cut Line= 3
   .859266014648   .223334418026   .862824295195   .181104226671
   .861277006482   .154542437101
BEGIN DESCRIPTION:
Sandy Run 5.0
END DESCRIPTION:
#Sta/Elev= 28
  3572.7   55.93  3882.7   50.95  3962.7   50.01  4232.7   49.58  4352.7   50.34
  4392.7   47.99  4432.7   48.16  4542.7   46.18  4562.7   45.53  4792.7   45.41
  4852.7   46.14  4882.7   45.37  4952.7   45.44  4978.3   44.49  4982.3   36.49
  5017.6   36.49  5021.6   44.49  5104.1   45.33  5154.1   48.43  5194.1   48.71
  5234.1   48.68  5304.1   49.06  5324.1   48.61  5344.1   49.07  5424.1   48.98
  5564.1   51.64  5594.1   53.53  5614.1   55.97
#Mann= 3 , 1 , 0
 3572.70    0.13       0  4978.3    0.05       0  5021.6    0.13       0
Bank Sta=4978.30,5021.60
Exp/Cntr=0.3,0.1

Type RM Length L Ch R = 1 ,5881.5,742,742,742
XS GIS Cut Line= 3
   .881433932554   .240884496441   .881907522653   .188067025879
   .878555063775   .154284555650
BEGIN DESCRIPTION:
Sandy Run 4.0
END DESCRIPTION:
#Sta/Elev= 28
  3313.3   54.64  3463.3   51.87  3543.3   50.79  3603.3   48.09  3993.3      48
  4103.3   48.09  4283.3   48.95  4473.3    48.6  4513.3   48.33  4523.3   48.58
  4623.3   45.81  4793.3   44.96  4833.3   43.24  4853.3   43.15  4978.3   43.38
  4982.3   35.38  5017.6   35.38  5021.6   43.38  5054.8   44.58  5144.8   45.58
  5234.8   46.38  5364.8   47.39  5394.8   48.11  5564.8      49  5594.8   49.51
  5744.8    50.5  5754.8   51.41  5764.8   52.97
#Mann= 3 , 1 , 0
 3313.30    0.13       0  4978.3    0.05       0  5021.6    0.13       0
Bank Sta=4978.30,5021.60
Exp/Cntr=0.3,0.1

Type RM Length L Ch R = 1 ,5139.5,777.6,777.6,777.6
XS GIS Cut Line= 3
   .898332521835   .240092375069   .900990750110   .191935247661
   .901764394467   .163568287926
BEGIN DESCRIPTION:
Sandy Run 3.0
END DESCRIPTION:
#Sta/Elev= 30
  3385.5   52.32  3485.5   50.68  3805.5   49.83  3945.5   48.15  4115.5    49.6
  4195.5   48.56  4225.5   49.01  4325.5    45.6  4345.5   45.65  4355.5   44.14
  4385.5   45.05  4485.5   43.64  4535.5   44.87  4555.5   44.01  4595.5   45.27
  4655.5   44.47  4675.5   45.48  4745.5   43.89  4885.5   44.51  4935.5   42.73
  4978.3   42.23  4982.3   34.23  5017.6   34.23  5021.6   42.23  5043.1   42.21
  5063.1    44.1  5073.1   44.46  5093.1   44.21  5363.1   48.61  5443.1   52.61
#Mann= 3 , 1 , 0
 3385.50    0.13       0  4978.3    0.05       0  5021.6    0.13       0
Bank Sta=4978.30,5021.60
Exp/Cntr=0.3,0.1

Type RM Length L Ch R = 1 ,4361.9,823,823,823
XS GIS Cut Line= 3
   .908399064278   .233227323173   .921621266281   .195545587991
   .932025943089   .164942584798
BEGIN DESCRIPTION:
Sandy Run 2.0
END DESCRIPTION:
#Sta/Elev= 23
  3731.4   51.89  3931.4   48.65  4331.4   48.77  4481.4   48.74  4531.4   47.26
  4571.4   44.34  4681.4   42.29  4721.4   43.07  4871.4    42.5  4921.4   42.45
  4951.4   44.32  4971.4   44.39  4978.3   41.81  4982.3   33.81  5017.6   33.81
  5021.6   41.81  5040.8   44.02  5100.8   43.59  5240.8   46.85  5290.8   48.01
  5430.8   46.69  5440.8   47.24  5520.8   54.69
#Mann= 3 , 1 , 0
 3731.40    0.13       0  4978.3    0.05       0  5021.6    0.13       0
Bank Sta=4978.30,5021.60
Exp/Cntr=0.3,0.1

Type RM Length L Ch R = 1 ,3538.9,0,0,0
XS GIS Cut Line= 3
   .917299460990   .230212456111   .943541189713   .196061350895
   .950000000000   .172079342690
BEGIN DESCRIPTION:
Sandy Run 1.0
END DESCRIPTION:
#Sta/Elev= 15
    4374   46.81    4394   45.92    4444    45.1    4654   45.17    4744   43.82
    4824    44.5    4884   43.01    4954   42.99  4978.3   41.71  4982.3   33.71
  5017.7   33.71  5021.7   41.71  5088.5   42.91  5178.5   43.55  5238.5   51.68
#Mann= 3 , 1 , 0
 4374.00    0.13       0  4978.3    0.05       0  5021.7    0.13       0
Bank Sta=4978.30,5021.70
Exp/Cntr=0.3,0.1

Chan Stop Cuts=-1