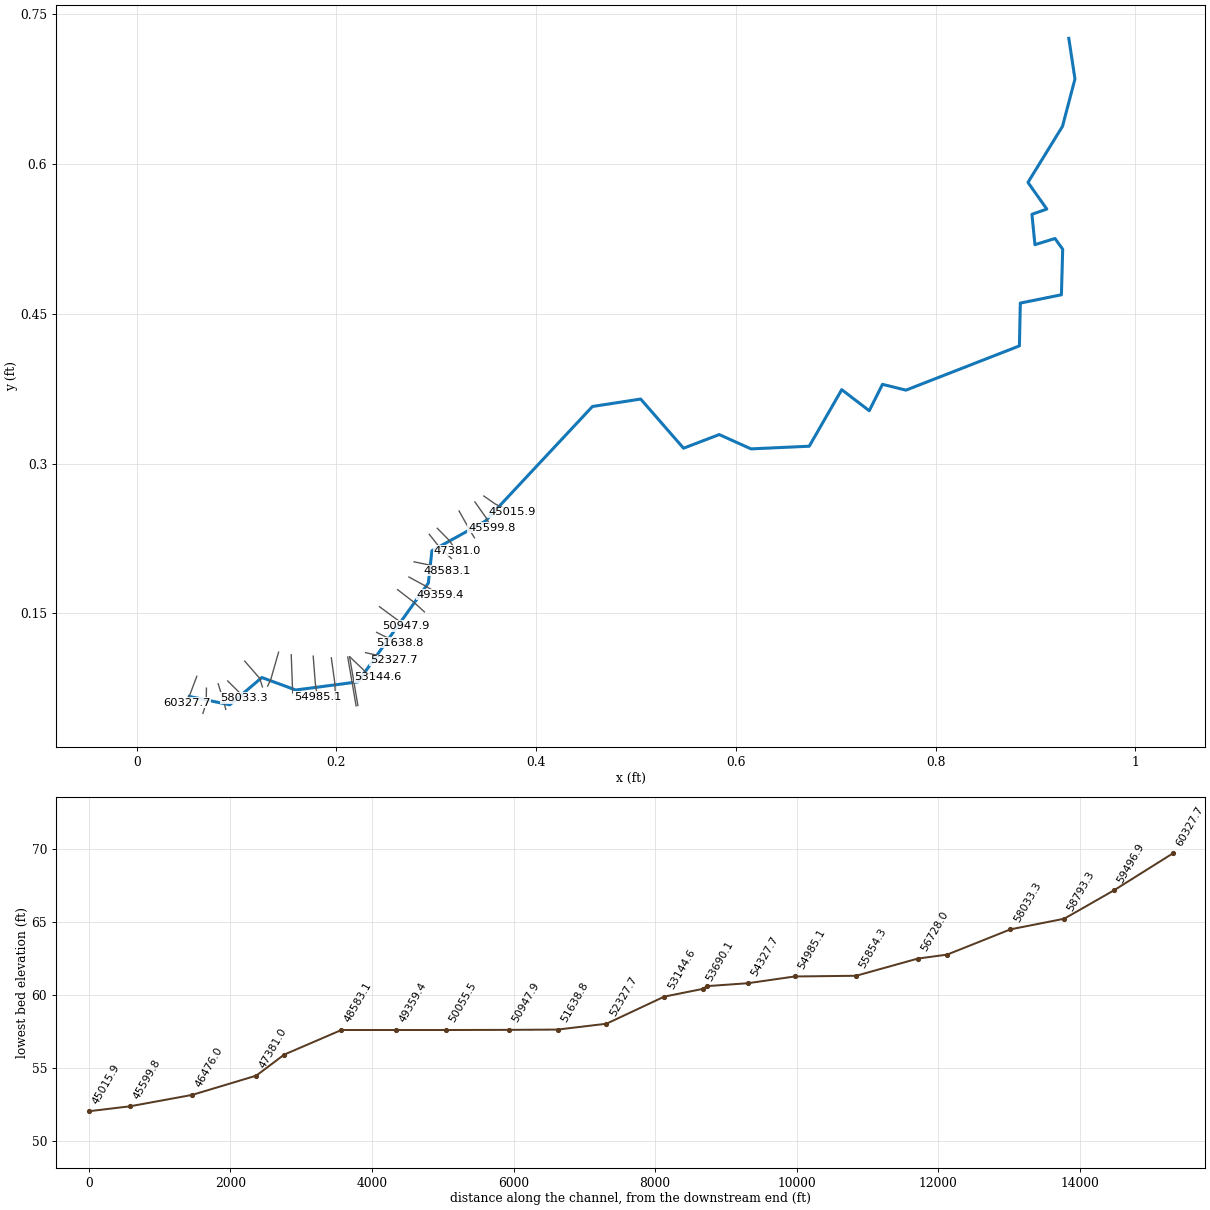
--- 2B CID37079C_DF_WHEAT SWAMP.PRJ (project) ---

Proj Title=Wheat Swamp
Current Plan=p01
Default Exp/Contr=0.3,0.1
English Units
Geom File=g01
Flow File=f02
Flow File=f01
Plan File=p02
Plan File=p01
Y Axis Title=Elevation
X Axis Title(PF)=Main Channel Distance
X Axis Title(XS)=Station
BEGIN DESCRIPTION:
####(Watershed Name)####
WHEAT SWAMP
HCFCD Unit X###-##-##
(Flood Hazard, Floodway) Model
10, 2, 1, 0.2% Event
Filename:  n:\NC_flood\60138\Approximates\Eng\Toisnot_Nahunta\ENG\Wheat Swamp\Wheat Swamp.prj
Prepared by:  ________     Date: ________
Reviewed by:  ________     Date: ________
STATUS (Draft RAS, SVSQ, FINAL)
END DESCRIPTION:
DSS Export Rating Curves= 0
DSS Export Rating Curve Sorted= 0
DSS Export Volume Flow Curves= 0
DXF OffsetX= 0
DXF OffsetY= 0
DXF ScaleX= 1
DXF ScaleY= 10

--- 2B CID37079C_DF_WHEAT SWAMP.p01 (plan) ---

Plan Title=100 Year Single
Version=Version 3.0.1  Mar 2001
Short Identifier=Plan01
Geom File=g01
Flow File=f01
Subcritical Flow
K Sum by GR= 0
Std Step Tol= 0.01
Critical Tol= 0.01
Num of Std Step Trials= 20
Max Error Tol= 0.3
Flow Tol Ratio= 0.001
Split Flow NTrial= 30
Split Flow Tol= 0.02
Split Flow Ratio= 0.02
Log Output Level= 0
Friction Slope Method= 1
Unsteady Friction Slope Method= 2
Parabolic Critical Depth
Global Vel Dist= 0 , 0 , 0
Global Log Level= 0
CheckData=True
Encroach Param=-1 ,10,10, 2
Encroach River=Wheat Swamp
Encroach Reach=Reach - 1
Encroach Node=60327.7
       4      .7
Encroach Node=59496.9
       4      .7
Encroach Node=58793.3
       1    4880    5040
Encroach Node=58033.3
       1    4970    5115
Encroach Node=57140.6
       1    4760    5015
Encroach Node=56728.0
       4      .7
Encroach Node=55854.3
       4      .7
Encroach Node=54985.1
       1    4790    5240
Encroach Node=54327.7
       1    4865    5180
Encroach Node=53750.1
       4      .7
Encroach Node=53720.1
       4      .7
Encroach Node=53690.1
       4      .7
Encroach Node=53144.6
       1    4925    5100
Encroach Node=52327.7
       4      .7
Encroach Node=51638.8
       4      .7
Encroach Node=50947.9
       4      .7
Encroach Node=50055.5
       4      .7
Encroach Node=49359.4
       4      .7
Encroach Node=48583.1
       4      .7
Encroach Node=47775.0
       4      .7
Encroach Node=47381.0
       4      .7
Encroach Node=46476.0
       4      .7
Encroach Node=45599.8
       4      .7
Encroach Node=45015.9
       4      .7
Encroach Node=44265.5
       4      .7
Encroach Node=43849.7
       4      .7
Encroach Node=43162.8
       1    4945    5290
Encroach Node=42287.9
       4      .7
Encroach Node=41730.2
       1    4780    5110
Encroach Node=40997.1
       4      .7
Encroach Node=40014.7
       4      .7
Encroach Node=39600.8
       1    4920    5100
Encroach Node=39577.3
       4      .7
Encroach Node=39553.8
       1    4920    5100
Encroach Node=39192.8
       4      .7
Encroach Node=38695.0
       4      .7
Encroach Node=37809.7
       4      .7
Encroach Node=36977.0
       1    4925    5300
Encroach Node=36534.2
       1    4930    5310
Encroach Node=35990.4
       4      .7
Encroach Node=35305.4
       4      .7
Encroach Node=34566.3
       4      .7
Encroach Node=33866.2
       4      .7
Encroach Node=33391.5
       4      .7
Encroach Node=32810.5
       4      .7
Encroach Node=32057.7
       1    4933    5400
Encroach Node=31304.9
       1    4945    5375
Encroach Node=30063.2
       4      .7
Encroach Node=29513.8
       1    4815    5025
Encroach Node=28873.3
       1    4915    5115
Encroach Node=28850.3
       4      .7
Encroach Node=28827.3
       1    4915    5115
Encroach Node=28579.9
       4      .7
Encroach Node=27905.6
       4      .7
Encroach Node=26916.9
       4      .7
Encroach Node=25770.1
       4      .7
Encroach Node=25225.1
       4      .7
Encroach Node=24452.5
       4      .7
Encroach Node=23860.9
       4      .7
Encroach Node=23185.9
       1    4917    5065
Encroach Node=22361.6
       4      .7
Encroach Node=21958.3
       1    4920    5055
Encroach Node=21286.9
       4      .7
Encroach Node=20539.5
       1    4810    5095
Encroach Node=20164.7
       1    4850    5230
Encroach Node=19440.9
       1    4960    5040
Encroach Node=19417.9
       4      .7
Encroach Node=19394.9
       1    4960    5040
Encroach Node=18904.9
       4      .7
Encroach Node=18251.7
       4      .7
Encroach Node=16897.2
       4      .7
Encroach Node=16485.7
       4      .7
Encroach Node=15941.0
       4      .7
Encroach Node=15313.0
       4      .7
Encroach Node=14060.0
       4      .7
Encroach Node=13465.4
       1    4780    5160
Encroach Node=12452.4
       1    4870    5070
Encroach Node=11891.6
       1    4866    5155
Encroach Node=11377.0
       1    4800    5280
Encroach Node=10619.8
       4      .7
Encroach Node=10124.5
       4      .7
Encroach Node=9409.8
       4      .7
Encroach Node=8710.2
       1    4720    5020
Encroach Node=8174.5
       4      .7
Encroach Node=7395.4
       4      .7
Encroach Node=6285.1
       4      .7
Encroach Node=5660.7
       1    4940    5115
Encroach Node=5638.2
       4      .7
Encroach Node=5615.7
       1    4940    5115
Encroach Node=5057.4
       1    4550    5107
Computation Interval=1HOUR
Output Interval=1HOUR
Run HTab= 0
Run UNet= 0
Run PostProcess= 0
UNET Theta= 1
UNET ZTol= 0.02
UNET ZSATol= 0.1
UNET MxIter= 20
UNET MaxInSteps= 20
UNET DtIC= 0
UNET DtMin= 0
UNET MaxCRTS= 20
UNET WFStab= 2
UNET SFStab= 1
UNET WFX= 1
UNET SFX= 1
UNET Convert EG Bridges=-1
UNET Use Existing IB Tables=-1
Instantaneous Interval=1HOUR
Write IC File= 0
Write Velocity= 0
Write Detailed= 0

--- 2B CID37079C_DF_WHEAT SWAMP.p02 (plan) ---

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Plan Title=Multi_Profile
Program Version=4.00
Short Identifier=Multi_Pro
Geom File=g01
Flow File=f02
Unsteady Bridges Friction Slope Method= 1
Run WQNet= 0
UNET Theta Warmup= 1
UNET DSS MLevel= 4
UNET DZMax Abort= 100
UNET Froude Reduction=False
UNET Froude Limit= 1
UNET Froude Power= 10
UNET Time Slicing=0,0, 5
Echo Input=False
Echo Output=False
Detailed Automatic Start=False, 10
WQ ULTIMATE=-1
WQ Max Comp Step=1HOUR
WQ Output Interval=15MIN
WQ Output Selected Increments= 0
WQ Output face flow=0
WQ Output face velocity=0
WQ Output face area=0
WQ Output face dispersion=0
WQ Output cell volume=0
WQ Output cell surface area=0
WQ Output cell continuity=0
WQ Output face conc=0
WQ Output face dconc_dx=0
WQ Output face courant=0
WQ Output face peclet=0
WQ Output face adv mass=0
WQ Output face disp mass=0
WQ Output cell mass=0
WQ Output cell source sink temp=0
WQ Output cell source sink nsm=0
WQ Output MaxMinRange=-1
WQ Daily Max Min Mean=-1
WQ Daily Range=0
WQ Daily Time=0
WQ Create Restart=0
WQ Fixed Restart=0
WQ System Summary=False
Sorting and Armoring Iterations= 10
XS Update Threshold= 0.02
Hydraulics Update Threshold= 0.02
Energy Slope Method= 1
Volume Change Method= 0
XS Weighting Method= 0
Number of US Weighted Cross Sections= 1
Number of DS Weighted Cross Sections= 1
Upstream XS Weight=0.25
Main XS Weight=0.5
Downstream XS Weight=0.25
Number of DS XS's Weighted with US Boundary= 1
Upstream Boundary Weight= 1
Weight of XSs Associated with US Boundary= 0
Number of US XS's Weighted with DS Boundary= 1
Downstream Boundary Weight= 0.5
Weight of XSs Associated with DS Boundary= 0.5
Sediment Output Level= 4
Mass or Volume Output= 0
Output Increment Type= 1
Profile and TS Output Increment= 10
XS Output Flag= 0
XS Output Increment= 10
Disregard all LS=0
Disregard all Conn=0
Disregard all Breaches=0
Disregard all Pumps=0

--- 2B CID37079C_DF_WHEAT SWAMP.f01 (steady flow) ---

Flow Title= 100 Year Single
Version=Version 3.0.1  Mar 2001
Number of Profiles= 2
Profile Names=100-Year,AFW
River Rch & RM=Wheat Swamp,Reach - 1       ,60327.7
    1148    1148
River Rch & RM=Wheat Swamp,Reach - 1       ,59496.9
    1238    1238
River Rch & RM=Wheat Swamp,Reach - 1       ,56728
    1471    1471
River Rch & RM=Wheat Swamp,Reach - 1       ,54985.1
    1611    1611
River Rch & RM=Wheat Swamp,Reach - 1       ,47775
    1778    1778
River Rch & RM=Wheat Swamp,Reach - 1       ,40997.1
    2059    2059
River Rch & RM=Wheat Swamp,Reach - 1       ,34566.3
    2222    2222
River Rch & RM=Wheat Swamp,Reach - 1       ,31304.9
    2454    2454
River Rch & RM=Wheat Swamp,Reach - 1       ,21286.9
    2583    2583
River Rch & RM=Wheat Swamp,Reach - 1       ,16897.2
    2886    2886
River Rch & RM=Wheat Swamp,Reach - 1       ,13465.4
    3035    3035
Boundary for River Rch & Prof#=Wheat Swamp,Reach - 1       , 1
Up Type= 0
Dn Type= 3
Dn Slope=.0002
DSS Import GetInterval= 0
DSS Import GetPeak= 0
DSS Import FillOption= 0

--- 2B CID37079C_DF_WHEAT SWAMP.f02 (steady flow) ---

Flow Title=Multi_Profile
Program Version=3.13
Number of Profiles= 7
Profile Names=10-yr,25-yr,50-yr,500-yr,100-yr-10%,100-yr-20%,100-yr-35%
River Rch & RM=Wheat Swamp,Reach - 1       ,60327.7
     498     719     919    1816    1970    2525    3085
River Rch & RM=Wheat Swamp,Reach - 1       ,59496.9
     541     779     993    1953    2120    2717    3320
River Rch & RM=Wheat Swamp,Reach - 1       ,56728
     653     933    1185    2301    2504    3210    3922
River Rch & RM=Wheat Swamp,Reach - 1       ,54985.1
     720    1026    1300    2508    2733    3503    4280
River Rch & RM=Wheat Swamp,Reach - 1       ,47775
     802    1138    1438    2756    3007    3854    4709
River Rch & RM=Wheat Swamp,Reach - 1       ,40997.1
     940    1327    1670    3169    3465    4441    5426
River Rch & RM=Wheat Swamp,Reach - 1       ,34566.3
    1022    1437    1806    3408    3731    4781    5842
River Rch & RM=Wheat Swamp,Reach - 1       ,31304.9
    1138    1595    1999    3745    4106    5262    6429
River Rch & RM=Wheat Swamp,Reach - 1       ,21286.9
    1203    1683    2107    3933    4314    5529    6756
River Rch & RM=Wheat Swamp,Reach - 1       ,16897.2
    1357    1890    2360    4371    4802    6155    7520
River Rch & RM=Wheat Swamp,Reach - 1       ,13465.4
    1434    1993    2485    4586    5042    6462    7896
Boundary for River Rch & Prof#=Wheat Swamp,Reach - 1       , 1
Up Type= 0
Dn Type= 3
Dn Slope=0.0002
DSS Import GetInterval= 0
DSS Import GetPeak= 0
DSS Import FillOption= 0

--- 2B CID37079C_DF_WHEAT SWAMP.g01 (geometry) ---

Geom Title=Geom 01 by CodeH2 for Windows

River Reach=Wheat Swamp,Reach - 1
Reach XY= 30
   .052596807279   .066988321365   .093121323661   .058584765074
   .125305077762   .085883775074   .159279894388   .073401090082
   .221476783289   .081541917800   .292031654640   .180427129455
   .295613470354   .212801125948   .349018067344   .242379641949
   .456369838813   .357221395618   .504672846308   .364656625130
   .547602666226   .315431174033   .583314102026   .329107900709
   .615172433367   .314779709840   .673457753073   .317432276534
   .706012402505   .374056146012   .733550530178   .352975432885
   .746839038638   .379392831796   .770321136633   .373575745303
   .883942554954   .417871289064   .884849531695   .460726249373
   .925996641191   .469025148413   .927287505426   .514623311223
   .919586864577   .525388865285   .899482110391   .519184179250
   .896492984798   .549605329849   .911381076042   .554821992791
   .892507174669   .581520888577   .927089838940   .637673946800
   .939574689292   .685093177846   .933405758284   .725757326713

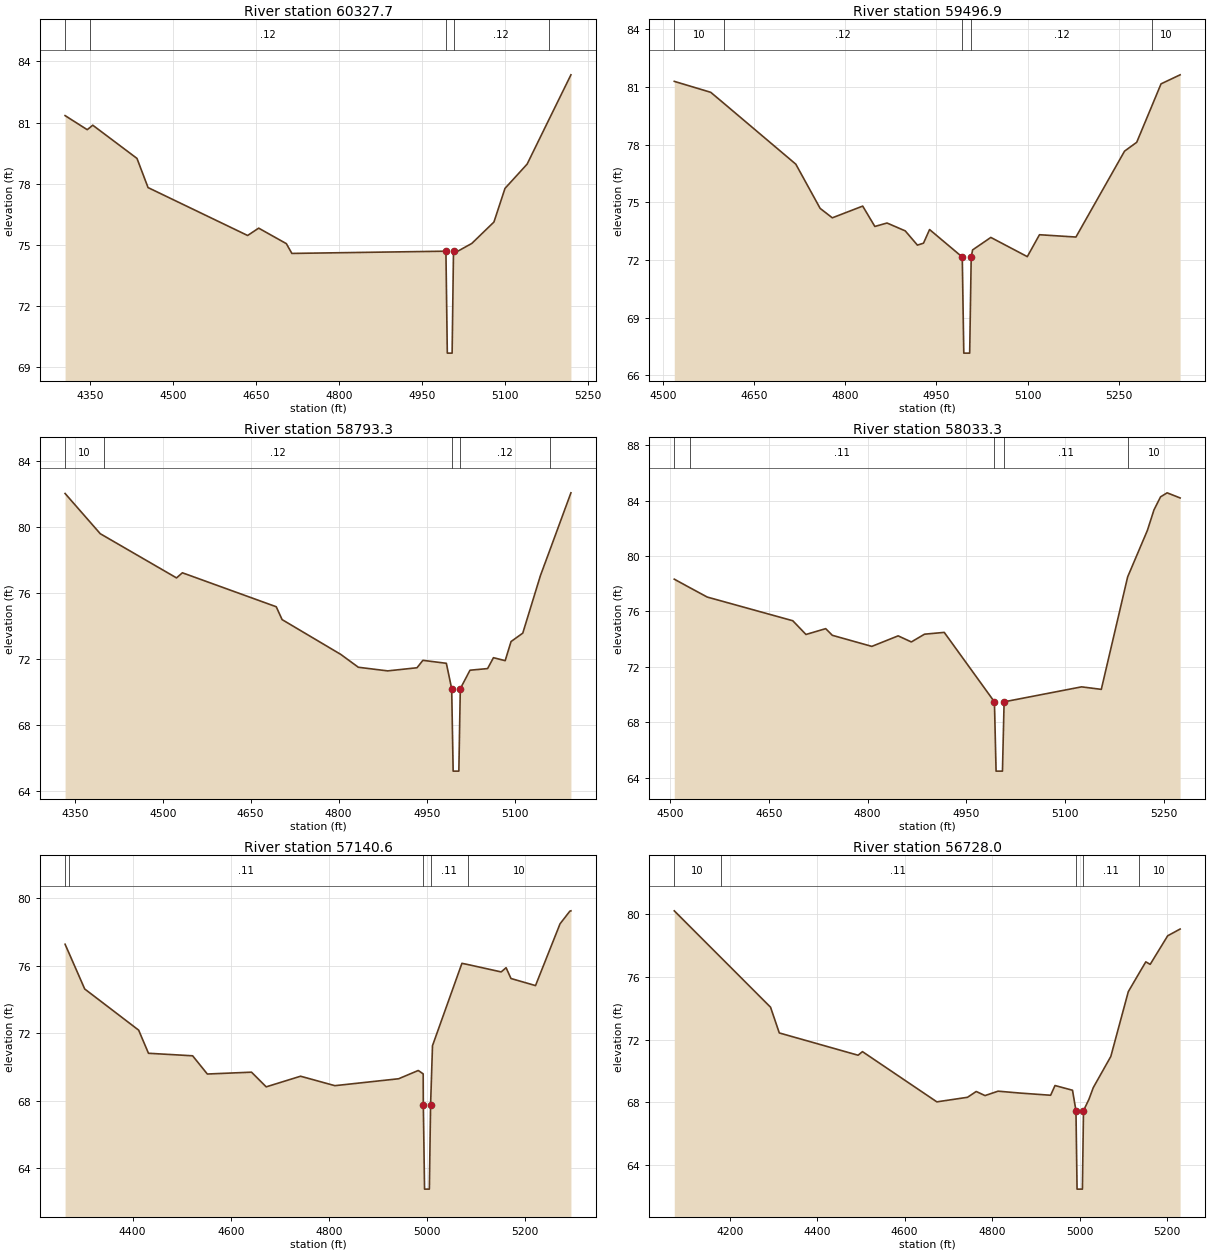
Type RM Length L Ch R = 1 ,60327.7,830.8,830.8,830.8
XS GIS Cut Line= 3
   .060137670713   .087132165982   .052594844392   .066989229076
   .050000000000   .060727070172
BEGIN DESCRIPTION:
Wheat Swamp 74.0
END DESCRIPTION:
#Sta/Elev= 21
  4304.7   81.34  4344.7   80.65  4349.9   80.76  4354.7   80.87  4434.7   79.24
  4454.7   77.81  4634.7   75.46  4654.7   75.82  4704.7   75.06  4714.7   74.58
  4993.2   74.69  4995.7   69.69  5004.4   69.69  5006.9   74.69    5010   74.62
    5040   75.07    5080   76.12    5100   77.77    5140   78.96  5179.9   81.17
  5219.2   83.34
#Mann= 5 , 1 , 0
 4304.70      10       0  4349.9    0.12       0  4993.2   0.041       0
  5006.9    0.12       0  5179.9      10       0
Bank Sta=4993.20,5006.90
Exp/Cntr=0.3,0.1

Type RM Length L Ch R = 1 ,59496.9,703.6,703.6,703.6
XS GIS Cut Line= 3
   .069803821857   .075226296889   .069576219168   .060354344664
   .066267425097   .050000000000
BEGIN DESCRIPTION:
Wheat Swamp 73.0
END DESCRIPTION:
#Sta/Elev= 27
  4518.8    81.3  4578.8   80.73  4599.9   80.17  4718.8   76.99  4758.8   74.69
  4778.8    74.2  4828.8   74.81  4848.8   73.75  4868.8   73.93  4898.8   73.52
  4918.8   72.78  4928.8   72.88  4938.8   73.59  4992.6   72.16  4995.1   67.16
  5004.8   67.16  5007.3   72.16  5009.6   72.53  5039.6   73.18  5099.6   72.18
  5119.6   73.32  5179.6    73.2  5259.6   77.67  5279.6   78.13  5304.9   80.05
  5319.6   81.17    5351   81.64
#Mann= 5 , 1 , 0
 4518.80      10       0  4599.9    0.12       0  4992.6   0.041       0
  5007.3    0.12       0  5304.9      10       0
Bank Sta=4992.60,5007.30
Exp/Cntr=0.3,0.1

Type RM Length L Ch R = 1 ,58793.3,760,760,760
XS GIS Cut Line= 3
   .081591811057   .079587852893   .087697086648   .059773547630
   .089136124146   .054007916328
BEGIN DESCRIPTION:
Wheat Swamp 72.0
END DESCRIPTION:
#Sta/Elev= 26
  4333.6   82.05  4393.6   79.61  4399.9   79.48  4523.6   76.93  4533.6   77.24
  4693.6   75.18  4703.6    74.4  4803.6   72.29  4833.6   71.51  4883.6   71.29
  4933.6   71.48  4943.6   71.93  4983.6   71.75  4992.7   70.21  4995.2   65.21
  5004.9   65.21  5007.4   70.21  5023.9   71.33  5053.9   71.43  5063.9   72.09
  5083.9   71.91  5093.9   73.07  5113.9   73.58  5143.9   77.06  5159.9    78.6
    5196   82.09
#Mann= 5 , 1 , 0
 4333.60      10       0  4399.9    0.12       0  4992.7   0.041       0
  5007.4    0.12       0  5159.9      10       0
Bank Sta=4992.70,5007.40
Exp/Cntr=0.3,0.1

Type RM Length L Ch R = 1 ,58033.3,892.7,892.7,892.7
XS GIS Cut Line= 3
   .091140082310   .082416970302   .102102912266   .071572020237
   .107761147083   .065442265853
BEGIN DESCRIPTION:
Wheat Swamp 71.0
END DESCRIPTION:
#Sta/Elev= 24
  4506.4   78.33  4529.9   77.72  4556.4   77.04  4686.4   75.33  4706.4   74.34
  4736.4   74.76  4746.4   74.28  4806.4   73.48  4846.4   74.24  4866.4    73.8
  4886.4   74.36  4916.4   74.49  4992.6   69.48  4995.1   64.48  5004.8   64.48
  5007.3   69.48  5124.9   70.56  5154.9   70.38  5194.9   78.49  5224.9   81.85
  5234.9   83.33  5244.9   84.27  5254.9   84.56  5274.6   84.19
#Mann= 5 , 1 , 0
 4506.40      10       0  4529.9    0.11       0  4992.6   0.041       0
  5007.3    0.11       0  5194.9      10       0
Bank Sta=4992.60,5007.30
Exp/Cntr=0.3,0.1

Type RM Length L Ch R = 1 ,57140.6,412.6,412.6,412.6
XS GIS Cut Line= 3
   .108114786759   .102338672050   .123125705758   .085096298338
   .125913531524   .076500502227
BEGIN DESCRIPTION:
Wheat Swamp 70.0
END DESCRIPTION:
#Sta/Elev= 28
  4262.3   77.26  4269.9   76.76  4302.3   74.61  4412.3   72.17  4432.3    70.8
  4522.3   70.65  4552.3   69.57  4642.3   69.68  4672.3   68.81  4742.3   69.44
  4812.3   68.88  4942.3   69.29  4982.3   69.78  4992.3   69.58  4992.6   67.75
  4995.1   62.75  5004.9   62.75  5007.4   67.75  5011.3   71.25  5071.3   76.13
  5082.9   76.06  5151.3   75.62  5161.3   75.87  5171.3   75.23  5221.3   74.81
  5271.3   78.47  5291.3   79.22  5293.5   79.24
#Mann= 5 , 1 , 0
 4262.30      10       0  4269.9    0.11       0  4992.6   0.041       0
  5007.4    0.11       0  5082.9      10       0
Bank Sta=4992.60,5007.40
Exp/Cntr=0.3,0.1

Type RM Length L Ch R = 1 ,56728.0,873.7,873.7,873.7
XS GIS Cut Line= 3
   .142064195656   .111297543843   .134166242892   .083713649114
   .131101365700   .077348134945
BEGIN DESCRIPTION:
Wheat Swamp 69.0
END DESCRIPTION:
#Sta/Elev= 28
  4073.5   80.21  4179.9   77.24  4293.5   74.07  4313.5   72.43  4493.5   71.01
  4503.5   71.24  4673.5   68.04  4743.5   68.33  4763.5    68.7  4783.5   68.44
  4813.5   68.72  4863.5    68.6  4933.5   68.46  4943.5   69.08  4983.5   68.78
  4991.4   67.48  4993.9   62.48  5006.1   62.48  5008.6   67.48    5021    68.2
    5031   68.95    5071   70.93    5111   75.06  5134.9    76.2    5151   76.96
    5161    76.8    5201   78.62  5229.4   79.05
#Mann= 5 , 1 , 0
 4073.50      10       0  4179.9    0.11       0  4991.4   0.041       0
  5008.6    0.11       0  5134.9      10       0
Bank Sta=4991.40,5008.60
Exp/Cntr=0.3,0.1

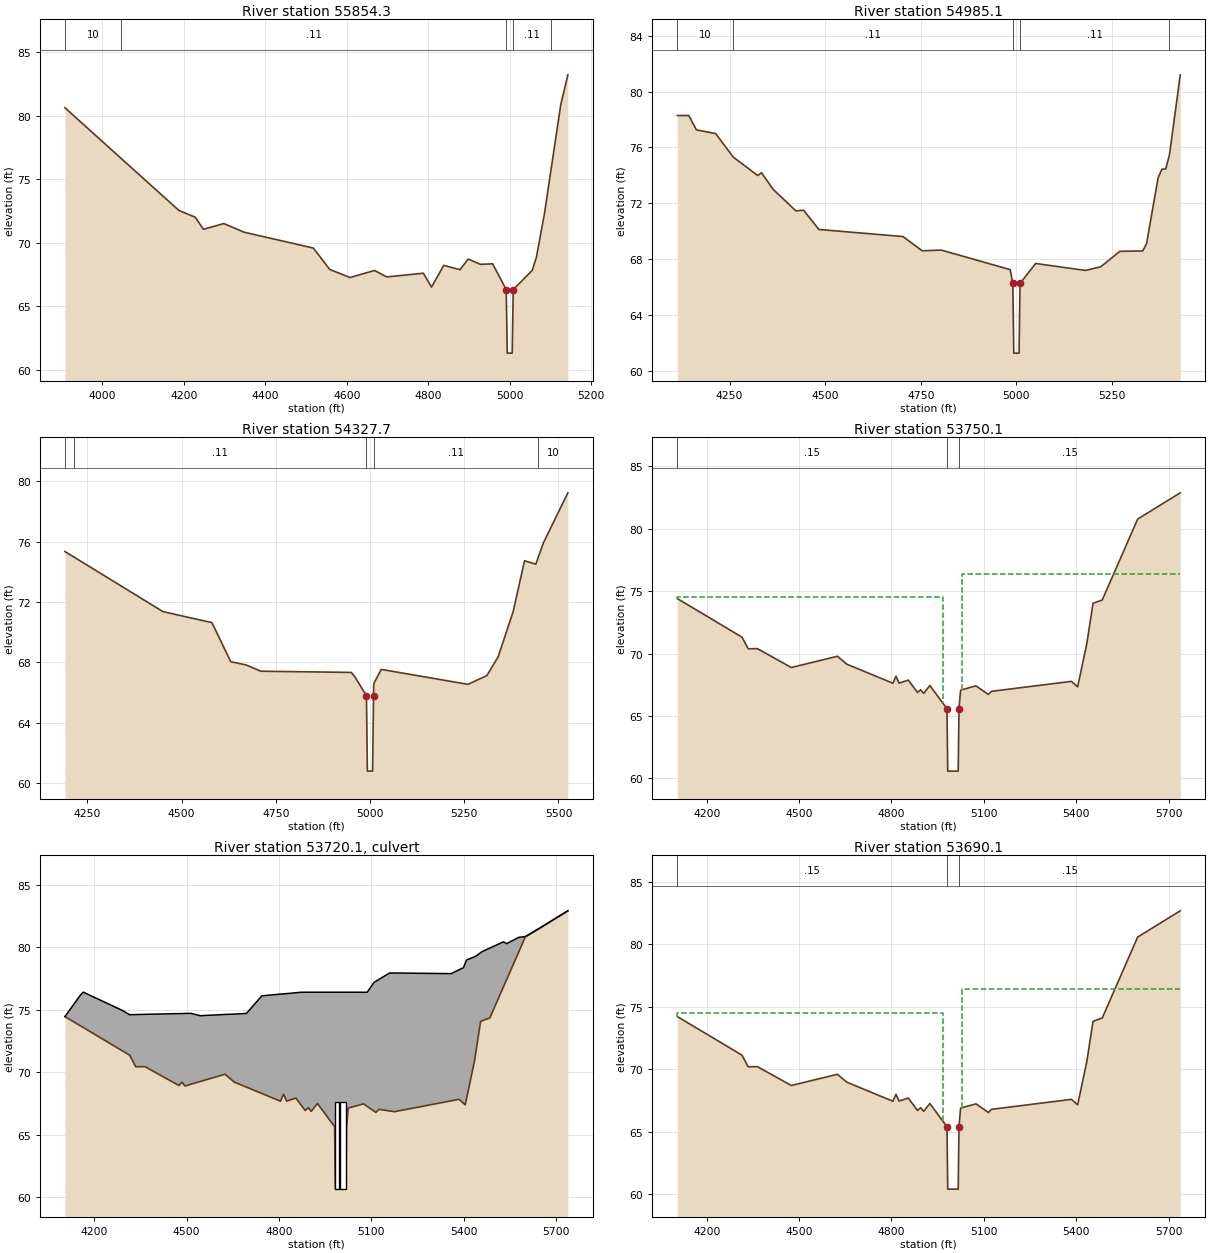
Type RM Length L Ch R = 1 ,55854.3,869.2,869.2,869.2
XS GIS Cut Line= 3
   .154721064440   .108676657943   .155998817916   .074758111123
   .156209782697   .070511101209
BEGIN DESCRIPTION:
Wheat Swamp 68.0
END DESCRIPTION:
#Sta/Elev= 29
    3908   80.62  4044.9   76.66    4188   72.53    4228      72    4248   71.05
    4298    71.5    4348   70.82    4518   69.57    4558   67.89    4608   67.25
    4668   67.81    4698    67.3    4788   67.59    4808    66.5    4838   68.21
    4878   67.87    4898   68.71    4928   68.29    4958   68.33  4991.4    66.3
  4993.9    61.3  5006.1    61.3  5008.6    66.3  5055.3   67.82  5065.3   68.83
  5085.3   72.29  5100.9   75.64  5125.3   80.87  5142.7   83.21
#Mann= 5 , 1 , 0
 3908.00      10       0  4044.9    0.11       0  4991.4   0.041       0
  5008.6    0.11       0  5100.9      10       0
Bank Sta=4991.40,5008.60
Exp/Cntr=0.3,0.1

Type RM Length L Ch R = 1 ,54985.1,657.4,657.4,657.4
XS GIS Cut Line= 3
   .176720883905   .107289627514   .178842721962   .079941492569
   .180846680126   .066856824557
BEGIN DESCRIPTION:
Wheat Swamp 67.0
END DESCRIPTION:
#Sta/Elev= 30
  4113.6   78.29  4143.6   78.29  4163.6   77.26  4213.6      77  4259.9   75.31
  4323.6   73.99  4333.6   74.19  4363.6   73.01  4423.6   71.45  4443.6    71.5
  4483.6   70.12  4703.6   69.61  4753.6   68.59  4803.6   68.64  4983.6   67.24
  4990.6   66.25  4993.1   61.25  5006.9   61.25  5009.4   66.25  5050.3   67.68
  5180.3   67.18  5220.3   67.44  5270.3   68.55  5330.3   68.58  5340.3   69.11
  5370.3   73.82  5380.3   74.44  5390.3   74.46  5399.9   75.45  5428.3   81.21
#Mann= 5 , 1 , 0
 4113.60      10       0  4259.9    0.11       0  4990.6   0.041       0
  5009.4    0.11       0  5399.9      10       0
Bank Sta=4990.60,5009.40
Exp/Cntr=0.3,0.1

Type RM Length L Ch R = 1 ,54327.7,577.6,577.6,577.6
XS GIS Cut Line= 3
   .194874387274   .105639309026   .198301769598   .080836504802
   .199118063387   .064617106609
BEGIN DESCRIPTION:
Wheat Swamp 66.0
END DESCRIPTION:
#Sta/Elev= 25
  4190.6   75.34  4214.9   74.97  4450.6   71.36  4580.6   70.63  4630.6   68.04
  4670.6   67.83  4710.6   67.41  4950.6   67.33  4960.6   67.01  4990.5   65.79
  4990.6   65.79  4993.1   60.79  5006.9   60.79  5009.4   65.79    5010   66.59
    5030   67.53    5260   66.54    5310   67.12    5340   68.36    5380   71.37
    5410   74.73    5440    74.5  5444.9   74.85    5460   75.91    5525   79.23
#Mann= 5 , 1 , 0
 4190.60      10       0  4214.9    0.11       0  4990.5   0.041       0
  5009.4    0.11       0  5444.9      10       0
Bank Sta=4990.50,5009.40
Exp/Cntr=0.5,0.3

Type RM Length L Ch R = 1 ,53750.1,60,60,60
XS GIS Cut Line= 3
   .211312537191   .106391444110   .215842754061   .080023258739
   .219676014489   .057488333797
BEGIN DESCRIPTION:
Upstream Section of Bridge/Culvert/Weir
END DESCRIPTION:
#Sta/Elev= 30
  4104.9   74.41  4314.9   71.32  4334.9   70.39  4364.9    70.4  4474.9   68.89
  4624.9   69.79  4654.9   69.16  4804.9   67.63  4814.9   68.19  4824.9   67.64
  4854.9   67.88  4884.9   66.89  4894.9   67.11  4904.9   66.82  4924.9   67.45
  4980.5   65.59    4983   60.59    5017   60.59  5019.5   65.59  5024.8   67.08
  5074.8   67.42  5114.8   66.73  5124.8   66.98  5384.8   67.78  5404.8   67.34
  5434.8   70.83  5454.8   74.03  5484.8    74.3  5599.8   80.78  5738.1   82.88
#Mann= 3 , 1 , 0
 4104.90    0.15       0  4980.5    0.05       0  5019.5    0.15       0
#XS Ineff= 2 , 0
       0    4968    74.5    5030       0    76.4
Bank Sta=4980.50,5019.50
Exp/Cntr=0.5,0.3

Type RM Length L Ch R = 2 ,53720.1,,,
BEGIN DESCRIPTION:
Sugg Rd-TOR
Structure ID: Sugg Rd-Assumed
Approximate Survey Structure
END DESCRIPTION:
Bridge Culvert--1,0,-1,-1, 0
Deck Dist Width WeirC Skew NumUp NumDn MinLoCord MaxHiCord MaxSubmerge Is_Ogee
10,40,3,,57,57,,,0.95,0,1,1,,
  4104.9  4154.2  4164.2  4294.2  4314.2  4314.9  4334.9  4364.9  4474.9  4484.9
  4494.9  4514.2  4544.2  4624.9  4654.9  4694.2  4744.2  4804.9  4814.9  4824.9
  4854.9  4873.1  4884.9  4894.9  4904.9  4924.9  4980.5    4983    5000    5017
  5019.5  5024.8  5074.8  5086.4  5109.1  5114.8  5124.8  5159.1  5174.8  5359.1
  5384.8  5399.1  5404.8  5409.1  5434.8  5439.1  5454.8  5459.1  5484.8  5529.1
  5539.1  5579.1  5599.8  5649.1  5659.1  5689.1  5738.1
   74.45   76.14   76.41   74.91    74.6    74.6   74.61   74.63   74.69   74.69
    74.7   74.71   74.52   74.62   74.65    74.7   76.11   76.25   76.27   76.29
   76.36    76.4    76.4    76.4    76.4    76.4    76.4    76.4    76.4    76.4
    76.4    76.4    76.4    76.4    77.2   77.28   77.43   77.94   77.94   77.89
    78.2   78.37   78.72   78.98   79.24   79.28   79.57   79.65   79.94   80.44
   80.29    80.8   80.86   81.57   81.72   82.18   82.92
   74.45   73.72   73.58   71.66   71.37   71.36   70.43   70.44   68.93   69.19
   68.89   69.03   69.25   69.83    69.2    68.8   68.29   67.67   68.23   67.68
   67.92   67.32   66.93   67.15   66.86   67.49   65.63   60.63   60.63   60.63
   65.63   67.12   67.46   67.26   66.87   66.77   67.02   66.89   66.83    67.7
   67.82   67.51   67.38   67.88   70.87   71.56   74.07   74.11   74.34   76.84
    77.4   79.65   80.82   81.57   81.72   82.18   82.92
  4104.9  4154.2  4164.2  4294.2  4314.2  4314.9  4334.9  4364.9  4474.9  4484.9
  4494.9  4514.2  4544.2  4624.9  4654.9  4694.2  4744.2  4804.9  4814.9  4824.9
  4854.9  4873.1  4884.9  4894.9  4904.9  4924.9  4980.5    4983    5000    5017
  5019.5  5024.8  5074.8  5086.4  5109.1  5114.8  5124.8  5159.1  5174.8  5359.1
  5384.8  5399.1  5404.8  5409.1  5434.8  5439.1  5454.8  5459.1  5484.8  5529.1
  5539.1  5579.1  5599.8  5649.1  5659.1  5689.1  5738.1
   74.35   76.14   76.41   74.91    74.6    74.6   74.61   74.63   74.69   74.69
    74.7   74.71   74.52   74.62   74.65    74.7   76.11   76.25   76.27   76.29
   76.36    76.4    76.4    76.4    76.4    76.4    76.4    76.4    76.4    76.4
    76.4    76.4    76.4    76.4    77.2   77.28   77.43   77.94   77.94   77.89
    78.2   78.37   78.72   78.98   79.24   79.28   79.57   79.65   79.94   80.44
   80.29    80.8   80.86   81.48   81.63   82.09   82.82
   74.25   73.52   73.38   71.46   71.17   71.16   70.23   70.24   68.73   68.99
   68.69   68.83   69.05   69.63      69    68.6   68.09   67.47   68.03   67.48
   67.72   67.12   66.73   66.95   66.66   67.29   65.43   60.43   60.43   60.43
   65.43   66.92   67.26   67.06   66.67   66.57   66.82   66.69   66.63    67.5
   67.62   67.31   67.18   67.68   70.67   71.36   73.87   73.91   74.14   76.64
    77.2   79.45   80.62   81.37   81.52   81.98   82.72
BR Coef= 1 , 0 , 0 ,1.25, 0 ,,,0.8,-1,2,0,
Wspro=,,,, 1 ,,,, 0 ,,,, 0 ,,,,-1 ,-1 ,-1 , 0 , 0 , 0 , 0 , 0
Culvert=2,7.0,13.0,40.0,0.015,0.4,1.0,8,1,60.63,4989.53,60.43,4989.53,Culvert #1  ,0,10
Culvert=2,7.0,20.0,40.0,0.015,0.4,1.0,8,1,60.63,5007.03,60.43,5007.03,Culvert #2  ,0,10
BC Design=,, 0 ,, 0 ,,,,,,
BR U #Sta/Elev= 57
  4104.9   74.45  4154.2   73.72  4164.2   73.58  4294.2   71.66  4314.2   71.37
  4314.9   71.36  4334.9   70.43  4364.9   70.44  4474.9   68.93  4484.9   69.19
  4494.9   68.89  4514.2   69.03  4544.2   69.25  4624.9   69.83  4654.9    69.2
  4694.2    68.8  4744.2   68.29  4804.9   67.67  4814.9   68.23  4824.9   67.68
  4854.9   67.92  4873.1   67.32  4884.9   66.93  4894.9   67.15  4904.9   66.86
  4924.9   67.49  4980.5   65.63    4983   60.63    5000   60.63    5017   60.63
  5019.5   65.63  5024.8   67.12  5074.8   67.46  5086.4   67.26  5109.1   66.87
  5114.8   66.77  5124.8   67.02  5159.1   66.89  5174.8   66.83  5359.1    67.7
  5384.8   67.82  5399.1   67.51  5404.8   67.38  5409.1   67.88  5434.8   70.87
  5439.1   71.56  5454.8   74.07  5459.1   74.11  5484.8   74.34  5529.1   76.84
  5539.1    77.4  5579.1   79.65  5599.8   80.82  5649.1   81.57  5659.1   81.72
  5689.1   82.18  5738.1   82.92
BR U #Mann= 3
 4104.90    0.15  4980.5    0.05  5019.5    0.15
BR U Banks=4980.50,5019.50
BR D #Sta/Elev= 57
  4104.9   74.25  4154.2   73.52  4164.2   73.38  4294.2   71.46  4314.2   71.17
  4314.9   71.16  4334.9   70.23  4364.9   70.24  4474.9   68.73  4484.9   68.99
  4494.9   68.69  4514.2   68.83  4544.2   69.05  4624.9   69.63  4654.9      69
  4694.2    68.6  4744.2   68.09  4804.9   67.47  4814.9   68.03  4824.9   67.48
  4854.9   67.72  4873.1   67.12  4884.9   66.73  4894.9   66.95  4904.9   66.66
  4924.9   67.29  4980.5   65.43    4983   60.43    5000   60.43    5017   60.43
  5019.5   65.43  5024.8   66.92  5074.8   67.26  5086.4   67.06  5109.1   66.67
  5114.8   66.57  5124.8   66.82  5159.1   66.69  5174.8   66.63  5359.1    67.5
  5384.8   67.62  5399.1   67.31  5404.8   67.18  5409.1   67.68  5434.8   70.67
  5439.1   71.36  5454.8   73.87  5459.1   73.91  5484.8   74.14  5529.1   76.64
  5539.1    77.2  5579.1   79.45  5599.8   80.62  5649.1   81.37  5659.1   81.52
  5689.1   81.98  5738.1   82.72
BR D #Mann= 3
 4104.90    0.15  4980.5    0.05  5019.5    0.15
BR D Banks=4980.50,5019.50

Type RM Length L Ch R = 1 ,53690.1,545.5,545.5,545.5
XS GIS Cut Line= 3
   .213127404540   .106780133127   .217657621410   .080411947756
   .221490881839   .057877022814
BEGIN DESCRIPTION:
Downstream Section of Bridge/Culvert/Weir
END DESCRIPTION:
#Sta/Elev= 30
  4104.9   74.22  4314.9   71.13  4334.9    70.2  4364.9   70.21  4474.9    68.7
  4624.9    69.6  4654.9   68.97  4804.9   67.44  4814.9      68  4824.9   67.45
  4854.9   67.69  4884.9    66.7  4894.9   66.92  4904.9   66.63  4924.9   67.26
  4980.5    65.4    4983    60.4    5017    60.4  5019.5    65.4  5024.8   66.89
  5074.8   67.23  5114.8   66.54  5124.8   66.79  5384.8   67.59  5404.8   67.15
  5434.8   70.64  5454.8   73.84  5484.8   74.11  5599.8   80.59  5738.1   82.69
#Mann= 3 , 1 , 0
 4104.90    0.15       0  4980.5    0.05       0  5019.5    0.15       0
#XS Ineff= 2 , 0
       0    4968    74.5    5030       0    76.4
Bank Sta=4980.50,5019.50
Exp/Cntr=0.5,0.3

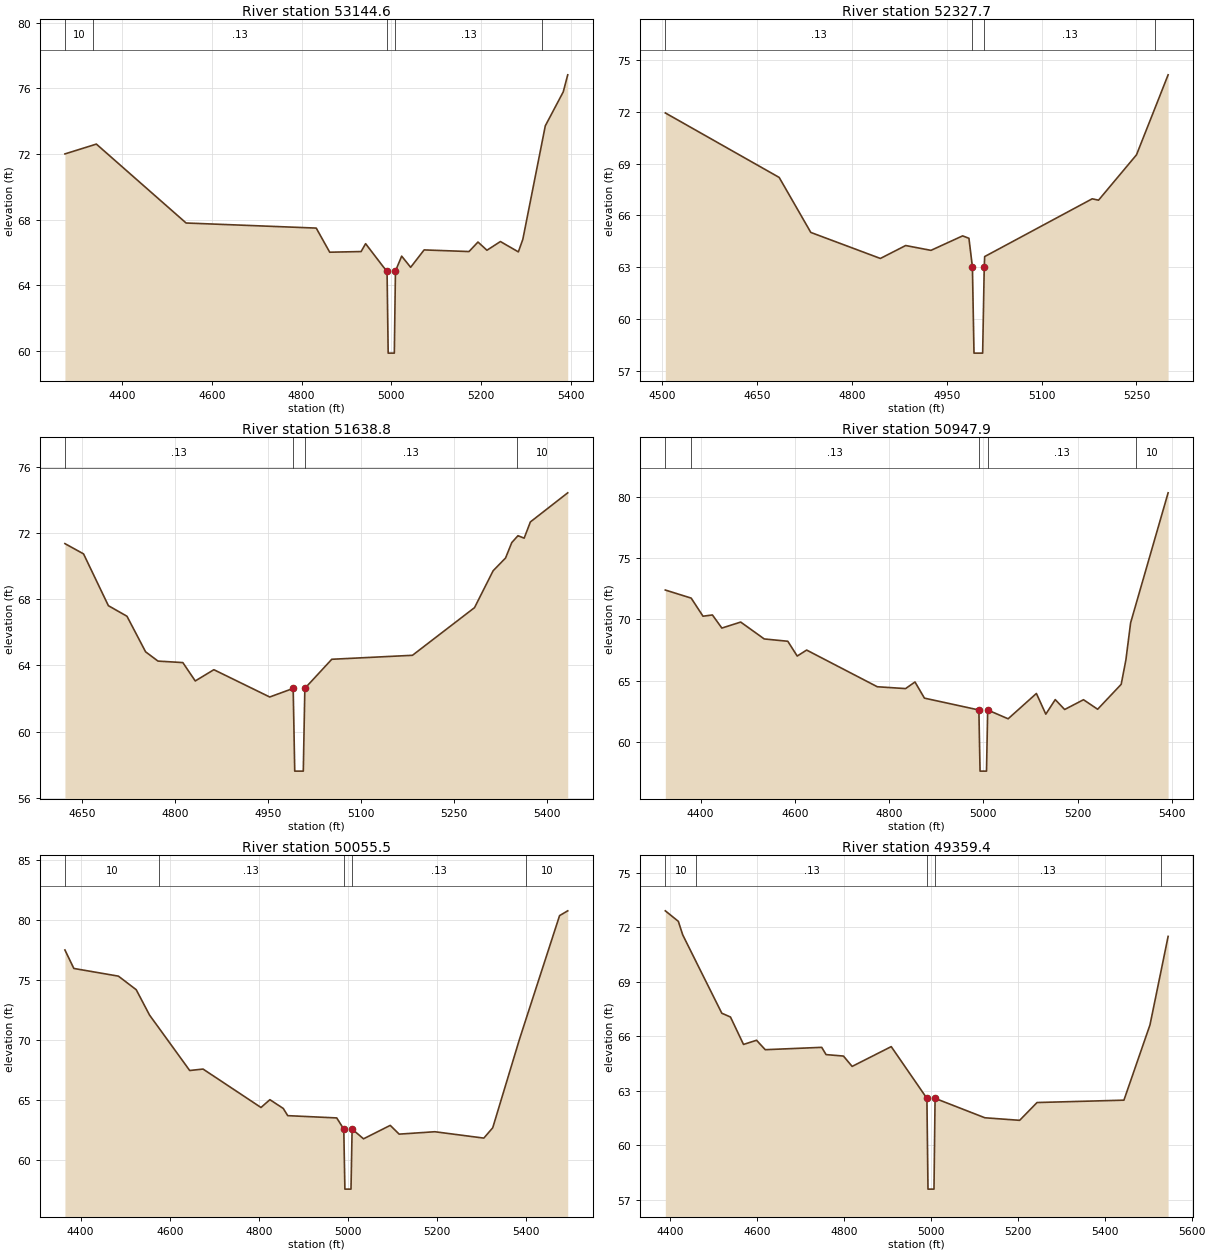
Type RM Length L Ch R = 1 ,53144.6,816.9,816.9,816.9
XS GIS Cut Line= 3
   .213381530319   .106582348162   .229760041310   .091020428091
   .241672704400   .086189126846
BEGIN DESCRIPTION:
Wheat Swamp 65.0
END DESCRIPTION:
#Sta/Elev= 26
  4272.8   72.01  4334.9   72.54  4342.8   72.61  4542.8    67.8  4832.8   67.49
  4862.8   66.02  4932.8   66.06  4942.8   66.54  4982.8   65.11  4990.6   64.87
  4993.1   59.87  5006.8   59.87  5009.3   64.87  5023.2   65.78  5043.2    65.1
  5073.2   66.16  5173.2   66.06  5193.2   66.64  5213.2   66.14  5243.2   66.67
  5283.2   66.04  5293.2   66.81  5334.9   72.57  5343.2   73.72  5383.2   75.79
  5393.2   76.83
#Mann= 5 , 1 , 0
 4272.80      10       0  4334.9    0.13       0  4990.6   0.042       0
  5009.3    0.13       0  5334.9      10       0
Bank Sta=4990.60,5009.30
Exp/Cntr=0.3,0.1

Type RM Length L Ch R = 1 ,52327.7,688.9,688.9,688.9
XS GIS Cut Line= 3
   .229179244276   .110767527268   .244132822051   .107494390235
   .257289820750   .102984847004
BEGIN DESCRIPTION:
Wheat Swamp 64.0
END DESCRIPTION:
#Sta/Elev= 18
  4505.1   71.94  4685.1    68.2  4735.1   65.01  4845.1    63.5  4885.1   64.25
  4925.1   63.97  4975.1   64.81  4985.1   64.67  4990.6   63.01  4993.1   58.01
  5006.8   58.01  5009.3   63.01    5010   63.61    5180   66.96    5190   66.88
    5250   69.51  5279.9   72.28    5300   74.15
#Mann= 4 , 1 , 0
 4505.10    0.13       0  4990.6   0.042       0  5009.3    0.13       0
  5279.9      10       0
Bank Sta=4990.60,5009.30
Exp/Cntr=0.3,0.1

Type RM Length L Ch R = 1 ,51638.8,690.9,690.9,690.9
XS GIS Cut Line= 3
   .240258145696   .131101365700   .250784893963   .125868250167
   .263008964853   .120610055311
BEGIN DESCRIPTION:
Wheat Swamp 63.0
END DESCRIPTION:
#Sta/Elev= 25
  4622.8   71.36  4652.8   70.74  4692.8   67.61  4722.8   66.97  4752.8   64.82
  4772.8   64.26  4812.8   64.17  4832.8   63.06  4862.8   63.74  4952.8   62.09
  4990.6   62.61  4993.1   57.61  5006.9   57.61  5009.4   62.61  5052.8   64.37
  5182.8   64.61  5282.8   67.49  5312.8   69.72  5332.8   70.49  5342.8   71.42
  5351.9    71.8  5352.8   71.84  5362.8   71.69  5372.8   72.67    5433   74.43
#Mann= 4 , 1 , 0
 4622.80    0.13       0  4990.6   0.042       0  5009.4    0.13       0
  5351.9      10       0
Bank Sta=4990.60,5009.40
Exp/Cntr=0.3,0.1

Type RM Length L Ch R = 1 ,50947.9,892.4,892.4,892.4
XS GIS Cut Line= 3
   .243087263104   .156799182157   .259708327877   .144539673388
   .269845998589   .137466879868
BEGIN DESCRIPTION:
Wheat Swamp 62.0
END DESCRIPTION:
#Sta/Elev= 30
    4325    72.4  4379.9   71.74    4405   70.26    4425   70.36    4445   69.29
    4485   69.78    4535    68.4    4585   68.21    4605      67    4625   67.49
    4775   64.49    4835   64.34    4855   64.88    4875   63.56  4990.6   62.59
  4993.1   57.59  5006.8   57.59  5009.3   62.59  5052.7   61.87  5112.7   63.94
  5132.7   62.25  5152.7   63.44  5172.7   62.63  5212.7   63.43  5242.7   62.65
  5292.7   64.69  5302.7   66.69  5312.7   69.72  5324.9   71.35  5392.3   80.35
#Mann= 5 , 1 , 0
 4325.00      10       0  4379.9    0.13       0  4990.6   0.042       0
  5009.3    0.13       0  5324.9      10       0
Bank Sta=4990.60,5009.30
Exp/Cntr=0.3,0.1

Type RM Length L Ch R = 1 ,50055.5,696.1,696.1,696.1
XS GIS Cut Line= 3
   .261239240586   .173842085225   .276918792110   .161750137621
   .288117381850   .151612466908
BEGIN DESCRIPTION:
Wheat Swamp 61.0
END DESCRIPTION:
#Sta/Elev= 27
  4364.9    77.5  4384.9   75.96  4484.9   75.32  4524.9   74.19  4554.9   72.07
  4574.9   71.05  4644.9   67.46  4674.9   67.58  4804.9   64.38  4824.9   65.03
  4854.9    64.3  4864.9    63.7  4974.9   63.51  4990.7   62.58  4993.2   57.58
  5006.9   57.58  5009.4   62.58    5035   61.77    5095   62.89    5115   62.16
    5195   62.36    5305   61.83    5325   62.69    5385   70.06  5399.9   71.77
    5475   80.36  5493.3   80.76
#Mann= 5 , 1 , 0
 4364.90      10       0  4574.9    0.13       0  4990.7   0.042       0
  5009.4    0.13       0  5399.9      10       0
Bank Sta=4990.70,5009.40
Exp/Cntr=0.3,0.1

Type RM Length L Ch R = 1 ,49359.4,776.3,776.3,776.3
XS GIS Cut Line= 3
   .272557236106   .186504914942   .289296180770   .177428163257
   .303677527595   .168822931141
BEGIN DESCRIPTION:
Wheat Swamp 60.0
END DESCRIPTION:
#Sta/Elev= 25
  4388.5   72.91  4418.5   72.33  4428.5   71.59  4459.9   70.08  4518.5   67.27
  4538.5   67.06  4568.5   65.55  4598.5   65.78  4618.5   65.26  4748.5   65.39
  4758.5   64.99  4798.5   64.91  4818.5   64.34  4908.5   65.43  4990.6   62.58
  4993.1   57.58  5006.9   57.58  5009.4   62.58  5124.1   61.51  5204.1   61.37
  5244.1   62.35  5444.1   62.48  5504.1   66.63  5529.9   69.64  5545.8    71.5
#Mann= 5 , 1 , 0
 4388.50      10       0  4459.9    0.13       0  4990.6   0.042       0
  5009.4    0.13       0  5529.9      10       0
Bank Sta=4990.60,5009.40
Exp/Cntr=0.3,0.1

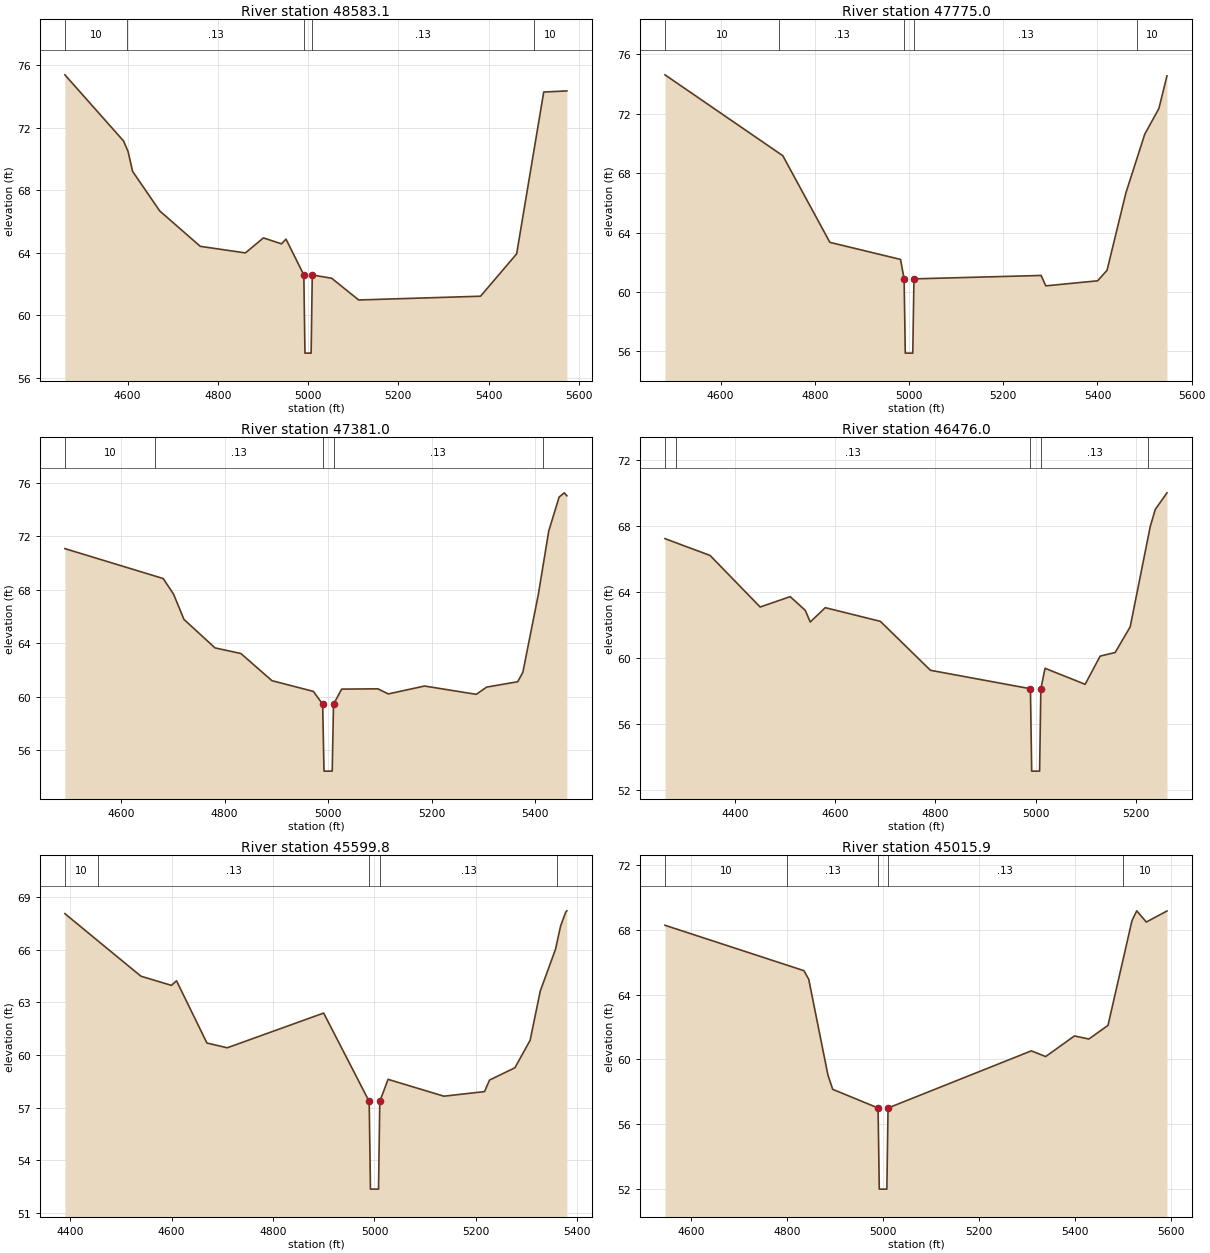
Type RM Length L Ch R = 1 ,48583.1,808.1,808.1,808.1
XS GIS Cut Line= 3
   .277743951354   .201711421011   .294129256342   .198292904142
   .310955466747   .192892227960
BEGIN DESCRIPTION:
Wheat Swamp 59.0
END DESCRIPTION:
#Sta/Elev= 22
  4461.2   75.38  4591.2   71.15  4599.9   70.57  4601.2   70.48  4611.2   69.21
  4671.2   66.68  4761.2   64.41  4861.2   63.99  4901.2   64.95  4941.2   64.57
  4951.2   64.87  4990.7   62.58  4993.2   57.58  5006.9   57.58  5009.4   62.58
  5052.3   62.37  5112.3   60.98  5382.3   61.22  5462.3   63.93  5499.9   70.42
  5522.3   74.28  5573.6   74.35
#Mann= 5 , 1 , 0
 4461.20      10       0  4599.9    0.13       0  4990.7   0.042       0
  5009.4    0.13       0  5499.9      10       0
Bank Sta=4990.70,5009.40
Exp/Cntr=0.3,0.1

Type RM Length L Ch R = 1 ,47775.0,394,394,394
XS GIS Cut Line= 3
   .292950457422   .229295315740   .302852368351   .216682167295
   .315111877119   .205012057987
BEGIN DESCRIPTION:
Wheat Swamp 58.0
END DESCRIPTION:
#Sta/Elev= 18
    4482   74.63  4724.9   69.34    4732   69.19    4832   63.35    4982    62.2
  4989.6   60.89  4992.1   55.89    5008   55.89  5010.5   60.89  5280.4   61.12
  5290.4   60.42  5400.4   60.76  5420.4   61.47  5460.4   66.68  5484.9    69.1
  5500.4   70.63  5530.4   72.36  5547.6   74.56
#Mann= 5 , 1 , 0
 4482.00      10       0  4724.9    0.13       0  4989.6   0.042       0
  5010.5    0.13       0  5484.9      10       0
Bank Sta=4989.60,5010.50
Exp/Cntr=0.3,0.1

Type RM Length L Ch R = 1 ,47381.0,905,905,905
XS GIS Cut Line= 3
   .300966290079   .235307190232   .312164879819   .223990720599
   .320534352151   .212674250967
BEGIN DESCRIPTION:
Wheat Swamp 57.0
END DESCRIPTION:
#Sta/Elev= 27
  4491.6   71.08  4664.9   69.04  4681.6   68.84  4701.6   67.67  4721.6   65.79
  4781.6   63.66  4831.6   63.24  4891.6   61.21  4971.6   60.41  4989.6   59.45
  4992.1   54.45    5008   54.45  5010.5   59.45  5026.3   60.58  5096.3    60.6
  5116.3   60.22  5186.3   60.81  5286.3   60.19  5306.3   60.73  5366.3   61.13
  5376.3   61.84  5406.3   67.68  5414.9   69.71  5426.3    72.4  5446.3   74.93
  5456.3   75.25  5461.3   75.03
#Mann= 5 , 1 , 0
 4491.60      10       0  4664.9    0.13       0  4989.6   0.042       0
  5010.5    0.13       0  5414.9      10       0
Bank Sta=4989.60,5010.50
Exp/Cntr=0.3,0.1

Type RM Length L Ch R = 1 ,46476.0,876.2,876.2,876.2
XS GIS Cut Line= 3
   .322774070099   .252635534357   .333972659840   .232713832608
   .338216335952   .225758918980
BEGIN DESCRIPTION:
Wheat Swamp 56.0
END DESCRIPTION:
#Sta/Elev= 23
    4260   67.24  4281.9   66.99    4350   66.22    4450   63.09    4510   63.72
    4540   62.89    4550   62.18    4580   63.05    4690   62.22    4790   59.25
  4989.6   58.13  4992.1   53.13  5007.9   53.13  5010.4   58.13  5018.8   59.37
  5098.8    58.4  5128.8   60.11  5158.8   60.33  5188.8   61.89  5224.9   67.38
  5228.8   67.97  5238.8   69.01  5262.2   70.02
#Mann= 5 , 1 , 0
 4260.00      10       0  4281.9    0.13       0  4989.6   0.042       0
  5010.4    0.13       0  5224.9      10       0
Bank Sta=4989.60,5010.40
Exp/Cntr=0.3,0.1

Type RM Length L Ch R = 1 ,45599.8,583.9,583.9,583.9
XS GIS Cut Line= 3
   .338687855520   .261594406149   .349532805585   .246270020188
   .355426800185   .236014469584
BEGIN DESCRIPTION:
Wheat Swamp 55.0
END DESCRIPTION:
#Sta/Elev= 24
  4389.9   68.06  4454.9   66.51  4539.9   64.49  4599.9   63.97  4609.9   64.23
  4669.9   60.68  4709.9   60.41  4899.9   62.39  4989.6   57.35  4992.1   52.35
    5008   52.35  5010.5   57.35  5026.8   58.61  5136.8   57.65  5216.8   57.91
  5226.8   58.57  5276.8   59.27  5306.8   60.84  5326.8   63.65  5356.8   66.03
  5359.9   66.44  5366.8   67.35  5376.8   68.14  5379.2   68.22
#Mann= 5 , 1 , 0
 4389.90      10       0  4454.9    0.13       0  4989.6   0.042       0
  5010.5    0.13       0  5359.9      10       0
Bank Sta=4989.60,5010.50
Exp/Cntr=0.3,0.1

Type RM Length L Ch R = 1 ,45015.9,750.4,750.4,750.4
XS GIS Cut Line= 3
   .347528847420   .267606280641   .359081076837   .259590447985
   .375466381826   .251338855545
BEGIN DESCRIPTION:
Wheat Swamp 54.0
END DESCRIPTION:
#Sta/Elev= 20
  4544.9   68.27  4799.9   65.81  4834.9   65.47  4844.9   64.94  4884.9   59.05
  4894.9   58.16  4989.6   57.01  4992.1   52.01  5007.9   52.01  5010.4   57.01
  5309.4   60.53  5339.4   60.18  5399.4   61.45  5429.4   61.26  5469.4    62.1
  5499.9   66.03  5519.4   68.55  5529.4   69.16  5549.4   68.47  5592.5   69.15
#Mann= 5 , 1 , 0
 4544.90      10       0  4799.9    0.13       0  4989.6   0.042       0
  5010.4    0.13       0  5499.9      10       0
Bank Sta=4989.60,5010.40
Exp/Cntr=0.3,0.1