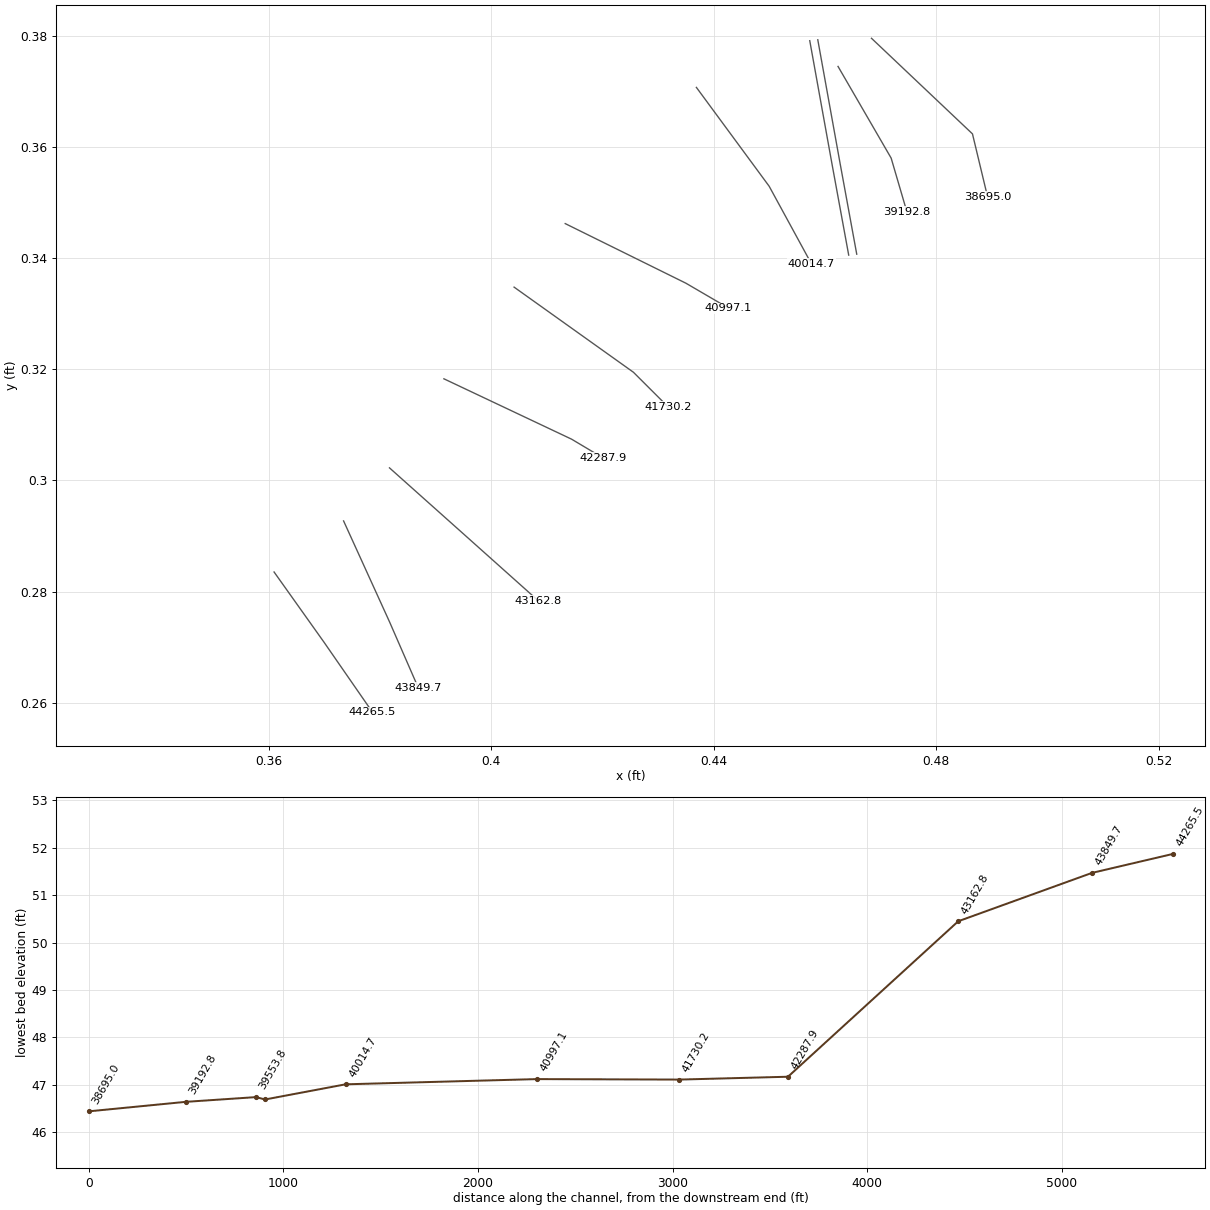
HEC-RAS study 2B CID37079C_DF_WHEAT SWAMP.PRJ: Wheat Swamp

--- 2B CID37079C_DF_WHEAT SWAMP.g01 (geometry) --- (continued)

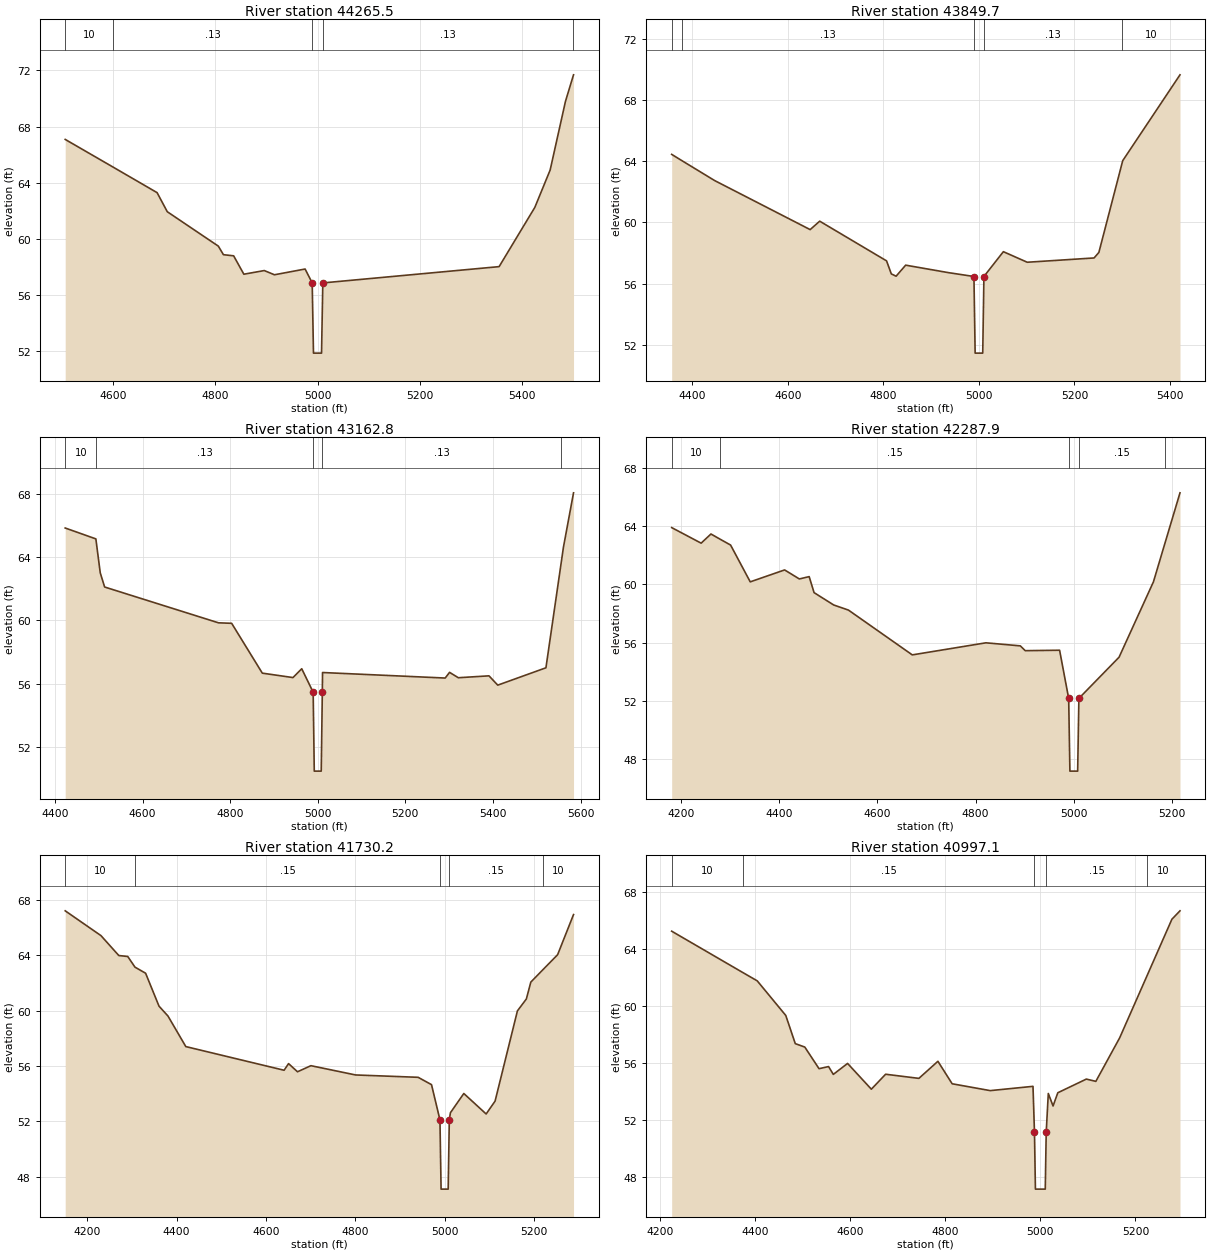
Type RM Length L Ch R = 1 ,44265.5,415.8,415.8,415.8
XS GIS Cut Line= 3
   .360967155109   .283520066062   .369926026901   .270906917617
   .378649138910   .258293769173
BEGIN DESCRIPTION:
Wheat Swamp 53.0
END DESCRIPTION:
#Sta/Elev= 21
  4505.7   67.09  4599.9   65.11  4685.7    63.3  4705.7   61.94  4805.7   59.49
  4815.7   58.88  4835.7    58.8  4855.7   57.49  4895.7   57.75  4915.7   57.45
  4975.7   57.86  4989.6   56.87  4992.1   51.87  5007.9   51.87  5010.4   56.87
  5355.8   58.03  5425.8   62.25  5455.8   64.91  5485.8    69.8  5499.9   71.49
  5501.6   71.69
#Mann= 5 , 1 , 0
 4505.70      10       0  4599.9    0.13       0  4989.6   0.042       0
  5010.4    0.13       0  5499.9      10       0
Bank Sta=4989.60,5010.40
Exp/Cntr=0.3,0.1

Type RM Length L Ch R = 1 ,43849.7,686.9,686.9,686.9
XS GIS Cut Line= 3
   .373462423662   .292714697638   .381714016102   .274561194270
   .386900731350   .262655325177
BEGIN DESCRIPTION:
Wheat Swamp 52.0
END DESCRIPTION:
#Sta/Elev= 21
  4356.5   64.44  4377.9   64.03  4446.5   62.73  4646.5   59.53  4666.5   60.08
  4806.5   57.49  4816.5   56.64  4826.5   56.49  4846.5   57.21  4936.5   56.72
  4989.5   56.47    4992   51.47  5007.9   51.47  5010.4   56.47  5051.1   58.09
  5101.1    57.4  5241.1   57.68  5251.1   58.04  5299.9   63.89  5301.1   64.03
    5421   69.63
#Mann= 5 , 1 , 0
 4356.50      10       0  4377.9    0.13       0  4989.5   0.042       0
  5010.4    0.13       0  5299.9      10       0
Bank Sta=4989.50,5010.40
Exp/Cntr=0.3,0.1

Type RM Length L Ch R = 1 ,43162.8,874.9,874.9,874.9
XS GIS Cut Line= 3
   .381714016102   .302262968891   .395034443899   .290357099798
   .408472751587   .278333350814
BEGIN DESCRIPTION:
Wheat Swamp 51.0
END DESCRIPTION:
#Sta/Elev= 24
  4423.5   65.86  4493.5   65.17  4494.9   64.87  4503.5   63.02  4513.5   62.12
  4773.5   59.85  4803.5   59.82  4873.5   56.66  4943.5   56.38  4963.5   56.94
  4989.6   55.45  4992.1   50.45    5008   50.45  5010.5   55.45    5011    56.7
    5291   56.35    5301   56.71    5321   56.37    5391   56.49    5411    55.9
    5521      57  5554.9   63.48    5561   64.65    5584   68.09
#Mann= 5 , 1 , 0
 4423.50      10       0  4494.9    0.13       0  4989.6   0.042       0
  5010.5    0.13       0  5554.9      10       0
Bank Sta=4989.60,5010.50
Exp/Cntr=0.3,0.1

Type RM Length L Ch R = 1 ,42287.9,557.7,557.7,557.7
XS GIS Cut Line= 3
   .391498047138   .318294634203   .414453498313   .307425403183
   .420142860896   .304031167271
BEGIN DESCRIPTION:
Wheat Swamp 50.0
END DESCRIPTION:
#Sta/Elev= 25
  4181.1   63.91  4241.1   62.84  4261.1   63.47  4279.9   63.11  4301.1   62.71
  4341.1   60.18  4411.1      61  4441.1   60.38  4461.1   60.54  4471.1   59.44
  4511.1   58.59  4541.1   58.24  4671.1   55.16  4821.1   55.99  4891.1   55.78
  4901.1   55.45  4971.1   55.48  4989.6   52.17  4992.1   47.17  5007.9   47.17
  5010.4   52.17  5092.2      55  5162.2   60.18  5184.9   62.75  5216.3    66.3
#Mann= 5 , 1 , 0
 4181.10      10       0  4279.9    0.15       0  4989.6   0.045       0
  5010.4    0.15       0  5184.9      10       0
Bank Sta=4989.60,5010.40
Exp/Cntr=0.3,0.1

Type RM Length L Ch R = 1 ,41730.2,733.1,733.1,733.1
XS GIS Cut Line= 3
   .404111195583   .334797819084   .425565335928   .319473433123
   .431812970204   .313225798847
BEGIN DESCRIPTION:
Wheat Swamp 49.0
END DESCRIPTION:
#Sta/Elev= 30
  4150.7   67.22  4230.7   65.43  4270.7   63.99  4290.7   63.92  4306.9   63.15
  4330.7   62.71  4360.7   60.33  4380.7   59.62  4420.7   57.41  4640.7    55.7
  4650.7   56.18  4670.7   55.59  4700.7   56.03  4800.7   55.36  4940.7   55.19
  4970.7   54.66  4989.6   52.11  4992.1   47.11    5008   47.11  5010.5   52.11
    5013   52.63    5043   54.02    5093   52.54    5113   53.47    5163   59.99
    5183   60.85    5193   62.07  5219.9   62.96    5253   64.05  5288.6   66.95
#Mann= 5 , 1 , 0
 4150.70      10       0  4306.9    0.15       0  4989.6   0.045       0
  5010.5    0.15       0  5219.9      10       0
Bank Sta=4989.60,5010.50
Exp/Cntr=0.3,0.1

Type RM Length L Ch R = 1 ,40997.1,982.4,982.4,982.4
XS GIS Cut Line= 3
   .413305827159   .346232168608   .434995727288   .335505098436
   .442657920269   .331025662540
BEGIN DESCRIPTION:
Wheat Swamp 48.0
END DESCRIPTION:
#Sta/Elev= 30
  4224.5   65.24  4374.9   62.32  4404.5   61.75  4464.5   59.32  4484.5   57.34
  4504.5    57.1  4534.5   55.58  4554.5   55.73  4564.5   55.18  4594.5   55.95
  4644.5   54.14  4674.5   55.19  4744.5    54.9  4784.5    56.1  4814.5   54.52
  4894.5   54.04  4984.5   54.34  4987.6   51.12  4989.6   47.12  5010.3   47.12
  5012.3   51.12  5016.7   53.84  5026.7   52.96  5036.7   53.89  5096.7   54.85
  5116.7   54.69  5166.7   57.74  5224.9   62.15  5276.7   66.08  5293.7   66.67
#Mann= 5 , 1 , 0
 4224.50      10       0  4374.9    0.15       0  4987.6   0.045       0
  5012.3    0.15       0  5224.9      10       0
Bank Sta=4987.60,5012.30
Exp/Cntr=0.3,0.1

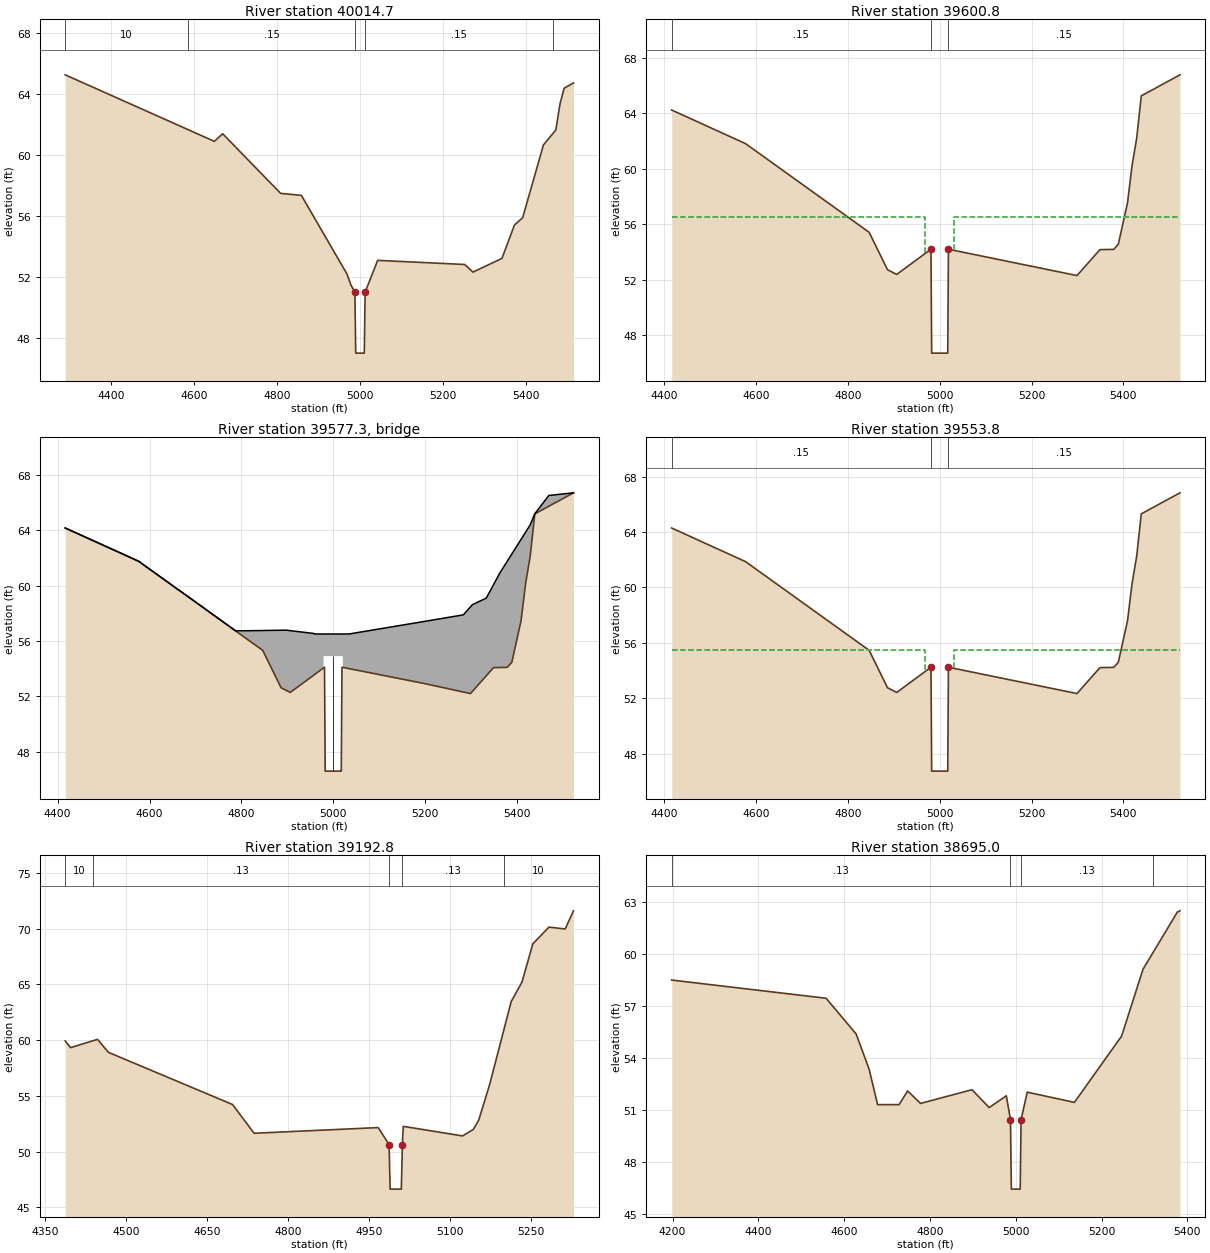
Type RM Length L Ch R = 1 ,40014.7,413.9,413.9,413.9
XS GIS Cut Line= 3
   .436881805560   .370751186146   .449966473573   .352951322453
   .457548638280   .339020761865
BEGIN DESCRIPTION:
Wheat Swamp 47.0
END DESCRIPTION:
#Sta/Elev= 24
  4288.5   65.25  4584.9   61.66  4648.5   60.89  4668.5   61.39  4808.5   57.48
  4858.5   57.35  4968.5    52.2  4978.5   51.45  4987.7   51.01  4989.7   47.01
  5010.4   47.01  5012.4   51.01  5042.7   53.09  5252.7   52.82  5272.7   52.32
  5342.7   53.22  5372.7    55.4  5392.7   55.89  5442.7   60.65  5464.9   61.38
  5472.7   61.64  5482.7   63.34  5492.7   64.37  5515.4   64.72
#Mann= 5 , 1 , 0
 4288.50      10       0  4584.9    0.15       0  4987.7   0.045       0
  5012.4    0.15       0  5464.9      10       0
Bank Sta=4987.70,5012.40
Exp/Cntr=0.5,0.3

Type RM Length L Ch R = 1 ,39600.8,47,47,47
XS GIS Cut Line= 3
   .457260316471   .379153826196   .461240705985   .357056917171
   .464260850565   .340562281388
BEGIN DESCRIPTION:
Upstream Section of Bridge/Culvert/Weir
END DESCRIPTION:
#Sta/Elev= 18
  4416.4   64.24  4577.4   61.81  4846.4   55.41  4886.4   52.71  4906.4   52.37
    4981   54.19  4982.5   46.69  5017.5   46.69    5019   54.19  5298.9   52.29
  5348.9   54.16  5378.9   54.18  5388.9   54.55  5408.9   57.54  5418.9   60.24
  5428.9   62.21  5438.9   65.26  5523.2   66.78
#Mann= 3 , 1 , 0
 4416.40    0.15       0    4981    0.05       0    5019    0.15       0
#XS Ineff= 2 , 0
       0    4967    56.5    5032       0    56.5
Bank Sta=4981.00,5019.00
Exp/Cntr=0.5,0.3

Type RM Length L Ch R = 3 ,39577.3,,,
BEGIN DESCRIPTION:
State Highway 58-TOR
Structure ID: NC 58-Bridge
Approximate Survey Structure
END DESCRIPTION:
Bridge Culvert--1,0,-1,-1, 0
Deck Dist Width WeirC Skew NumUp NumDn MinLoCord MaxHiCord MaxSubmerge Is_Ogee
10,27,2.6,,52,52,,,0.95,0,1,1,,
  4416.4  4417.4  4427.4  4447.4  4467.4  4497.4  4557.4  4576.4  4577.4  4597.4
  4637.4  4647.4  4657.4  4667.4  4707.4  4717.4  4737.4  4787.4  4827.4  4846.4
  4886.4  4897.4  4906.4  4957.4  4958.3 4978.91    4979    4981  4982.5    4983
    5000    5017  5017.5    5019 5020.89    5021  5034.2  5198.9  5283.2  5298.9
  5303.2  5333.2  5348.9  5363.2  5378.9  5388.9  5408.9  5418.9  5428.9  5438.9
  5469.4  5523.2
   64.15   64.14   63.99   63.69   63.39   62.94   62.04   61.75   61.73   61.25
    60.3   60.06   59.82   59.59   58.64    58.4   57.92   56.73   56.74   56.75
   56.77   56.78   56.74   56.54    56.5    56.5    56.5    56.5    56.5    56.5
    56.5    56.5    56.5    56.5    56.5    56.5    56.5   57.41   57.88   58.46
   58.62   59.09   60.05   60.93   61.75   62.28   63.33   63.85   64.38   65.18
    66.5   66.69
   64.15   64.13   63.98   63.68   63.38   62.93   62.03   61.74   61.72   61.24
   60.29   60.05   59.81   59.58   58.63   58.39   57.91   56.72   55.77   55.32
   52.62   52.43   52.28   53.52   53.55   54.05    54.9    54.9    54.9    54.9
    54.9    54.9    54.9    54.9    54.9   54.09      54   52.92   52.31    52.2
   52.36   53.48   54.07   54.08   54.09   54.46   57.45   60.15   62.12   65.17
   65.72   66.69
  4416.4  4417.4  4427.4  4447.4  4467.4  4497.4  4557.4  4576.4  4577.4  4597.4
  4637.4  4647.4  4657.4  4667.4  4707.4  4717.4  4737.4  4787.4  4827.4  4846.4
  4886.4  4897.4  4906.4  4957.4  4958.3 4978.91    4979    4981  4982.5    4983
    5000    5017  5017.5    5019 5020.89    5021  5034.2  5198.9  5283.2  5298.9
  5303.2  5333.2  5348.9  5363.2  5378.9  5388.9  5408.9  5418.9  5428.9  5438.9
  5469.4  5523.2
   64.15   64.14   63.99   63.69   63.39   62.94   62.04   61.75   61.73   61.25
    60.3   60.06   59.82   59.59   58.64    58.4   57.92   56.73   56.74   56.75
   56.77   56.78   56.74   56.54    56.5    56.5    56.5    56.5    56.5    56.5
    56.5    56.5    56.5    56.5    56.5    56.5    56.5   57.41   57.88   58.46
   58.62   59.09   60.05   60.93   61.75   62.28   63.33   63.85   64.38   65.18
    66.5   66.69
    63.9   63.88   63.73   63.43   63.13   62.68   61.78   61.49   61.47   60.99
   60.04    59.8   59.56   59.33   58.38   58.14   57.66   56.47   55.52   55.07
   52.37   52.18   52.03   53.27    53.3    53.8   54.65   54.65   54.65   54.65
   54.65   54.65   54.65   54.65   54.65   53.84   53.75   52.67   52.06   51.95
   52.11   53.23   53.82   53.83   53.84   54.21    57.2    59.9   61.87   64.92
   65.47   66.44
Pier Skew, UpSta & Num, DnSta & Num=,5000.0, 2 ,5000.0, 2 , 0 , 0 , 0 ,,
       1       1
    45.6    55.9
       1       1
   45.35   55.65
Abutment Skew #Up #Dn=, 2 , 2
 4978.80 4983.00
   54.90   46.60
 4978.80 4983.00
   54.65   46.35
Abutment Skew #Up #Dn=, 2 , 2
 5017.00 5021.09
   46.60   54.90
 5017.00 5021.09
   46.35   54.65
BR Coef= 1 , 1 , 0 ,1.25, 0 ,,,0.8,0,2,0,
Wspro=,,,, 1 ,,,, 0 ,,,, 0 ,,,,-1 ,-1 ,-1 , 0 , 0 , 0 , 0 , 0
BC Design=,, 0 ,, 0 ,,,,,,
BR U #Sta/Elev= 52
  4416.4   64.15  4417.4   64.13  4427.4   63.98  4447.4   63.68  4467.4   63.38
  4497.4   62.93  4557.4   62.03  4576.4   61.74  4577.4   61.72  4597.4   61.24
  4637.4   60.29  4647.4   60.05  4657.4   59.81  4667.4   59.58  4707.4   58.63
  4717.4   58.39  4737.4   57.91  4787.4   56.72  4827.4   55.77  4846.4   55.32
  4886.4   52.62  4897.4   52.43  4906.4   52.28  4957.4   53.52  4958.3   53.55
 4978.91   54.05    4979   54.05    4981    54.1  4982.5    46.6    4983    46.6
    5000    46.6    5017    46.6  5017.5    46.6    5019    54.1 5020.89   54.09
    5021   54.09  5034.2      54  5198.9   52.92  5283.2   52.31  5298.9    52.2
  5303.2   52.36  5333.2   53.48  5348.9   54.07  5363.2   54.08  5378.9   54.09
  5388.9   54.46  5408.9   57.45  5418.9   60.15  5428.9   62.12  5438.9   65.17
  5469.4   65.72  5523.2   66.69
BR U #Mann= 3
 4416.40    0.15    4981    0.05    5019    0.15
BR U Banks=4981.00,5019.00
BR D #Sta/Elev= 52
  4416.4    63.9  4417.4   63.88  4427.4   63.73  4447.4   63.43  4467.4   63.13
  4497.4   62.68  4557.4   61.78  4576.4   61.49  4577.4   61.47  4597.4   60.99
  4637.4   60.04  4647.4    59.8  4657.4   59.56  4667.4   59.33  4707.4   58.38
  4717.4   58.14  4737.4   57.66  4787.4   56.47  4827.4   55.52  4846.4   55.07
  4886.4   52.37  4897.4   52.18  4906.4   52.03  4957.4   53.27  4958.3    53.3
 4978.91    53.8    4979    53.8    4981   53.85  4982.5   46.35    4983   46.35
    5000   46.35    5017   46.35  5017.5   46.35    5019   53.85 5020.89   53.84
    5021   53.84  5034.2   53.75  5198.9   52.67  5283.2   52.06  5298.9   51.95
  5303.2   52.11  5333.2   53.23  5348.9   53.82  5363.2   53.83  5378.9   53.84
  5388.9   54.21  5408.9    57.2  5418.9    59.9  5428.9   61.87  5438.9   64.92
  5469.4   65.47  5523.2   66.44
BR D #Mann= 3
 4416.40    0.15    4981    0.05    5019    0.15
BR D Banks=4981.00,5019.00

Type RM Length L Ch R = 1 ,39553.8,361,361,361
XS GIS Cut Line= 3
   .458704295987   .379323250544   .462684685501   .357226341519
   .465704830081   .340731705736
BEGIN DESCRIPTION:
Downstream Section of Bridge/Culvert/Weir
END DESCRIPTION:
#Sta/Elev= 18
  4416.4   64.29  4577.4   61.86  4846.4   55.46  4886.4   52.76  4906.4   52.42
    4981   54.24  4982.5   46.74  5017.5   46.74    5019   54.24  5298.9   52.34
  5348.9   54.21  5378.9   54.23  5388.9    54.6  5408.9   57.59  5418.9   60.29
  5428.9   62.26  5438.9   65.31  5523.2   66.83
#Mann= 3 , 1 , 0
 4416.40    0.15       0    4981    0.05       0    5019    0.15       0
#XS Ineff= 2 , 0
       0    4967    55.5    5032       0    55.5
Bank Sta=4981.00,5019.00
Exp/Cntr=0.5,0.3

Type RM Length L Ch R = 1 ,39192.8,497.8,497.8,497.8
XS GIS Cut Line= 3
   .462343862233   .374523342690   .471892133486   .358020157809
   .474721250894   .348354006665
BEGIN DESCRIPTION:
Wheat Swamp 46.0
END DESCRIPTION:
#Sta/Elev= 24
  4387.6   59.93  4397.6   59.33  4439.9   59.96  4447.6   60.07  4467.6   58.91
  4697.6   54.23  4737.6   51.65  4967.6   52.16  4987.7   50.64  4989.7   46.64
  5010.4   46.64  5012.4   50.64    5014   52.27    5124   51.41    5144      52
    5154   52.85    5174   56.01  5199.9   60.83    5214   63.46    5234   65.21
    5254   68.63    5284   70.14    5314   69.97  5329.5    71.6
#Mann= 5 , 1 , 0
 4387.60      10       0  4439.9    0.13       0  4987.7   0.042       0
  5012.4    0.13       0  5199.9      10       0
Bank Sta=4987.70,5012.40
Exp/Cntr=0.3,0.1

Type RM Length L Ch R = 1 ,38695.0,885.3,885.3,885.3
XS GIS Cut Line= 3
   .468355736726   .379592178046   .486509240094   .362381713813
   .489220477610   .351065244181
BEGIN DESCRIPTION:
Wheat Swamp 45.0
END DESCRIPTION:
#Sta/Elev= 22
    4198   58.49    4558   57.44    4628   55.38    4658   53.37    4678   51.31
    4728   51.31    4748    52.1    4778   51.38    4898   52.17    4938   51.14
    4978   51.82  4987.7   50.44  4989.7   46.44  5010.4   46.44  5012.4   50.44
  5026.7   52.03  5136.7   51.44  5246.7   55.26  5296.7   59.12  5319.9   60.07
  5376.7   62.41  5382.8   62.48
#Mann= 4 , 1 , 0
 4198.00    0.13       0  4987.7   0.042       0  5012.4    0.13       0
  5319.9      10       0
Bank Sta=4987.70,5012.40
Exp/Cntr=0.3,0.1