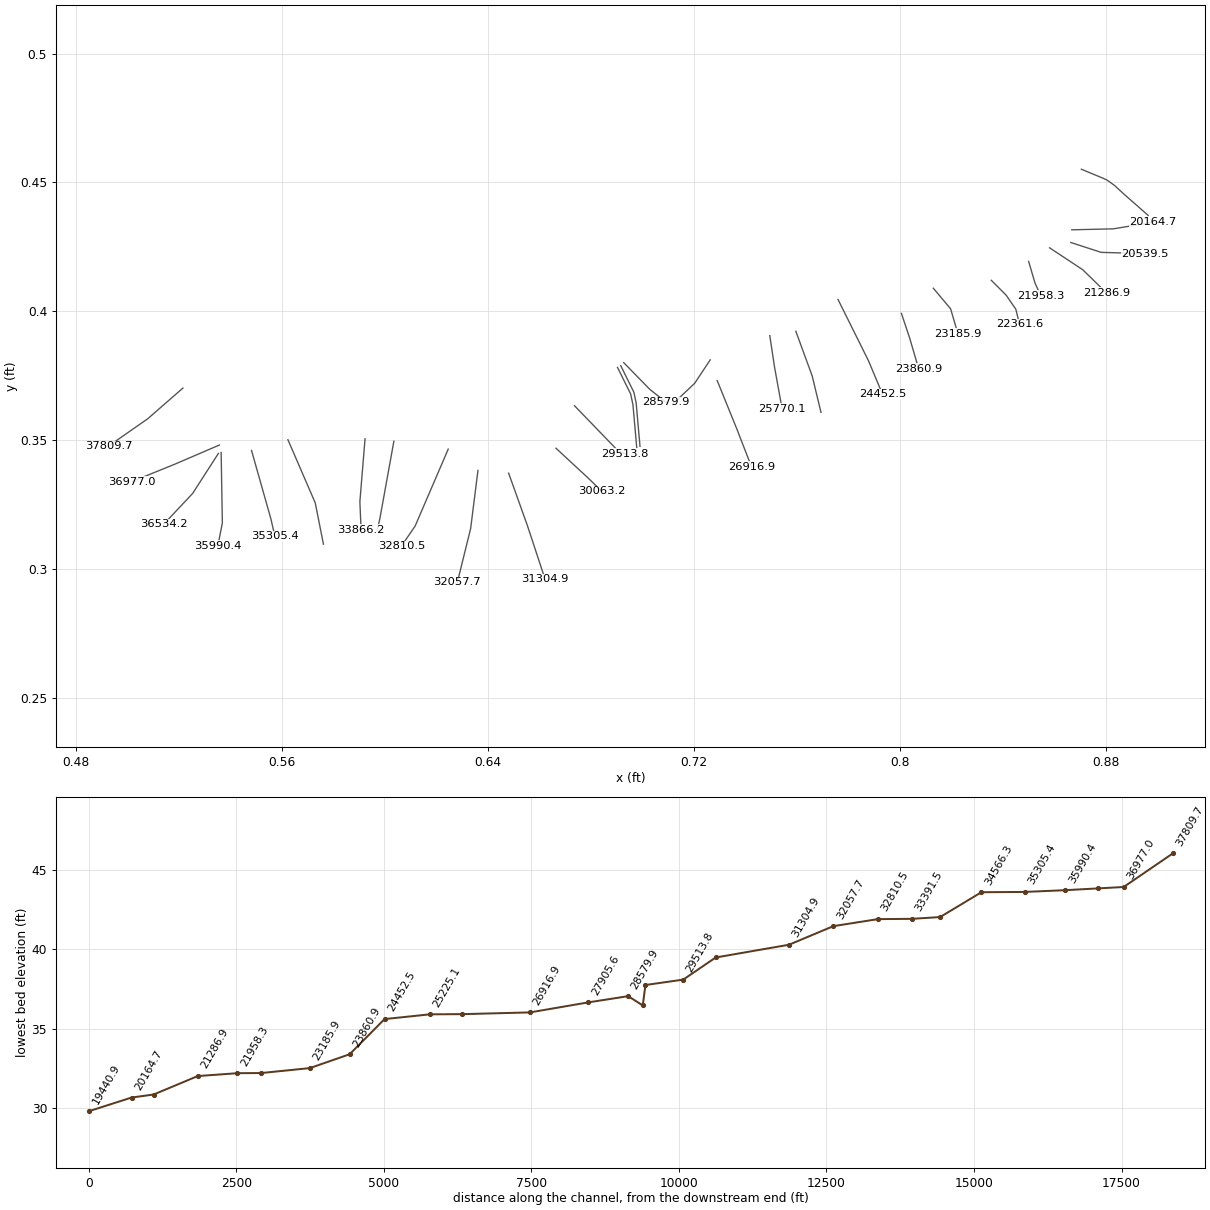
HEC-RAS study 2B CID37079C_DF_WHEAT SWAMP.PRJ: Wheat Swamp

--- 2B CID37079C_DF_WHEAT SWAMP.g01 (geometry) --- (continued)

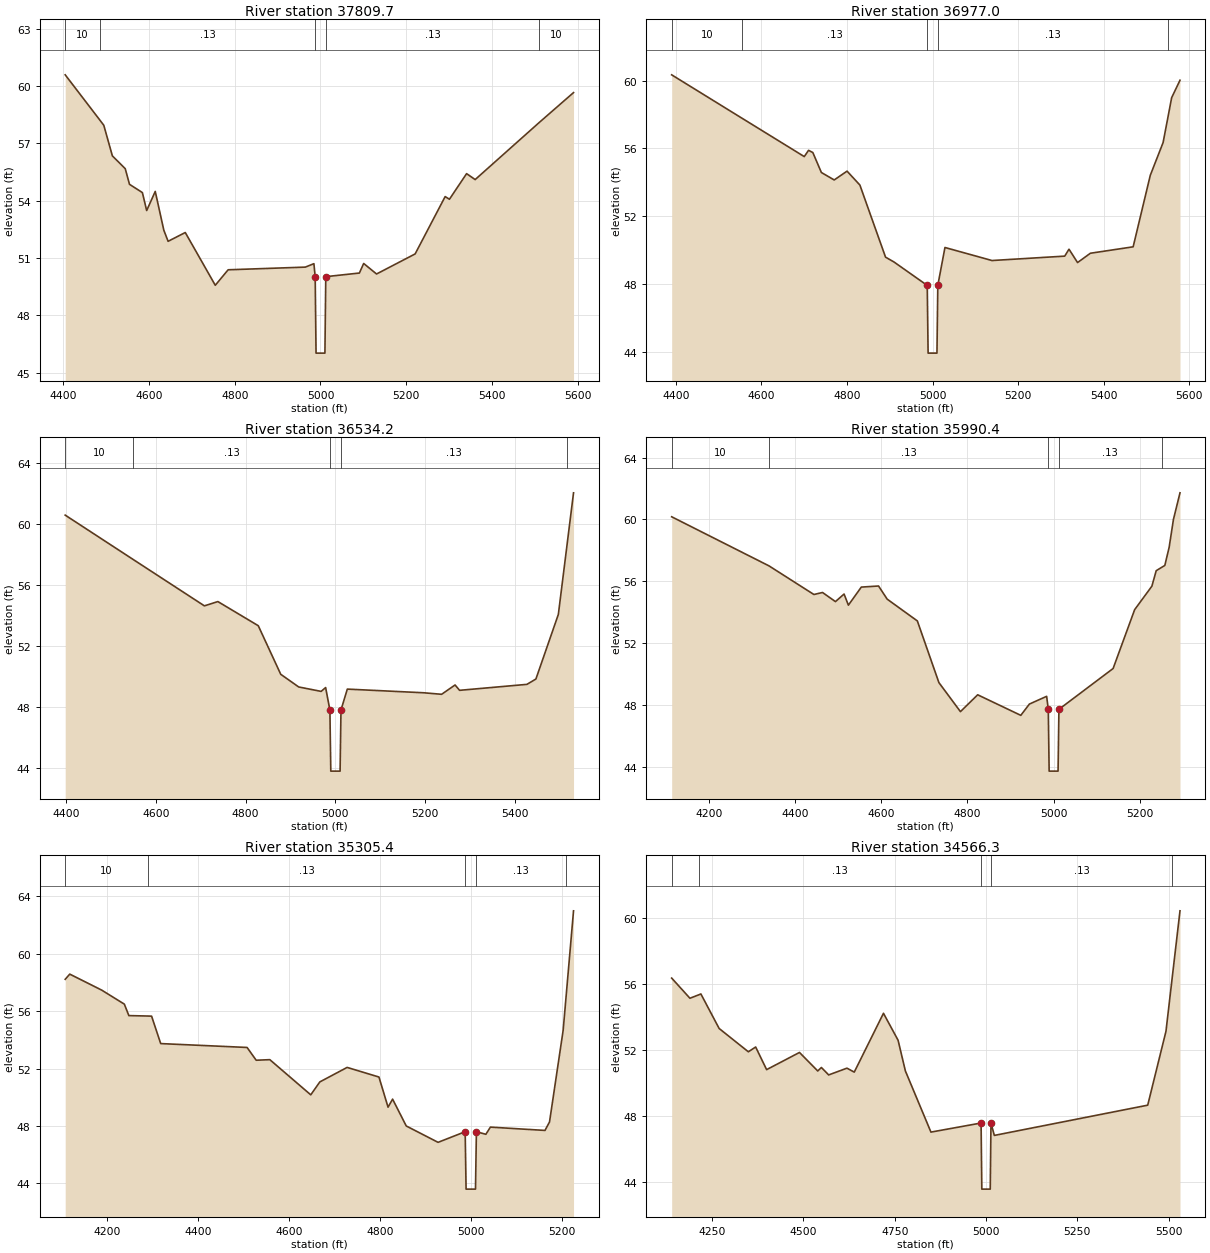
Type RM Length L Ch R = 1 ,37809.7,832.7,832.7,832.7
XS GIS Cut Line= 3
   .521519568020   .370161786686   .507845500547   .358255917593
   .492638994479   .347646727313
BEGIN DESCRIPTION:
Wheat Swamp 44.0
END DESCRIPTION:
#Sta/Elev= 30
  4404.7   60.58  4484.9   58.23  4494.7   57.94  4514.7   56.34  4544.7   55.67
  4554.7   54.85  4584.7   54.42  4594.7   53.48  4614.7   54.48  4634.7   52.45
  4644.7   51.87  4684.7   52.33  4754.7   49.57  4784.7   50.38  4964.7   50.52
  4984.7    50.7  4987.7   50.02  4989.7   46.02  5010.4   46.02  5012.4   50.02
  5090.8   50.21  5100.8   50.71  5130.8   50.16  5220.8   51.21  5290.8   54.21
  5300.8   54.07  5340.8   55.41  5360.8    55.1  5509.9   58.08  5590.2   59.65
#Mann= 5 , 1 , 0
 4404.70      10       0  4484.9    0.13       0  4987.7   0.042       0
  5012.4    0.13       0  5509.9      10       0
Bank Sta=4987.70,5012.40
Exp/Cntr=0.3,0.1

Type RM Length L Ch R = 1 ,36977.0,442.8,442.8,442.8
XS GIS Cut Line= 3
   .535723919137   .348081195605   .518416167506   .340646993562
   .501805372317   .333909747961
BEGIN DESCRIPTION:
Wheat Swamp 43.0
END DESCRIPTION:
#Sta/Elev= 27
  4390.1   60.35  4554.9   57.78  4700.1   55.52  4710.1   55.89  4720.1   55.76
  4740.1   54.58  4770.1   54.14  4800.1   54.66  4830.1   53.84  4890.1   49.58
  4910.1   49.29  4987.6   47.91  4989.6   43.91  5010.3   43.91  5012.3   47.91
    5029   50.15    5139   49.38    5309   49.64    5319   50.05    5339   49.26
    5369   49.81    5469   50.19    5509   54.41    5539   56.35  5549.9   57.79
    5559      59  5578.5   60.03
#Mann= 5 , 1 , 0
 4390.10      10       0  4554.9    0.13       0  4987.6   0.042       0
  5012.3    0.13       0  5549.9      10       0
Bank Sta=4987.60,5012.30
Exp/Cntr=0.3,0.1

Type RM Length L Ch R = 1 ,36534.2,543.8,543.8,543.8
XS GIS Cut Line= 3
   .535311515385   .344817609905   .525291724564   .329257464160
   .513975254931   .317233715175
BEGIN DESCRIPTION:
Wheat Swamp 42.0
END DESCRIPTION:
#Sta/Elev= 23
  4398.2   60.58  4549.9   57.67  4708.2   54.64  4738.2   54.92  4828.2   53.34
  4878.2   50.16  4918.2   49.33  4968.2   49.04  4978.2   49.29  4987.7   47.82
  4989.7   43.82  5010.4   43.82  5012.4   47.82  5026.5   49.19  5196.5   48.95
  5236.5   48.85  5266.5   49.46  5276.5   49.11  5426.5    49.5  5446.5   49.85
  5496.5   54.08  5514.9   58.41  5530.3   62.04
#Mann= 5 , 1 , 0
 4398.20      10       0  4549.9    0.13       0  4987.7   0.042       0
  5012.4    0.13       0  5514.9      10       0
Bank Sta=4987.70,5012.40
Exp/Cntr=0.3,0.1

Type RM Length L Ch R = 1 ,35990.4,685,685,685
XS GIS Cut Line= 3
   .536372434412   .345171249580   .536843953981   .317823114635
   .535075755600   .308864242843
BEGIN DESCRIPTION:
Wheat Swamp 41.0
END DESCRIPTION:
#Sta/Elev= 30
  4113.9   60.17  4339.9   56.99  4443.9   55.14  4463.9   55.27  4493.9   54.68
  4513.9   55.17  4523.9   54.45  4553.9   55.62  4593.9   55.69  4613.9   54.84
  4683.9   53.43  4733.9   49.44  4783.9   47.56  4823.9   48.65  4923.9   47.32
  4943.9   48.05  4983.9   48.55  4987.7   47.71  4989.7   43.71  5010.4   43.71
  5012.4   47.71  5138.1   50.35  5188.1   54.16  5228.1   55.68  5238.1   56.68
  5250.9    56.9  5258.1   57.02  5268.1   58.19  5278.1      60  5293.3   61.72
#Mann= 5 , 1 , 0
 4113.90      10       0  4339.9    0.13       0  4987.7   0.042       0
  5012.4    0.13       0  5250.9      10       0
Bank Sta=4987.70,5012.40
Exp/Cntr=0.3,0.1

Type RM Length L Ch R = 1 ,35305.4,739.1,739.1,739.1
XS GIS Cut Line= 3
   .548160423613   .345996408825   .555704736701   .319355553231
   .557237175297   .312636399387
BEGIN DESCRIPTION:
Wheat Swamp 40.0
END DESCRIPTION:
#Sta/Elev= 30
  4108.1   58.22  4118.1   58.58  4188.1   57.47  4238.1   56.49  4248.1   55.69
  4289.9   55.66  4298.1   55.65  4318.1   53.74  4508.1   53.47  4528.1   52.58
  4558.1   52.62  4648.1   50.17  4668.1   51.07  4728.1   52.08  4798.1   51.41
  4818.1   49.31  4828.1   49.87  4858.1      48  4928.1   46.86  4987.7    47.6
  4989.7    43.6  5010.4    43.6  5012.4    47.6  5033.2   47.42  5043.2   47.92
  5163.2   47.69  5173.2   48.28  5203.2   54.67  5209.9   57.11    5226   62.99
#Mann= 5 , 1 , 0
 4108.10      10       0  4289.9    0.13       0  4987.7   0.042       0
  5012.4    0.13       0  5209.9      10       0
Bank Sta=4987.70,5012.40
Exp/Cntr=0.3,0.1

Type RM Length L Ch R = 1 ,34566.3,700.1,700.1,700.1
XS GIS Cut Line= 3
   .562306010654   .350122205045   .572915200934   .325603187508
   .576097958018   .309571522195
BEGIN DESCRIPTION:
Wheat Swamp 39.0
END DESCRIPTION:
#Sta/Elev= 27
  4139.2   56.35  4189.2   55.13  4214.9   55.35  4219.2   55.39  4269.2    53.3
  4349.2   51.89  4369.2   52.18  4399.2   50.81  4489.2   51.85  4539.2   50.73
  4549.2   50.94  4569.2   50.49  4619.2    50.9  4639.2   50.66  4719.2   54.22
  4759.2   52.59  4779.2   50.73  4849.2   47.03  4986.5   47.58  4988.5   43.58
  5011.6   43.58  5013.6   47.58  5022.8   46.83  5442.8   48.66  5492.8   53.13
  5509.9   56.38  5531.2   60.42
#Mann= 5 , 1 , 0
 4139.20      10       0  4214.9    0.13       0  4986.5   0.042       0
  5013.6    0.13       0  5509.9      10       0
Bank Sta=4986.50,5013.60
Exp/Cntr=0.3,0.1

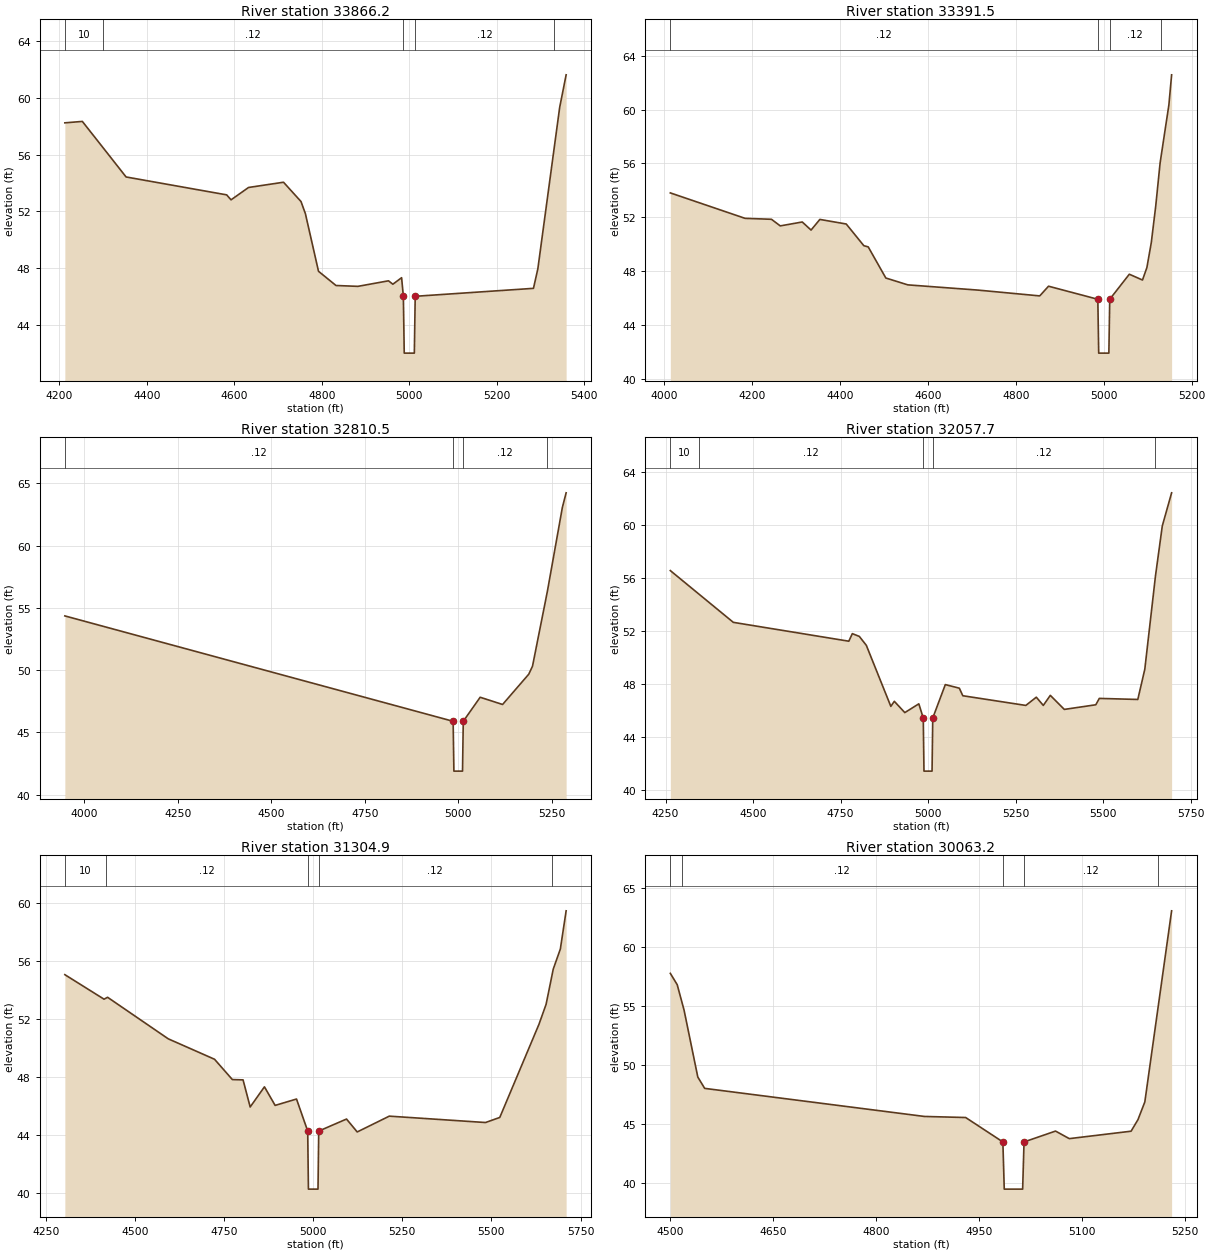
Type RM Length L Ch R = 1 ,33866.2,474.7,474.7,474.7
XS GIS Cut Line= 3
   .592247503223   .350475844721   .590243545059   .326074707076
   .590715064627   .315111877119
BEGIN DESCRIPTION:
Wheat Swamp 38.0
END DESCRIPTION:
#Sta/Elev= 25
  4212.5   58.23  4252.5   58.33  4299.9   56.48  4352.5   54.42  4582.5   53.16
  4592.5   52.81  4632.5   53.68  4712.5   54.05  4752.5   52.69  4762.5   51.84
  4792.5   47.78  4832.5   46.78  4882.5   46.72  4952.5   47.11  4962.5   46.87
  4982.5   47.33  4986.5   46.02  4988.5   42.02  5011.6   42.02  5013.6   46.02
    5284   46.58    5294   47.95  5330.9   56.35    5344   59.33  5358.7   61.61
#Mann= 5 , 1 , 0
 4212.50      10       0  4299.9    0.12       0  4986.5   0.041       0
  5013.6    0.12       0  5330.9      10       0
Bank Sta=4986.50,5013.60
Exp/Cntr=0.3,0.1

Type RM Length L Ch R = 1 ,33391.5,581,581,581
XS GIS Cut Line= 3
   .603446092963   .349532805585   .598023617931   .319591313015
   .596962698903   .314876117335
BEGIN DESCRIPTION:
Wheat Swamp 37.0
END DESCRIPTION:
#Sta/Elev= 28
  4014.4   53.81  4184.4   51.92  4244.4   51.85  4264.4   51.36  4314.4   51.65
  4334.4   51.05  4354.4   51.84  4414.4    51.5  4454.4   49.89  4464.4    49.8
  4504.4   47.49  4554.4   46.98  4714.4   46.59  4854.4   46.16  4874.4   46.88
  4986.5   45.91  4988.5   41.91  5011.6   41.91  5013.6   45.91  5058.1   47.77
  5088.1   47.34  5098.1   48.27  5108.1   50.12  5118.1   52.81  5128.1   56.03
  5129.9   56.42  5148.1   60.35  5154.3   62.58
#Mann= 4 , 1 , 0
 4014.40    0.12       0  4986.5   0.041       0  5013.6    0.12       0
  5129.9      10       0
Bank Sta=4986.50,5013.60
Exp/Cntr=0.3,0.1

Type RM Length L Ch R = 1 ,32810.5,752.8,752.8,752.8
XS GIS Cut Line= 3
   .624546593632   .346467928393   .611692171263   .316601996330
   .606348838544   .308819316066
BEGIN DESCRIPTION:
Wheat Swamp 36.0
END DESCRIPTION:
#Sta/Elev= 13
  3947.7   54.35  4986.5   45.89  4988.5   41.89  5011.6   41.89  5013.6   45.89
  5058.8   47.82  5118.8   47.24  5188.8   49.67  5198.8   50.31  5237.9   56.21
  5238.8   56.35  5278.8   63.07  5288.8   64.23
#Mann= 4 , 1 , 0
 3947.70    0.12       0  4986.5   0.041       0  5013.6    0.12       0
  5237.9      10       0
Bank Sta=4986.50,5013.60
Exp/Cntr=0.3,0.1

Type RM Length L Ch R = 1 ,32057.7,752.8,752.8,752.8
XS GIS Cut Line= 3
   .636098823049   .338216335952   .633251357187   .315637873252
   .628082990392   .294718655803
BEGIN DESCRIPTION:
Wheat Swamp 35.0
END DESCRIPTION:
#Sta/Elev= 30
  4263.7   56.56  4344.9    54.8  4443.7   52.66  4773.7   51.24  4783.7   51.81
  4803.7    51.6  4823.7   50.93  4893.7   46.33  4903.7   46.71  4933.7   45.86
  4973.7   46.52  4986.4   45.45  4988.4   41.45  5011.5   41.45  5013.5   45.45
  5049.4   47.97  5089.4    47.7  5099.4   47.13  5279.4    46.4  5309.4   47.02
  5329.4    46.4  5349.4   47.16  5389.4    46.1  5479.4   46.45  5489.4   46.93
  5599.4   46.85  5619.4   49.13  5649.9   56.16  5669.4   59.93    5696   62.42
#Mann= 5 , 1 , 0
 4263.70      10       0  4344.9    0.12       0  4986.4   0.041       0
  5013.5    0.12       0  5649.9      10       0
Bank Sta=4986.40,5013.50
Exp/Cntr=0.3,0.1

Type RM Length L Ch R = 1 ,31304.9,1241.7,1241.7,1241.7
XS GIS Cut Line= 3
   .648004692141   .337155416924   .655313245446   .316762195607
   .662150279182   .296015334615
BEGIN DESCRIPTION:
Wheat Swamp 34.0
END DESCRIPTION:
#Sta/Elev= 27
  4303.2   55.06  4413.2   53.37  4419.9   53.46  4423.2    53.5  4593.2   50.64
  4723.2   49.23  4773.2   47.83  4803.2   47.81  4823.2   45.94  4863.2   47.33
  4893.2   46.05  4953.2   46.49  4984.6   44.28  4986.6   40.28  5013.5   40.28
  5015.5   44.28  5093.5   45.11  5123.5   44.22  5213.5   45.31  5483.5   44.87
  5523.5   45.22  5633.5   51.64  5653.5   53.02  5669.9      55  5673.5   55.44
  5693.5   56.83  5709.7   59.46
#Mann= 5 , 1 , 0
 4303.20      10       0  4419.9    0.12       0  4984.6   0.041       0
  5015.5    0.12       0  5669.9      10       0
Bank Sta=4984.60,5015.50
Exp/Cntr=0.3,0.1

Type RM Length L Ch R = 1 ,30063.2,549.4,549.4,549.4
XS GIS Cut Line= 3
   .666393955294   .346821568068   .679124983630   .335033578868
   .684193818987   .330082623404
BEGIN DESCRIPTION:
Wheat Swamp 33.0
END DESCRIPTION:
#Sta/Elev= 19
  4500.4   57.77  4510.4   56.81  4516.9   55.41  4520.4   54.65  4540.4   48.98
  4550.4   48.02  4870.4   45.64  4930.4   45.55  4984.6   43.48  4986.6   39.48
  5013.4   39.48  5015.4   43.48  5061.3    44.4  5081.3   43.76  5171.3   44.39
  5181.3   45.37  5191.3   46.87  5209.9    54.6  5230.3   63.07
#Mann= 5 , 1 , 0
 4500.40      10       0  4516.9    0.12       0  4984.6   0.041       0
  5015.4    0.12       0  5209.9      10       0
Bank Sta=4984.60,5015.40
Exp/Cntr=0.3,0.1

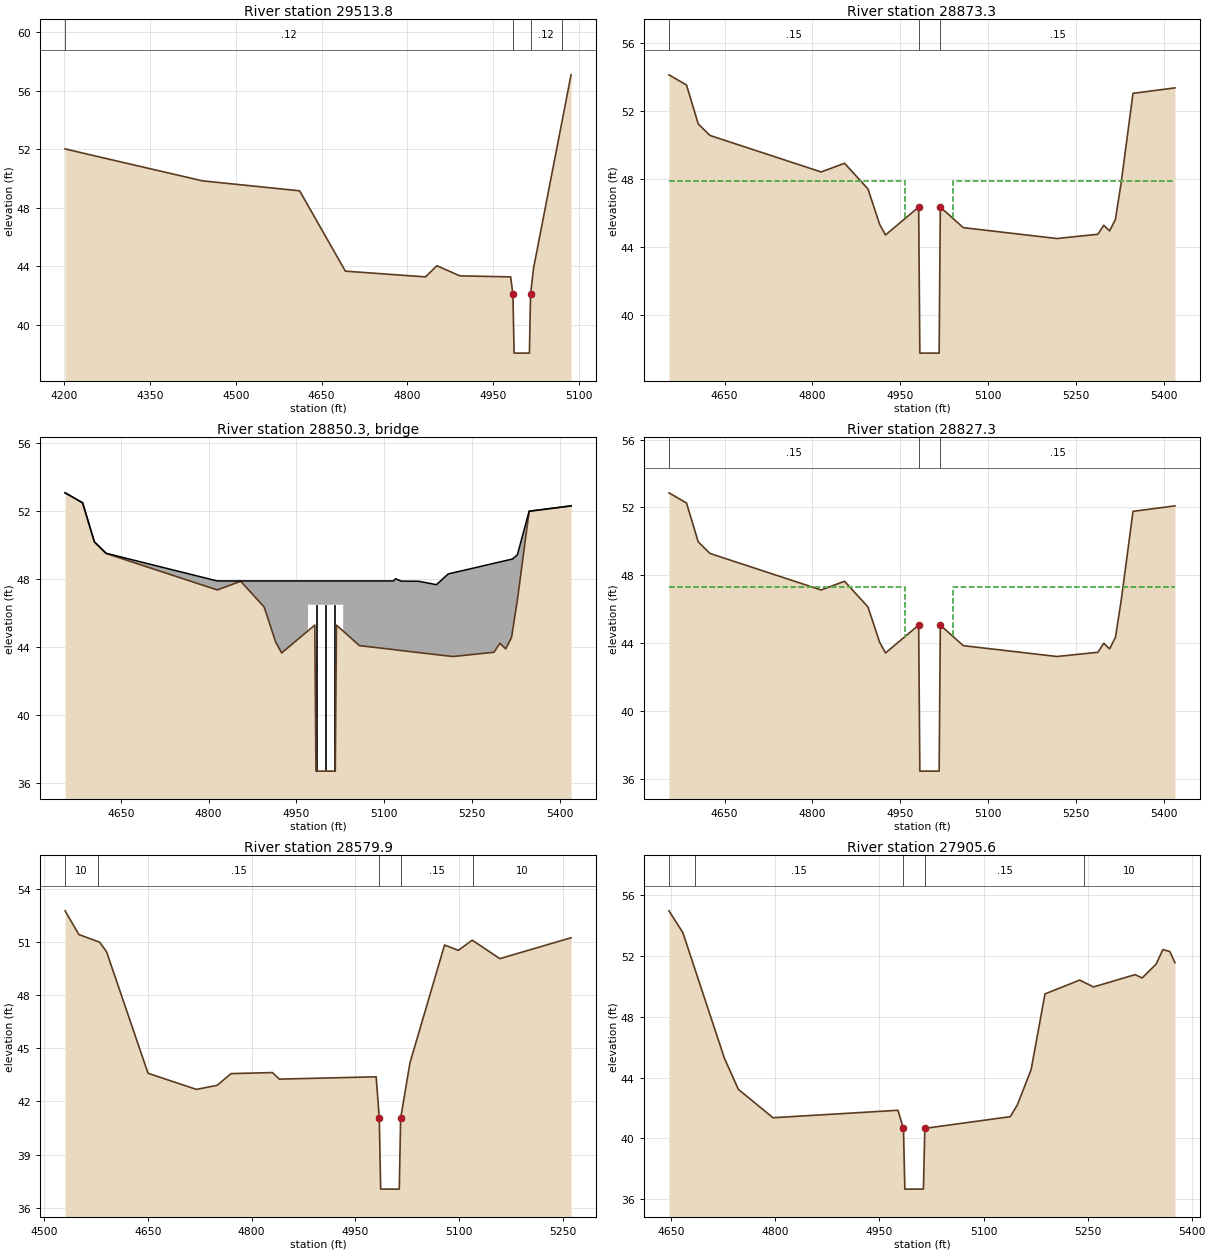
Type RM Length L Ch R = 1 ,29513.8,640.5,640.5,640.5
XS GIS Cut Line= 3
   .673584628706   .363324752949   .690323573371   .345996408825
   .693270570671   .344581850120
BEGIN DESCRIPTION:
Wheat Swamp 32.0
END DESCRIPTION:
#Sta/Elev= 16
  4201.7   52.02  4241.7   51.65  4441.7   49.84  4611.7   49.16  4691.7   43.68
  4831.7   43.29  4851.7   44.05  4891.7   43.36  4980.6   43.29  4984.6   42.09
  4986.6   38.09  5013.4   38.09  5015.4   42.09  5020.6   43.87  5069.9   53.79
  5086.2   57.07
#Mann= 4 , 1 , 0
 4201.70    0.12       0  4984.6   0.041       0  5015.4    0.12       0
  5069.9      10       0
Bank Sta=4984.60,5015.40
Exp/Cntr=0.5,0.3

Type RM Length L Ch R = 1 ,28873.3,46,46,46
XS GIS Cut Line= 4
   .690288402981   .378190509766   .695392465166   .367882726508
   .696282142329   .363712364805   .697768982737   .346892482683
BEGIN DESCRIPTION:
Upstream Section of Bridge/Culvert/Weir
END DESCRIPTION:
#Sta/Elev= 22
  4554.9   54.14  4584.9   53.54  4604.9   51.25  4624.9   50.57  4814.9   48.42
  4854.9   48.93  4894.9   47.42  4914.9   45.33  4924.9   44.71  4981.5   46.35
  4983.5   37.75  5016.5   37.75  5018.5   46.35  5057.7   45.14  5217.7    44.5
  5287.7   44.75  5297.7   45.28  5307.7   44.95  5317.7   45.63  5327.7   47.85
  5347.7   53.05  5419.3   53.37
#Mann= 3 , 1 , 0
 4554.90    0.15       0  4981.5    0.05       0  5018.5    0.15       0
#XS Ineff= 2 , 0
       0    4958    47.9    5040       0    47.9
Bank Sta=4981.50,5018.50
Exp/Cntr=0.5,0.3

Type RM Length L Ch R = 3 ,28850.3,,,
BEGIN DESCRIPTION:
Stocks Rd-TOR
Structure ID: Stocks Rd-Bridge
Approximate Survey Structure
END DESCRIPTION:
Bridge Culvert--1,0,-1,-1, 0
Deck Dist Width WeirC Skew NumUp NumDn MinLoCord MaxHiCord MaxSubmerge Is_Ogee
10,26,2.6,,38,38,,,0.95,0,1,1,,
  4554.9  4579.6  4584.9  4586.8  4604.9  4624.9  4814.9  4854.9  4894.9  4914.9
  4924.9 4969.91    4970    4977  4981.5  4983.5    5000  5016.5  5018.5    5023
 5029.89    5030  5057.7  5115.8  5119.3  5129.3  5159.3  5189.3  5209.3  5217.7
  5287.7  5297.7  5307.7  5317.7  5319.3  5327.7  5347.7  5419.3
   53.09   52.61    52.5   52.28   50.21   49.53    47.9    47.9    47.9    47.9
    47.9    47.9    47.9    47.9    47.9    47.9    47.9    47.9    47.9    47.9
    47.9    47.9    47.9    47.9   48.03   47.89   47.88   47.68   48.31   48.38
   48.94   49.02    49.1   49.18   49.19   49.45   52.01   52.32
   53.09    52.6   52.49   52.27    50.2   49.52   47.37   47.88   46.37   44.28
   43.66   44.96    46.5    46.5    46.5    46.5    46.5    46.5    46.5    46.5
    46.5   44.95   44.09   43.86   43.84    43.8   43.68   43.56   43.48   43.45
    43.7   44.23    43.9   44.58   44.94    46.8      52   52.32
  4554.9  4579.6  4584.9  4586.8  4604.9  4624.9  4814.9  4854.9  4894.9  4914.9
  4924.9 4969.91    4970    4977  4981.5  4983.5    5000  5016.5  5018.5    5023
 5029.89    5030  5057.7  5115.8  5119.3  5129.3  5159.3  5189.3  5209.3  5217.7
  5287.7  5297.7  5307.7  5317.7  5319.3  5327.7  5347.7  5419.3
   53.09   52.61    52.5   52.28   50.21   49.53    47.9    47.9    47.9    47.9
    47.9    47.9    47.9    47.9    47.9    47.9    47.9    47.9    47.9    47.9
    47.9    47.9    47.9    47.9   48.03   47.89   47.88   47.68   48.31   48.38
   48.94   49.02    49.1   49.18   49.19   49.45   52.01   52.32
   52.84   52.35   52.24   52.02   49.95   49.27   47.12   47.63   46.12   44.03
   43.41   44.71   46.25   46.25   46.25   46.25   46.25   46.25   46.25   46.25
   46.25    44.7   43.84   43.61   43.59   43.55   43.43   43.31   43.23    43.2
   43.45   43.98   43.65   44.33   44.69   46.55   51.75   52.07
Pier Skew, UpSta & Num, DnSta & Num=,4984.7, 2 ,4984.7, 2 , 0 , 0 , 0 ,,
       1       1
    35.7    47.5
       1       1
   35.45   47.25
Pier Skew, UpSta & Num, DnSta & Num=,5000.0, 2 ,5000.0, 2 , 0 , 0 , 0 ,,
       1       1
    35.7    47.5
       1       1
   35.45   47.25
Pier Skew, UpSta & Num, DnSta & Num=,5015.4, 2 ,5015.4, 2 , 0 , 0 , 0 ,,
       1       1
    35.7    47.5
       1       1
   35.45   47.25
Abutment Skew #Up #Dn=, 2 , 2
 4969.80 4977.00
   46.50   45.17
 4969.80 4977.00
   46.25   44.92
Abutment Skew #Up #Dn=, 2 , 2
 5023.00 5030.09
   45.16   46.50
 5023.00 5030.09
   44.91   46.25
BR Coef= 1 , 1 , 0 ,1.25, 0 ,,,0.8,0,2,0,
Wspro=,,,, 1 ,,,, 0 ,,,, 0 ,,,,-1 ,-1 ,-1 , 0 , 0 , 0 , 0 , 0
BC Design=,, 0 ,, 0 ,,,,,,
BR U #Sta/Elev= 38
  4554.9   53.09  4579.6    52.6  4584.9   52.49  4586.8   52.27  4604.9    50.2
  4624.9   49.52  4814.9   47.37  4854.9   47.88  4894.9   46.37  4914.9   44.28
  4924.9   43.66 4969.91   44.96    4970   44.97    4977   45.17  4981.5    45.3
  4983.5    36.7    5000    36.7  5016.5    36.7  5018.5    45.3    5023   45.16
 5029.89   44.95    5030   44.95  5057.7   44.09  5115.8   43.86  5119.3   43.84
  5129.3    43.8  5159.3   43.68  5189.3   43.56  5209.3   43.48  5217.7   43.45
  5287.7    43.7  5297.7   44.23  5307.7    43.9  5317.7   44.58  5319.3   44.94
  5327.7    46.8  5347.7      52  5419.3   52.32
BR U #Mann= 3
 4554.90    0.15  4981.5    0.05  5018.5    0.15
BR U Banks=4981.50,5018.50
BR D #Sta/Elev= 38
  4554.9   52.84  4579.6   52.35  4584.9   52.24  4586.8   52.02  4604.9   49.95
  4624.9   49.27  4814.9   47.12  4854.9   47.63  4894.9   46.12  4914.9   44.03
  4924.9   43.41 4969.91   44.71    4970   44.72    4977   44.92  4981.5   45.05
  4983.5   36.45    5000   36.45  5016.5   36.45  5018.5   45.05    5023   44.91
 5029.89    44.7    5030    44.7  5057.7   43.84  5115.8   43.61  5119.3   43.59
  5129.3   43.55  5159.3   43.43  5189.3   43.31  5209.3   43.23  5217.7    43.2
  5287.7   43.45  5297.7   43.98  5307.7   43.65  5317.7   44.33  5319.3   44.69
  5327.7   46.55  5347.7   51.75  5419.3   52.07
BR D #Mann= 3
 4554.90    0.15  4981.5    0.05  5018.5    0.15
BR D Banks=4981.50,5018.50

Type RM Length L Ch R = 1 ,28827.3,247.4,247.4,247.4
XS GIS Cut Line= 4
   .691537542681   .378872008270   .696641604866   .368564225011
   .697531282029   .364393863308   .699018122438   .347573981186
BEGIN DESCRIPTION:
Downstream Section of Bridge/Culvert/Weir
END DESCRIPTION:
#Sta/Elev= 22
  4554.9   52.86  4584.9   52.26  4604.9   49.97  4624.9   49.29  4814.9   47.14
  4854.9   47.65  4894.9   46.14  4914.9   44.05  4924.9   43.43  4981.5   45.07
  4983.5   36.47  5016.5   36.47  5018.5   45.07  5057.7   43.86  5217.7   43.22
  5287.7   43.47  5297.7      44  5307.7   43.67  5317.7   44.35  5327.7   46.57
  5347.7   51.77  5419.3   52.09
#Mann= 3 , 1 , 0
 4554.90    0.15       0  4981.5    0.05       0  5018.5    0.15       0
#XS Ineff= 2 , 0
       0    4958    47.3    5040       0    47.3
Bank Sta=4981.50,5018.50
Exp/Cntr=0.5,0.3

Type RM Length L Ch R = 1 ,28579.9,674.3,674.3,674.3
XS GIS Cut Line= 3
   .692681171211   .380063697614   .702818841923   .369690267117
   .709184356092   .364621431761
BEGIN DESCRIPTION:
Wheat Swamp 31.5
END DESCRIPTION:
#Sta/Elev= 23
  4530.1   52.76  4550.1   51.42  4577.9   51.02  4580.1   50.99  4590.1   50.45
  4650.1   43.59  4720.1   42.68  4750.1   42.91  4770.1   43.57  4830.1   43.63
  4840.1   43.26  4980.1   43.39  4984.6   41.05  4986.6   37.05  5013.5   37.05
  5015.5   41.05    5029   44.18    5079   50.83    5099   50.53    5119    51.1
  5119.9   51.08    5159   50.06    5262   51.24
#Mann= 5 , 1 , 0
 4530.10      10       0  4577.9    0.15       0  4984.6   0.045       0
  5015.5    0.15       0  5119.9      10       0
Bank Sta=4984.60,5015.50
Exp/Cntr=0.3,0.1

Type RM Length L Ch R = 1 ,27905.6,988.7,988.7,988.7
XS GIS Cut Line= 3
   .726276940432   .381124616642   .720265065940   .372047864958
   .711777713716   .364032032301
BEGIN DESCRIPTION:
Wheat Swamp 31.0
END DESCRIPTION:
#Sta/Elev= 24
  4646.6   54.98  4666.6   53.55  4683.9   51.16  4726.6   45.27  4746.6   43.23
  4796.6   41.36  4976.6   41.85  4984.6   40.66  4986.6   36.66  5013.4   36.66
  5015.4   40.66  5138.6   41.43  5148.6   42.19  5168.6   44.52  5188.6   49.51
  5238.6   50.42  5244.9   50.28  5258.6   49.97  5318.6   50.78  5328.6   50.56
  5348.6   51.46  5358.6   52.43  5368.6    52.3  5375.9   51.57
#Mann= 5 , 1 , 0
 4646.60      10       0  4683.9    0.15       0  4984.6   0.045       0
  5015.4    0.15       0  5244.9      10       0
Bank Sta=4984.60,5015.40
Exp/Cntr=0.3,0.1

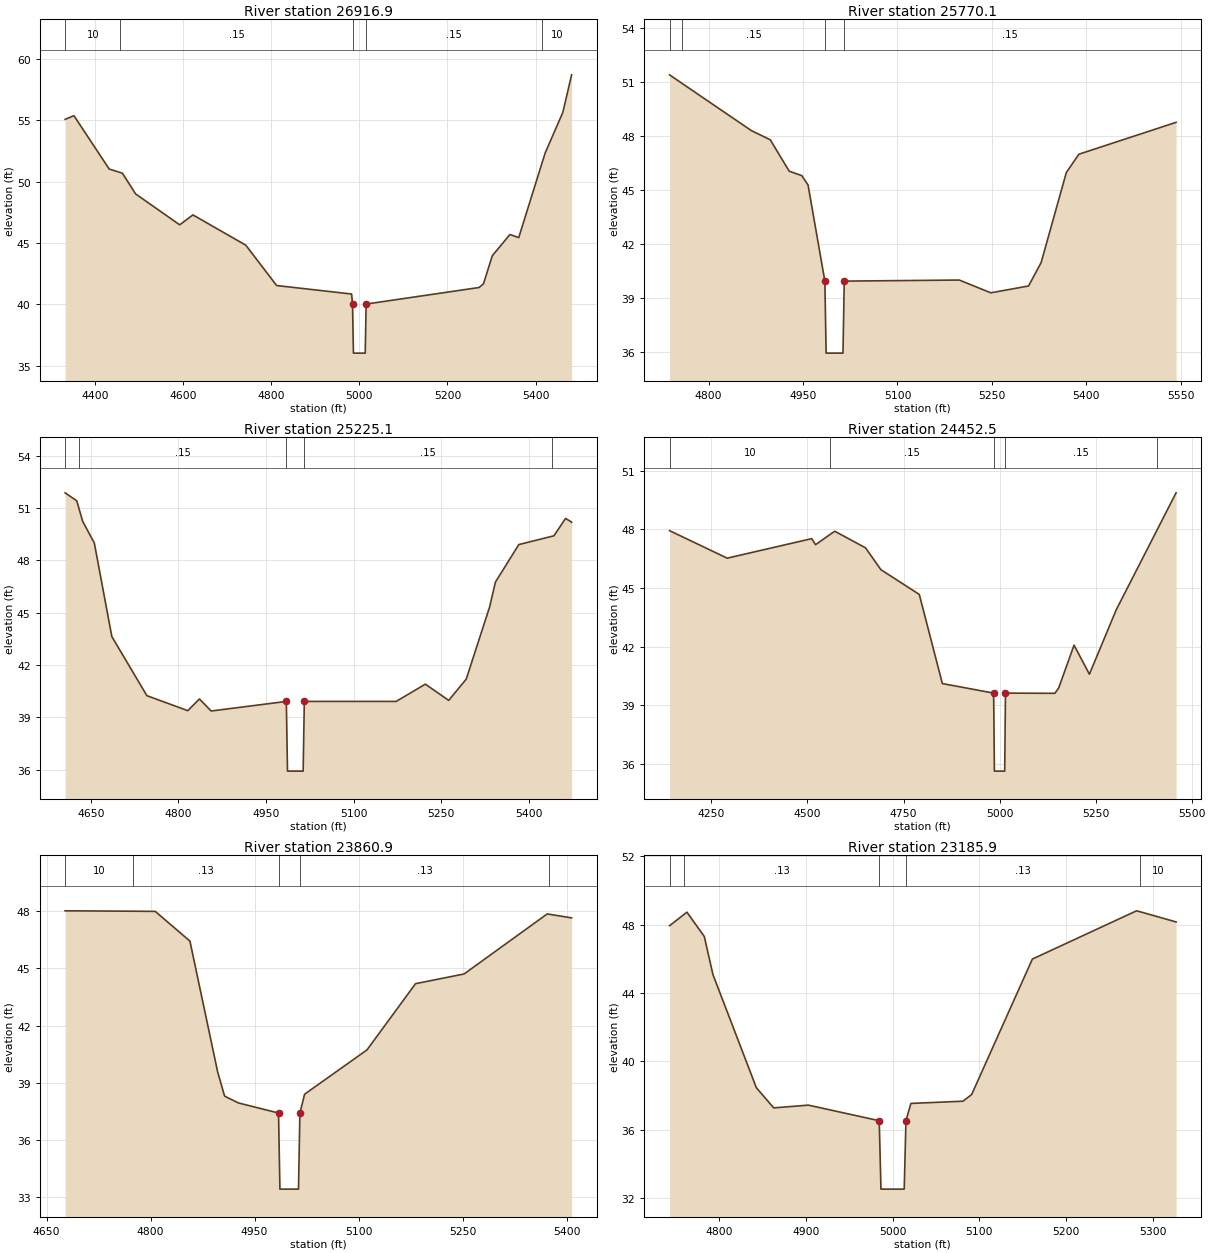
Type RM Length L Ch R = 1 ,26916.9,1146.8,1146.8,1146.8
XS GIS Cut Line= 3
   .728988177949   .373108783986   .736772620634   .353924013773
   .742308605745   .339630894656
BEGIN DESCRIPTION:
Wheat Swamp 30.0
END DESCRIPTION:
#Sta/Elev= 24
  4332.4   55.09  4352.4   55.39  4432.4   51.04  4457.9   50.75  4462.4    50.7
  4492.4   49.01  4592.4   46.49  4622.4    47.3  4742.4   44.83  4812.4   41.54
  4982.4   40.85  4984.6   40.03  4986.6   36.03  5013.4   36.03  5015.4   40.03
  5271.7   41.38  5281.7   41.68  5301.7   43.97  5341.7    45.7  5361.7   45.45
  5414.9   51.57  5421.7   52.35  5461.7   55.65  5481.7   58.72
#Mann= 5 , 1 , 0
 4332.40      10       0  4457.9    0.15       0  4984.6   0.045       0
  5015.4    0.15       0  5414.9      10       0
Bank Sta=4984.60,5015.40
Exp/Cntr=0.3,0.1

Type RM Length L Ch R = 1 ,25770.1,545,545,545
XS GIS Cut Line= 3
   .749410764107   .390537458834   .751267477537   .378295499234
   .754214474838   .362028074137
BEGIN DESCRIPTION:
Wheat Swamp 29.0
END DESCRIPTION:
#Sta/Elev= 18
  4737.9   51.38  4757.9    50.9  4867.9   48.28  4897.9   47.77  4927.9   46.03
  4947.9   45.78  4957.9   45.26  4984.6   39.92  4986.6   35.92  5013.4   35.92
  5015.4   39.92  5198.2   39.98  5248.2   39.27  5308.2   39.65  5328.2   40.95
  5368.2   45.95  5388.2   46.97  5542.6   48.74
#Mann= 4 , 1 , 0
 4737.90      10       0  4757.9    0.15       0  4984.6   0.045       0
  5015.4    0.15       0
Bank Sta=4984.60,5015.40
Exp/Cntr=0.3,0.1

Type RM Length L Ch R = 1 ,25225.1,772.6,772.6,772.6
XS GIS Cut Line= 3
   .759539864390   .392210154294   .765884584146   .374876982366
   .769303101014   .360731395325
BEGIN DESCRIPTION:
Wheat Swamp 28.0
END DESCRIPTION:
#Sta/Elev= 26
  4605.9   51.88  4625.9   51.42  4629.9   50.95  4635.9   50.25  4655.9      49
  4685.9   43.63  4745.9   40.24  4815.9   39.38  4835.9   40.05  4855.9   39.36
  4984.6   39.91  4986.6   35.91  5013.4   35.91  5015.4   39.91  5172.6   39.91
  5222.6    40.9  5262.6   39.97  5292.6   41.19  5332.6   45.33  5342.6   46.76
  5382.6   48.91  5439.9   49.39  5442.6   49.41  5462.6   50.41  5472.6   50.21
    5473   50.19
#Mann= 5 , 1 , 0
 4605.90      10       0  4629.9    0.15       0  4984.6   0.045       0
  5015.4    0.15       0  5439.9      10       0
Bank Sta=4984.60,5015.40
Exp/Cntr=0.3,0.1

Type RM Length L Ch R = 1 ,24452.5,591.6,591.6,591.6
XS GIS Cut Line= 3
   .775904374967   .404582715151   .787789832153   .380687141127
   .793232719091   .367686308953
BEGIN DESCRIPTION:
Wheat Swamp 27.0
END DESCRIPTION:
#Sta/Elev= 21
  4141.1   47.94  4291.1   46.53  4511.1   47.53  4521.1   47.22  4559.9   47.76
  4571.1   47.91  4651.1   47.06  4691.1   45.94  4791.1   44.67  4851.1    40.1
  4984.6   39.61  4986.6   35.61  5013.4   35.61  5015.4   39.61  5143.9    39.6
  5153.9   39.87  5193.9   42.07  5233.9   40.58  5303.9   43.89  5409.9   47.97
  5459.5   49.88
#Mann= 5 , 1 , 0
 4141.10      10       0  4559.9    0.15       0  4984.6   0.045       0
  5015.4    0.15       0  5409.9      10       0
Bank Sta=4984.60,5015.40
Exp/Cntr=0.3,0.1

Type RM Length L Ch R = 1 ,23860.9,675,675,675
XS GIS Cut Line= 3
   .800541272396   .399160240119   .803724029480   .389611968866
   .807260426240   .377588219882
BEGIN DESCRIPTION:
Wheat Swamp 26.0
END DESCRIPTION:
#Sta/Elev= 18
  4676.8   48.03  4774.9   48.01  4806.8      48  4856.8   46.44  4896.8   39.56
  4906.8   38.29  4926.8   37.93  4984.6    37.4  4986.6    33.4  5013.4    33.4
  5015.4    37.4  5022.2   38.39  5112.2   40.72  5182.2    44.2  5252.2   44.71
  5372.2   47.87  5374.9   47.85  5407.3   47.66
#Mann= 5 , 1 , 0
 4676.80      10       0  4774.9    0.13       0  4984.6   0.042       0
  5015.4    0.13       0  5374.9      10       0
Bank Sta=4984.60,5015.40
Exp/Cntr=0.3,0.1

Type RM Length L Ch R = 1 ,23185.9,824.3,824.3,824.3
XS GIS Cut Line= 3
   .812918661056   .408944271155   .819637814900   .400928438499
   .822466932308   .391262287355
BEGIN DESCRIPTION:
Wheat Swamp 25.0
END DESCRIPTION:
#Sta/Elev= 19
    4743   47.93  4759.9    48.6    4763   48.72    4783    47.3    4793   45.07
    4843   38.46    4863   37.28    4903   37.44  4984.6   36.53  4986.6   32.53
  5013.4   32.53  5015.4   36.53  5021.1   37.54  5081.1   37.67  5091.1   38.06
  5161.1   45.98  5281.1    48.8  5284.9   48.75  5326.7   48.15
#Mann= 5 , 1 , 0
 4743.00      10       0  4759.9    0.13       0  4984.6   0.042       0
  5015.4    0.13       0  5284.9      10       0
Bank Sta=4984.60,5015.40
Exp/Cntr=0.3,0.1

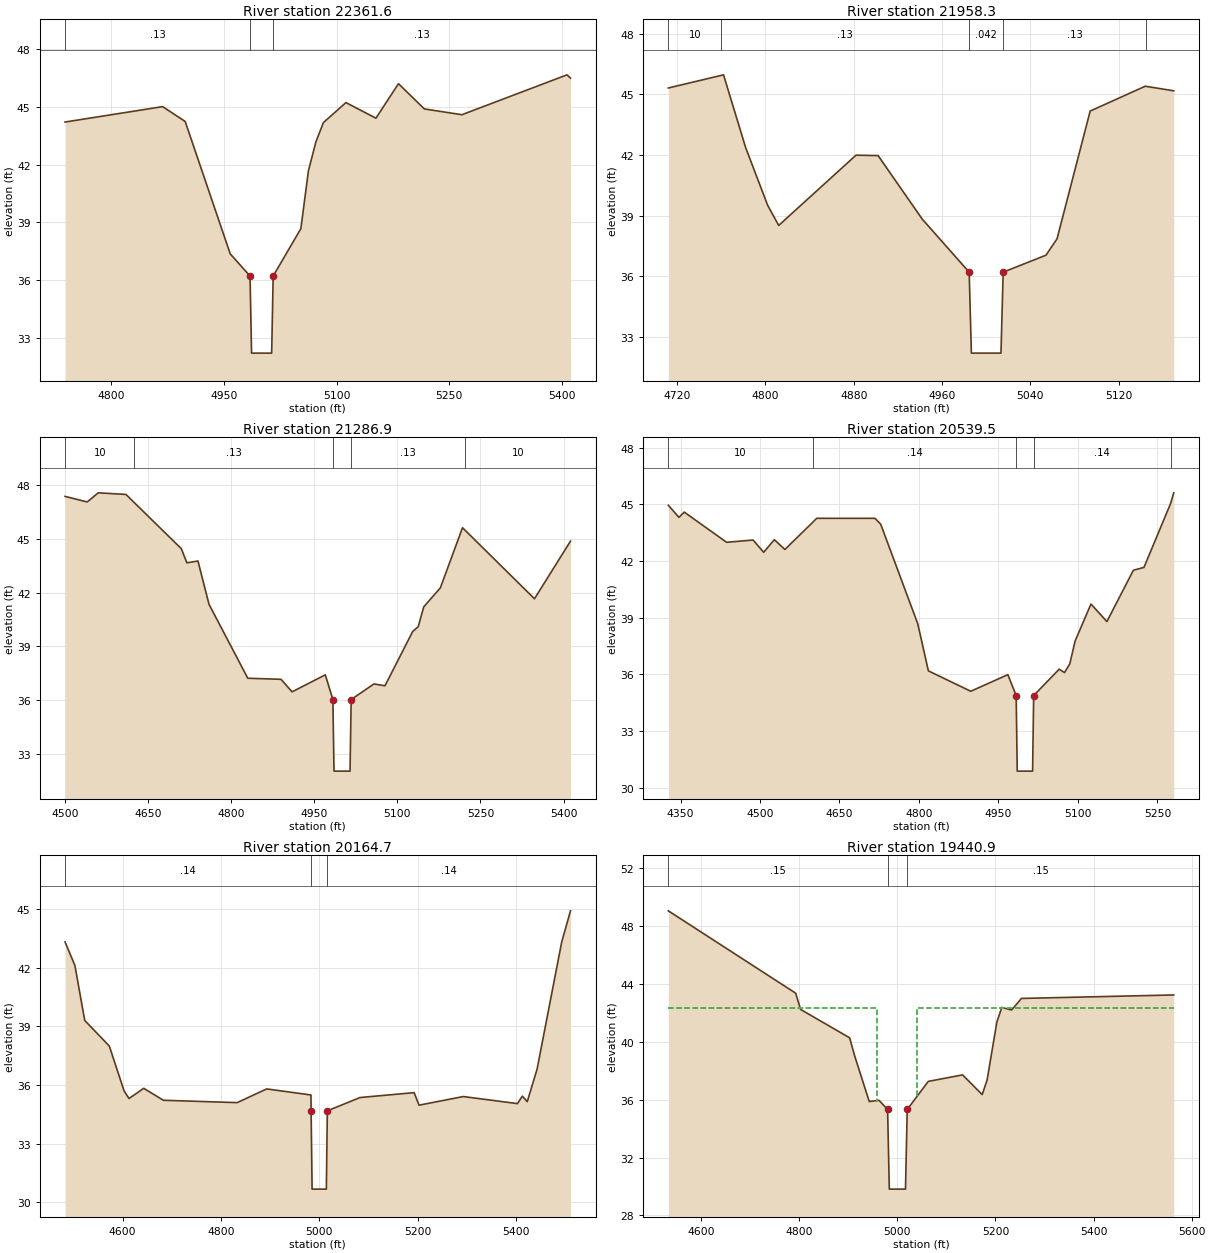
Type RM Length L Ch R = 1 ,22361.6,403.3,403.3,403.3
XS GIS Cut Line= 4
   .835433720429   .412009148347   .841209835137   .406233033639
   .844969171852   .400764907508   .846396550386   .394916564007
BEGIN DESCRIPTION:
Wheat Swamp 24.0
END DESCRIPTION:
#Sta/Elev= 19
  4738.2   44.21  4868.2   45.01  4898.2   44.24  4958.2   37.37  4984.6   36.22
  4986.6   32.22  5013.4   32.22  5015.4   36.22  5052.3   38.68  5062.3   41.67
  5072.3   43.18  5082.3   44.18  5112.3   45.22  5152.3   44.41  5182.3    46.2
  5216.8   44.89  5266.8   44.59  5406.8   46.66  5411.4   46.49
#Mann= 3 , 1 , 0
 4738.20    0.13       0  4984.6   0.042       0  5015.4    0.13       0
Bank Sta=4984.60,5015.40
Exp/Cntr=0.3,0.1

Type RM Length L Ch R = 1 ,21958.3,671.4,671.4,671.4
XS GIS Cut Line= 3
   .849932947146   .419317701652   .852408424878   .410948229319
   .854648142826   .405997273855
BEGIN DESCRIPTION:
Wheat Swamp 23.0
END DESCRIPTION:
#Sta/Elev= 19
  4712.1   45.31  4759.9   45.93  4762.1   45.96  4782.1   42.37  4802.1   39.51
  4812.1   38.52  4882.1   41.99  4902.1   41.97  4942.1   38.83  4984.6   36.21
  4986.6   32.21  5013.4   32.21  5015.4   36.21  5054.2   37.05  5064.2   37.86
  5094.2   44.17  5144.2    45.4  5144.9   45.39  5169.9   45.17
#Mann= 5 , 1 , 0
 4712.10      10       0  4759.9    0.13       0  4984.6   0.042       0
  5015.4    0.13       0  5144.9      10       0
Bank Sta=4984.60,5015.40
Exp/Cntr=0.3,0.1

Type RM Length L Ch R = 1 ,21286.9,747.4,747.4,747.4
XS GIS Cut Line= 3
   .858066659694   .424622296792   .870915567922   .416134944567
   .880110199499   .407176072775
BEGIN DESCRIPTION:
Wheat Swamp 22.0
END DESCRIPTION:
#Sta/Elev= 27
  4499.8   47.38  4539.8   47.07  4559.8   47.58  4609.8   47.49  4624.9   47.03
  4709.8   44.46  4719.8   43.67  4739.8   43.77  4759.8   41.35  4829.8   37.22
  4889.8   37.16  4909.8   36.46  4969.8   37.41  4983.5   36.03  4985.5   32.03
  5014.5   32.03  5016.5   36.03  5057.6    36.9  5077.6    36.8  5127.6   39.83
  5137.6    40.1  5147.6   41.21  5177.6   42.27  5217.6   45.63  5221.9    45.5
  5347.6   41.66  5412.6   44.88
#Mann= 5 , 1 , 0
 4499.80      10       0  4624.9    0.13       0  4983.5   0.042       0
  5016.5    0.13       0  5221.9      10       0
Bank Sta=4983.50,5016.50
Exp/Cntr=0.3,0.1

Type RM Length L Ch R = 1 ,20539.5,374.8,374.8,374.8
XS GIS Cut Line= 4
   .866313591231   .426686266268   .878106241335   .422854098412
   .886357833775   .422618338628   .895198825676   .422146819060
BEGIN DESCRIPTION:
Wheat Swamp 21.0
END DESCRIPTION:
#Sta/Elev= 30
    4327   44.95    4347   44.31    4357   44.59    4437   42.99    4487   43.11
    4507   42.46    4527   43.13    4547   42.61  4599.9   44.06    4607   44.26
    4717   44.26  4727.8   43.95  4797.8   38.67  4817.8   36.18  4897.8    35.1
  4967.8   35.98  4983.5   34.87  4985.5   30.87  5014.5   30.87  5016.5   34.87
  5064.7   36.27  5074.7   36.09  5084.7   36.55  5094.7   37.76  5124.7   39.72
  5154.7   38.79  5204.7   41.51  5224.7   41.66  5274.9   45.04  5280.9   45.61
#Mann= 5 , 1 , 0
 4327.00      10       0  4599.9    0.14       0  4983.5   0.044       0
  5016.5    0.14       0  5274.9      10       0
Bank Sta=4983.50,5016.50
Exp/Cntr=0.3,0.1

Type RM Length L Ch R = 1 ,20164.7,723.8,723.8,723.8
XS GIS Cut Line= 3
   .866685301333   .431611425121   .882761763251   .431983135223
   .898263702868   .434524207720
BEGIN DESCRIPTION:
Wheat Swamp 20.0
END DESCRIPTION:
#Sta/Elev= 25
  4483.2   43.31  4503.2   42.11  4523.2    39.3  4573.2   37.99  4603.2    35.7
  4613.2   35.31  4643.2   35.83  4683.2   35.22  4833.2    35.1  4893.2    35.8
  4983.2   35.49  4983.5   34.68  4985.5   30.68  5014.5   30.68  5016.5   34.68
    5083   35.36    5193   35.61    5203   34.97    5293   35.41    5403   35.05
    5413   35.43    5423   35.15    5443   36.81    5493    43.3  5510.9    44.9
#Mann= 3 , 1 , 0
 4483.20    0.14       0  4983.5   0.044       0  5016.5    0.14       0
Bank Sta=4983.50,5016.50
Exp/Cntr=0.5,0.3

Type RM Length L Ch R = 1 ,19440.9,46,46,46
XS GIS Cut Line= 6
   .870412478691   .455121619157   .878825026319   .451639161474
   .880504967453   .450836109778   .883326915360   .448792630259
   .886562023895   .445809107689   .896346054932   .437203875572
BEGIN DESCRIPTION:
Upstream Section of Bridge/Culvert/Weir
END DESCRIPTION:
#Sta/Elev= 20
  4532.9   49.04  4792.6   43.35  4802.6   42.23  4902.6   40.27  4912.6   39.05
  4942.6   35.87  4962.6   35.95    4980   35.32  4983.5   29.82  5016.5   29.82
    5020   35.32  5062.9   37.26  5132.9   37.71  5172.9   36.35  5182.9   37.36
  5202.9   41.37  5212.9   42.37  5232.9   42.19  5252.9   42.99  5563.5   43.23
#Mann= 3 , 1 , 0
 4532.90    0.15       0    4980    0.05       0    5020    0.15       0
#XS Ineff= 2 , 0
       0    4958    42.3    5040       0    42.3
Bank Sta=4980.00,5020.00
Exp/Cntr=0.5,0.3