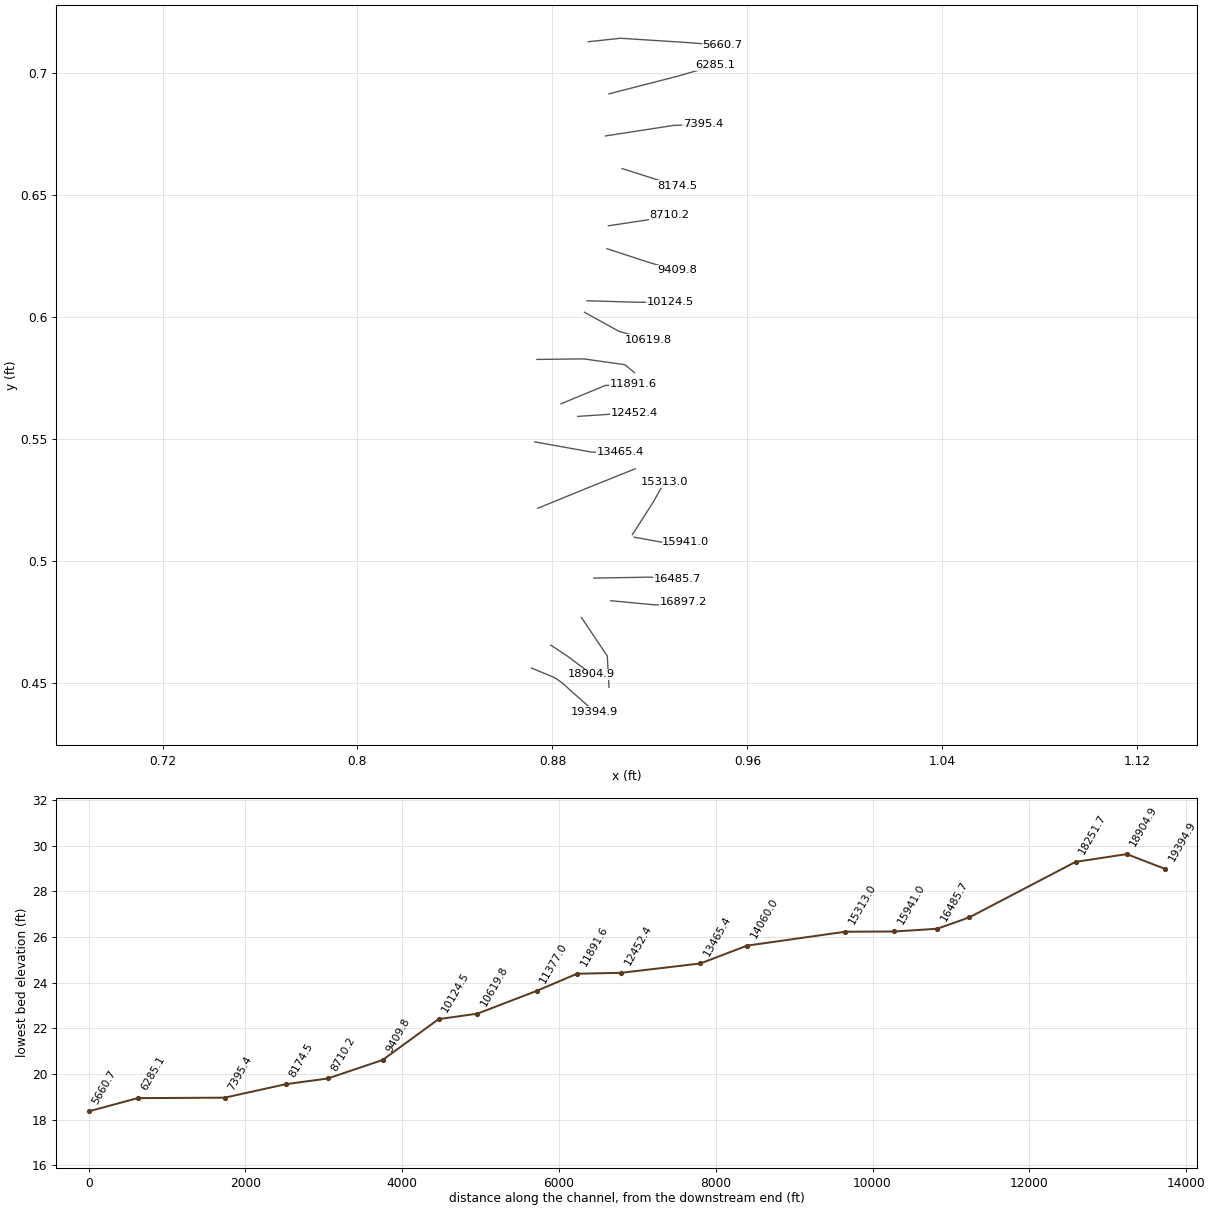
HEC-RAS study 2B CID37079C_DF_WHEAT SWAMP.PRJ: Wheat Swamp

--- 2B CID37079C_DF_WHEAT SWAMP.g01 (geometry) --- (continued)

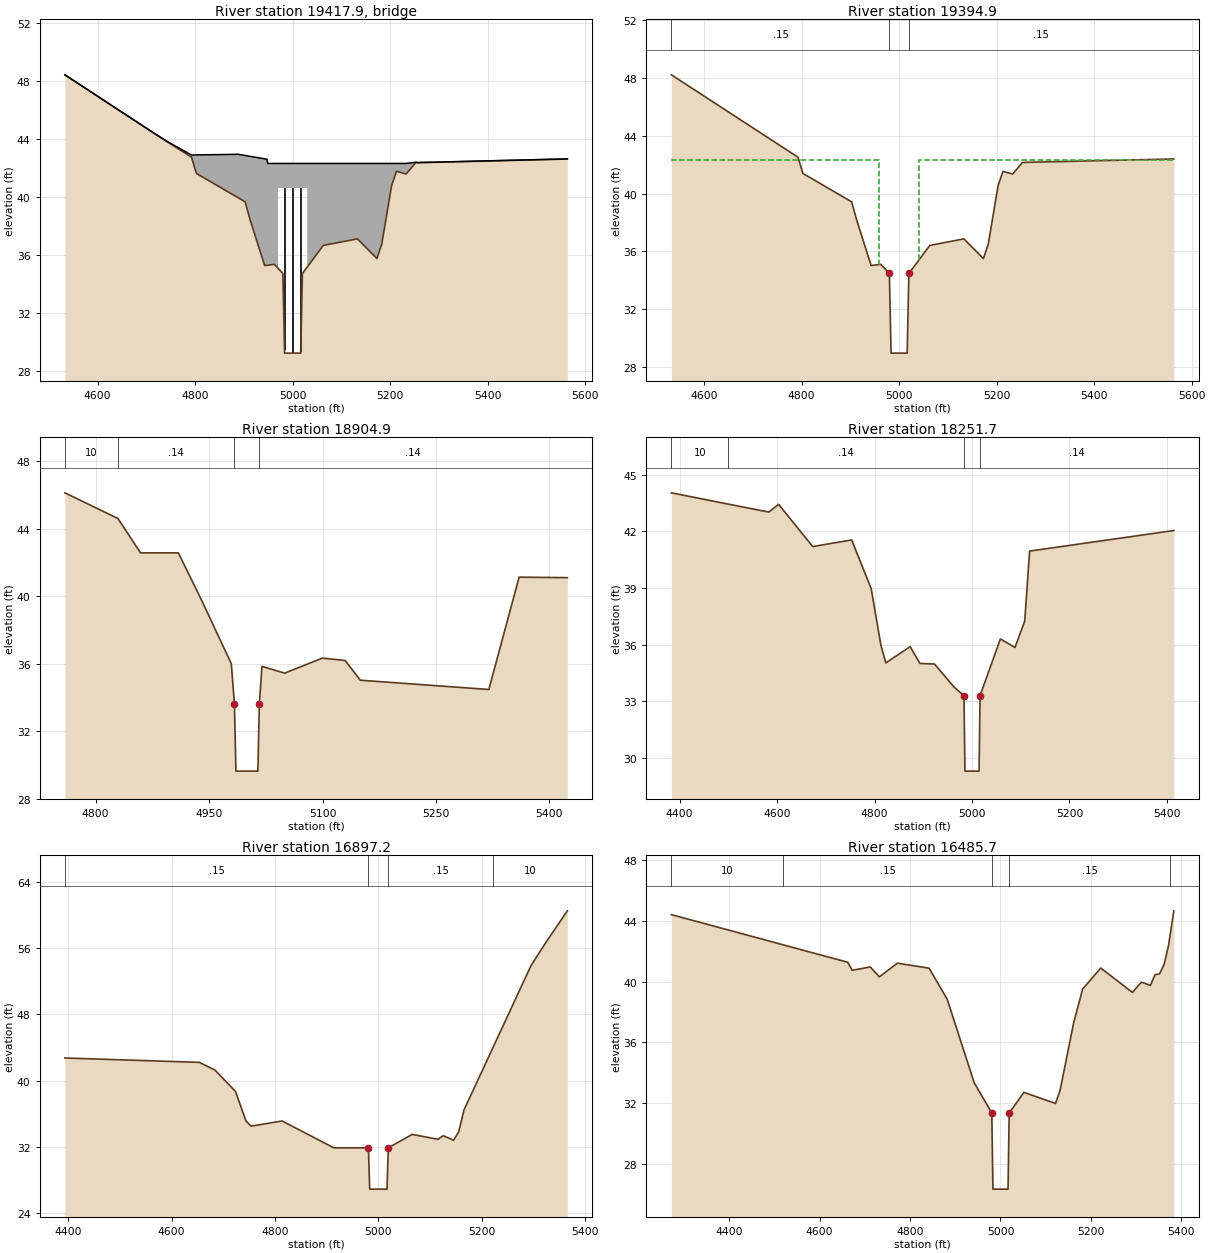
Type RM Length L Ch R = 3 ,19417.9,,,
BEGIN DESCRIPTION:
Oates Rd-TOR
Structure ID: Oates Rd-Bridge
Approximate Survey Structure
END DESCRIPTION:
Bridge Culvert--1,0,-1,-1, 0
Deck Dist Width WeirC Skew NumUp NumDn MinLoCord MaxHiCord MaxSubmerge Is_Ogee
10,26,2.6,,36,36,,,0.95,0,1,1,,
  4532.9  4712.6  4742.9  4792.6  4802.6  4887.2  4887.4  4902.6  4912.6  4942.6
  4947.4  4948.8  4962.6 4969.91    4970    4975    4980  4983.5    5000  5016.5
    5020    5025 5029.89    5030  5062.9  5132.9  5172.9  5182.9  5202.9  5212.9
  5232.9  5252.9  5256.3  5557.5  5562.3  5563.5
   48.42   44.46   43.81   42.88   42.89   42.93   42.94   42.85   42.79   42.62
   42.59    42.3    42.3    42.3    42.3    42.3    42.3    42.3    42.3    42.3
    42.3    42.3    42.3    42.3    42.3    42.3    42.3    42.3    42.3    42.3
    42.3   42.38   42.36   42.61   42.62   42.61
   48.42   44.45    43.8   42.73   41.61   39.95   39.95   39.65   38.43   35.25
   35.27   35.27   35.33   35.07    40.6    40.6    40.6    40.6    40.6    40.6
    40.6    40.6    40.6   35.15   36.64   37.09   35.73   36.74   40.75   41.75
   41.57   42.37   42.35    42.6   42.61   42.61
  4532.9  4712.6  4742.9  4792.6  4802.6  4887.2  4887.4  4902.6  4912.6  4942.6
  4947.4  4948.8  4962.6 4969.91    4970    4975    4980  4983.5    5000  5016.5
    5020    5025 5029.89    5030  5062.9  5132.9  5172.9  5182.9  5202.9  5212.9
  5232.9  5252.9  5256.3  5557.5  5562.3  5563.5
   48.42   44.46   43.81   42.88   42.89   42.93   42.94   42.85   42.79   42.62
   42.59    42.3    42.3    42.3    42.3    42.3    42.3    42.3    42.3    42.3
    42.3    42.3    42.3    42.3    42.3    42.3    42.3    42.3    42.3    42.3
    42.3   42.38   42.36   42.61   42.62   42.61
   48.17    44.2   43.55   42.48   41.36    39.7    39.7    39.4   38.18      35
   35.02   35.02   35.08   34.82   40.35   40.35   40.35   40.35   40.35   40.35
   40.35   40.35   40.35    34.9   36.39   36.84   35.48   36.49    40.5    41.5
   41.32   42.12    42.1   42.35   42.36   42.36
Pier Skew, UpSta & Num, DnSta & Num=,4983.3, 2 ,4983.3, 2 , 0 , 0 , 0 ,,
       1       1
    28.2    41.6
       1       1
   27.95   41.35
Pier Skew, UpSta & Num, DnSta & Num=,5000.0, 2 ,5000.0, 2 , 0 , 0 , 0 ,,
       1       1
    28.2    41.6
       1       1
   27.95   41.35
Pier Skew, UpSta & Num, DnSta & Num=,5016.6, 2 ,5016.6, 2 , 0 , 0 , 0 ,,
       1       1
    28.2    41.6
       1       1
   27.95   41.35
Abutment Skew #Up #Dn=, 2 , 2
 4969.80 4975.00
   40.60   34.88
 4969.80 4975.00
   40.35   34.63
Abutment Skew #Up #Dn=, 2 , 2
 5025.00 5030.09
   34.93   40.60
 5025.00 5030.09
   34.68   40.35
BR Coef= 1 , 1 , 0 ,1.25, 0 ,,,0.8,0,2,0,
Wspro=,,,, 1 ,,,, 0 ,,,, 0 ,,,,-1 ,-1 ,-1 , 0 , 0 , 0 , 0 , 0
BC Design=,, 0 ,, 0 ,,,,,,
BR U #Sta/Elev= 36
  4532.9   48.42  4712.6   44.45  4742.9    43.8  4792.6   42.73  4802.6   41.61
  4887.2   39.95  4887.4   39.95  4902.6   39.65  4912.6   38.43  4942.6   35.25
  4947.4   35.27  4948.8   35.27  4962.6   35.33 4969.91   35.07    4970   35.06
    4975   34.88    4980    34.7  4983.5    29.2    5000    29.2  5016.5    29.2
    5020    34.7    5025   34.93 5029.89   35.15    5030   35.15  5062.9   36.64
  5132.9   37.09  5172.9   35.73  5182.9   36.74  5202.9   40.75  5212.9   41.75
  5232.9   41.57  5252.9   42.37  5256.3   42.35  5557.5    42.6  5562.3   42.61
  5563.5   42.61
BR U #Mann= 3
 4532.90    0.15    4980    0.05    5020    0.15
BR U Banks=4980.00,5020.00
BR D #Sta/Elev= 36
  4532.9   48.17  4712.6    44.2  4742.9   43.55  4792.6   42.48  4802.6   41.36
  4887.2    39.7  4887.4    39.7  4902.6    39.4  4912.6   38.18  4942.6      35
  4947.4   35.02  4948.8   35.02  4962.6   35.08 4969.91   34.82    4970   34.81
    4975   34.63    4980   34.45  4983.5   28.95    5000   28.95  5016.5   28.95
    5020   34.45    5025   34.68 5029.89    34.9    5030    34.9  5062.9   36.39
  5132.9   36.84  5172.9   35.48  5182.9   36.49  5202.9    40.5  5212.9    41.5
  5232.9   41.32  5252.9   42.12  5256.3    42.1  5557.5   42.35  5562.3   42.36
  5563.5   42.36
BR D #Mann= 3
 4532.90    0.15    4980    0.05    5020    0.15
BR D Banks=4980.00,5020.00

Type RM Length L Ch R = 1 ,19394.9,490,490,490
XS GIS Cut Line= 6
   .871418657154   .456127797621   .879831204783   .452645339938
   .881511145917   .451842288241   .884333093823   .449798808723
   .887568202359   .446815286153   .897352233395   .438210054036
BEGIN DESCRIPTION:
Downstream Section of Bridge/Culvert/Weir
END DESCRIPTION:
#Sta/Elev= 20
  4532.9    48.2  4792.6   42.51  4802.6   41.39  4902.6   39.43  4912.6   38.21
  4942.6   35.03  4962.6   35.11    4980   34.48  4983.5   28.98  5016.5   28.98
    5020   34.48  5062.9   36.42  5132.9   36.87  5172.9   35.51  5182.9   36.52
  5202.9   40.53  5212.9   41.53  5232.9   41.35  5252.9   42.15  5563.5   42.39
#Mann= 3 , 1 , 0
 4532.90    0.15       0    4980    0.05       0    5020    0.15       0
#XS Ineff= 2 , 0
       0    4958    42.3    5040       0    42.3
Bank Sta=4980.00,5020.00
Exp/Cntr=0.5,0.3

Type RM Length L Ch R = 1 ,18904.9,653.2,653.2,653.2
XS GIS Cut Line= 3
   .879285040255   .465526619317   .885768434315   .461282943205
   .896023984919   .453620750225
BEGIN DESCRIPTION:
Wheat Swamp 19.0
END DESCRIPTION:
#Sta/Elev= 19
  4759.4   46.13  4829.4   44.61  4829.9   44.58  4859.4   42.57  4909.4   42.57
  4939.4   39.83  4979.4      36  4983.5   33.63  4985.5   29.63  5014.5   29.63
  5016.5   33.63  5019.9   35.84  5049.9   35.44  5099.9   36.33  5129.9   36.19
  5149.9   35.02  5319.9   34.47  5359.9   41.13  5423.7    41.1
#Mann= 4 , 1 , 0
 4759.40      10       0  4829.9    0.14       0  4983.5   0.043       0
  5016.5    0.14       0
Bank Sta=4983.50,5016.50
Exp/Cntr=0.3,0.1

Type RM Length L Ch R = 1 ,18251.7,1354.5,1354.5,1354.5
XS GIS Cut Line= 3
   .891898188699   .476843088950   .902507378980   .461047183421
   .903214658332   .448198275193
BEGIN DESCRIPTION:
Wheat Swamp 18.0
END DESCRIPTION:
#Sta/Elev= 22
  4383.1   44.05  4499.9   43.45  4583.1   43.03  4603.1   43.44  4673.1    41.2
  4753.1   41.55  4793.1   38.97  4813.1   35.96  4823.1   35.03  4873.1   35.89
  4893.1      35  4923.1   34.97  4963.1   33.75  4983.5   33.29  4985.5   29.29
  5014.5   29.29  5016.5   33.29  5058.2    36.3  5088.2   35.85  5108.2   37.25
  5118.2   40.96  5414.2   42.05
#Mann= 4 , 1 , 0
 4383.10      10       0  4499.9    0.14       0  4983.5   0.043       0
  5016.5    0.14       0
Bank Sta=4983.50,5016.50
Exp/Cntr=0.3,0.1

Type RM Length L Ch R = 1 ,16897.2,411.5,411.5,411.5
XS GIS Cut Line= 3
   .903894920397   .483728648148   .922424552692   .481969505841
   .933800339607   .483259543532
BEGIN DESCRIPTION:
Wheat Swamp 17.0
END DESCRIPTION:
#Sta/Elev= 22
  4393.7   42.73  4653.7    42.2  4683.7   41.28  4723.7   38.68  4743.7   35.13
  4753.7   34.48  4813.7   35.11  4913.7   31.86  4980.7   31.86  4983.2   26.86
  5016.7   26.86  5019.2   31.86  5065.4   33.48  5115.4   32.89  5125.4   33.33
  5145.4   32.78  5155.4   33.79  5165.4   36.42  5221.9   44.03  5295.4   53.93
  5325.4   56.85  5365.5   60.54
#Mann= 4 , 1 , 0
 4393.70    0.15       0  4980.7   0.045       0  5019.2    0.15       0
  5221.9      10       0
Bank Sta=4980.70,5019.20
Exp/Cntr=0.3,0.1

Type RM Length L Ch R = 1 ,16485.7,544.7,544.7,544.7
XS GIS Cut Line= 3
   .896975627326   .492993464295   .919547406307   .493376220145
   .931337540378   .492758911987
BEGIN DESCRIPTION:
Wheat Swamp 16.0
END DESCRIPTION:
#Sta/Elev= 29
    4272    44.4  4519.9   42.41    4662   41.27    4672   40.74    4712   40.96
    4732   40.31    4772   41.21    4842   40.88    4882   38.85    4942   33.34
  4980.8   31.36  4983.3   26.36  5016.7   26.36  5019.2   31.36  5051.8   32.72
  5121.8   31.99  5131.8   32.85  5161.8   37.28  5181.8   39.51  5221.8   40.89
  5291.8   39.29  5311.8   39.96  5331.8   39.75  5341.8   40.45  5351.8   40.51
  5361.8   41.11  5371.8   42.38  5374.9   42.98  5383.5   44.65
#Mann= 5 , 1 , 0
 4272.00      10       0  4519.9    0.15       0  4980.8   0.045       0
  5019.2    0.15       0  5374.9      10       0
Bank Sta=4980.80,5019.20
Exp/Cntr=0.3,0.1

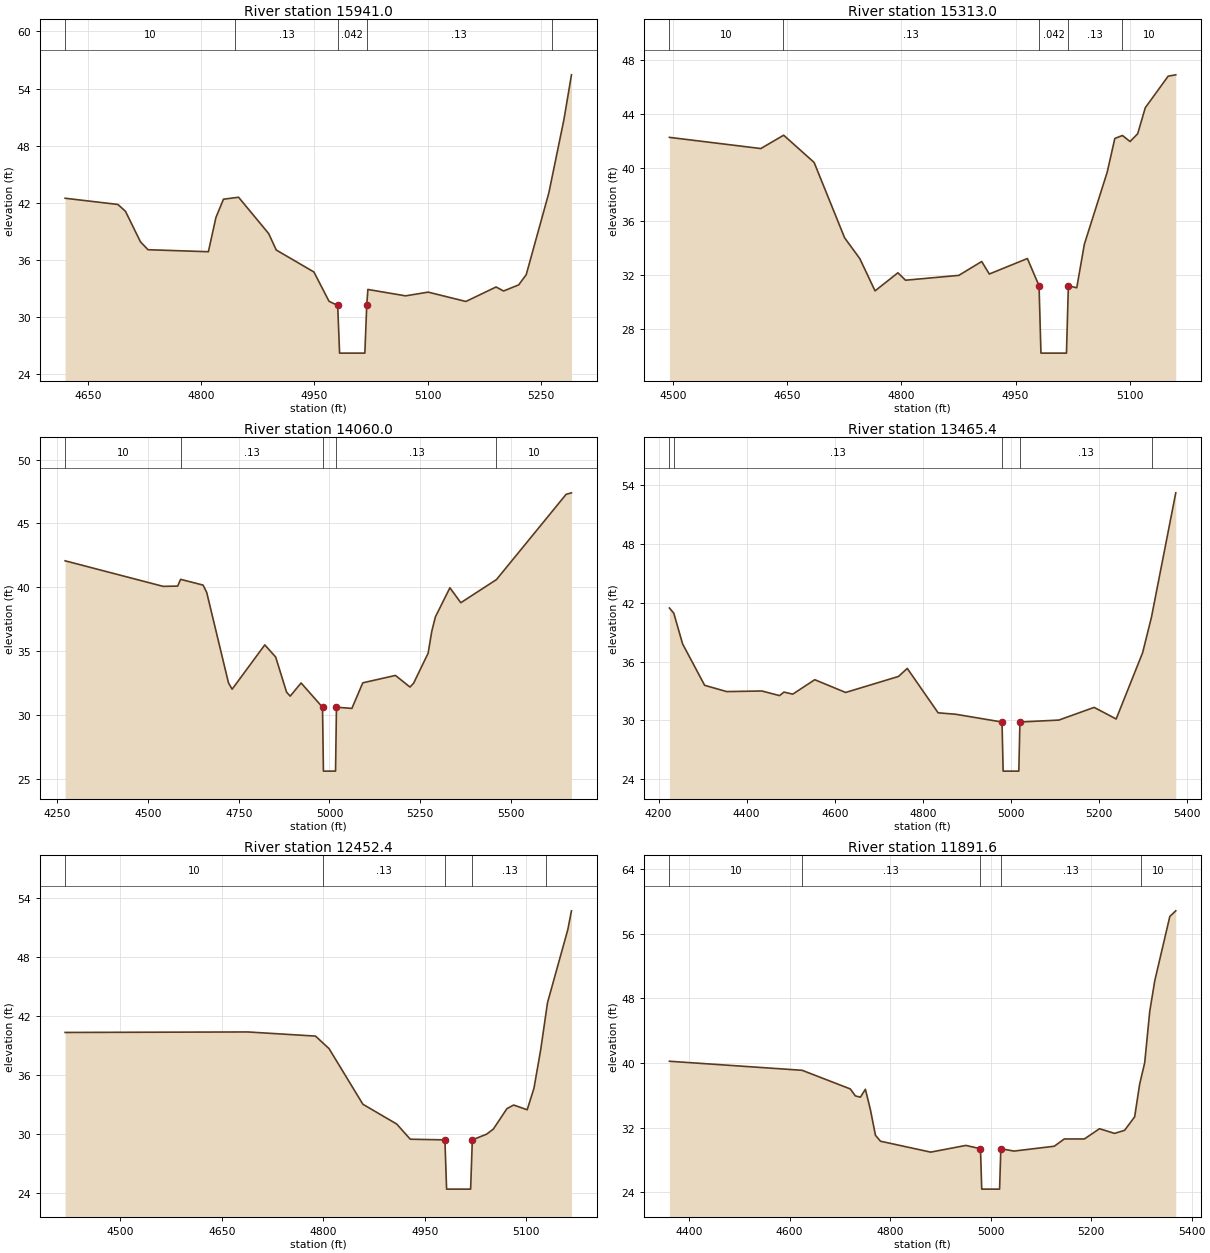
Type RM Length L Ch R = 1 ,15941.0,628,628,628
XS GIS Cut Line= 3
   .913511565006   .509763954283   .925121904228   .507652983515
   .934738548837   .507887535822
BEGIN DESCRIPTION:
Wheat Swamp 15.0
END DESCRIPTION:
#Sta/Elev= 30
  4619.3   42.49  4689.3   41.84  4699.3   41.13  4719.3   37.91  4729.3   37.09
  4809.3   36.88  4819.3   40.47  4829.3   42.39  4844.9   42.55  4849.3    42.6
  4889.3   38.78  4899.3   37.06  4949.3   34.75  4969.3   31.68  4980.8   31.24
  4983.3   26.24  5016.8   26.24  5019.3   31.24  5020.8   32.92  5070.8   32.25
  5100.8   32.64  5150.8   31.66  5190.8   33.18  5200.8   32.76  5220.8    33.4
  5230.8   34.47  5260.8   43.05  5264.9   44.63  5280.8   50.74  5290.8   55.44
#Mann= 5 , 1 , 0
 4619.30      10       0  4844.9    0.13       0  4980.8   0.042       0
  5019.3    0.13       0  5264.9      10       0
Bank Sta=4980.80,5019.30
Exp/Cntr=0.3,0.1

Type RM Length L Ch R = 1 ,15313.0,1253,1253,1253
XS GIS Cut Line= 3
   .912807908083   .510819439667   .921251791154   .523954368888
   .925942837305   .532280975805
BEGIN DESCRIPTION:
Wheat Swamp 14.0
END DESCRIPTION:
#Sta/Elev= 29
  4495.5   42.24  4615.5   41.41  4644.9   42.38  4645.5    42.4  4685.5   40.38
  4725.5   34.79  4745.5   33.24  4765.5   30.85  4795.5   32.19  4805.5   31.64
  4875.5      32  4905.5   33.03  4915.5    32.1  4965.5   33.25  4980.8   31.23
  4983.3   26.23  5016.8   26.23  5019.3   31.23  5030.3   31.08  5040.3   34.31
  5070.3   39.66  5080.3   42.16  5089.9   42.37  5090.3   42.38  5100.3   41.93
  5110.3   42.51  5120.3   44.44  5150.3   46.78  5160.3   46.88
#Mann= 5 , 1 , 0
 4495.50      10       0  4644.9    0.13       0  4980.8   0.042       0
  5019.3    0.13       0  5089.9      10       0
Bank Sta=4980.80,5019.30
Exp/Cntr=0.3,0.1

Type RM Length L Ch R = 1 ,14060.0,594.6,594.6,594.6
XS GIS Cut Line= 3
   .873989501188   .521608845812   .894893687562   .530139009228
   .913980669621   .537792955032
BEGIN DESCRIPTION:
Wheat Swamp 13.0
END DESCRIPTION:
#Sta/Elev= 30
  4271.8   42.08  4541.8   40.08  4581.8    40.1  4589.9   40.63  4651.8   40.18
  4661.8   39.61  4721.8   32.53  4731.8   32.03  4821.8    35.5  4851.8   34.55
  4881.8    31.8  4891.8   31.49  4921.8   32.52  4980.8   30.62  4983.3   25.62
  5016.7   25.62  5019.2   30.62  5061.7   30.53  5091.7   32.53  5181.7   33.11
  5221.7    32.2  5231.7    32.5  5271.7   34.85  5281.7   36.56  5291.7   37.69
  5331.7   39.97  5361.7    38.8  5459.9   40.61  5651.7   47.28  5666.5    47.4
#Mann= 5 , 1 , 0
 4271.80      10       0  4589.9    0.13       0  4980.8   0.042       0
  5019.2    0.13       0  5459.9      10       0
Bank Sta=4980.80,5019.20
Exp/Cntr=0.3,0.1

Type RM Length L Ch R = 1 ,13465.4,1013,1013,1013
XS GIS Cut Line= 3
   .872699463497   .548816913485   .896271970403   .544594971950
   .907882309625   .544594971950
BEGIN DESCRIPTION:
Wheat Swamp 12.0
END DESCRIPTION:
#Sta/Elev= 27
  4224.6   41.45  4234.6   40.92  4234.9   40.87  4254.6   37.79  4304.6   33.58
  4354.6   32.94  4434.6      33  4474.6   32.53  4484.6   32.89  4504.6   32.68
  4554.6   34.15  4624.6   32.85  4744.6   34.48  4764.6    35.3  4834.6   30.78
  4874.6   30.63  4979.7   29.84  4982.2   24.84  5017.8   24.84  5020.3   29.84
  5108.8   30.04  5188.8   31.33  5238.8   30.15  5298.8   36.89  5318.8   40.49
  5319.9   40.74  5374.1   53.18
#Mann= 5 , 1 , 0
 4224.60      10       0  4234.9    0.13       0  4979.7   0.042       0
  5020.3    0.13       0  5319.9      10       0
Bank Sta=4979.70,5020.30
Exp/Cntr=0.3,0.1

Type RM Length L Ch R = 1 ,12452.4,560.8,560.8,560.8
XS GIS Cut Line= 3
   .890408162715   .559254491170   .908396607722   .560455242879
   .913511565006   .560544528861
BEGIN DESCRIPTION:
Wheat Swamp 11.0
END DESCRIPTION:
#Sta/Elev= 23
  4418.6   40.34  4688.6   40.39  4788.6   39.97  4799.9   39.25  4808.6    38.7
  4858.6   33.05  4908.6   31.04  4928.6    29.5  4979.8   29.43  4982.3   24.43
  5017.8   24.43  5020.3   29.43  5041.4   30.01  5051.4   30.53  5071.4    32.6
  5081.4   32.97  5101.4   32.49  5111.4   34.68  5121.4   38.61  5129.9   42.65
  5131.4   43.36  5161.4   50.78  5166.8   52.69
#Mann= 5 , 1 , 0
 4418.60      10       0  4799.9    0.13       0  4979.8   0.042       0
  5020.3    0.13       0  5129.9      10       0
Bank Sta=4979.80,5020.30
Exp/Cntr=0.3,0.1

Type RM Length L Ch R = 1 ,11891.6,514.6,514.6,514.6
XS GIS Cut Line= 3
   .883488869643   .564414641936   .901666673476   .571920315776
   .913159736545   .572389420391
BEGIN DESCRIPTION:
Wheat Swamp 10.0
END DESCRIPTION:
#Sta/Elev= 30
  4360.8   40.22  4624.9    39.1  4720.8   36.79  4730.8   35.93  4740.8   35.77
  4750.8   36.75  4760.8   34.22  4770.8   31.06  4780.8   30.32  4880.8   28.97
  4950.8    29.8  4979.8   29.39  4982.3   24.39  5017.8   24.39  5020.3   29.39
  5046.6    29.1  5126.6    29.7  5146.6    30.6  5186.6    30.6  5216.6   31.87
  5246.6   31.29  5266.6   31.67  5286.6   33.34  5296.6    37.4  5299.9   38.27
  5306.6   40.04  5316.6   46.38  5326.6   50.18  5356.6   58.15  5368.4   58.84
#Mann= 5 , 1 , 0
 4360.80      10       0  4624.9    0.13       0  4979.8   0.042       0
  5020.3    0.13       0  5299.9      10       0
Bank Sta=4979.80,5020.30
Exp/Cntr=0.3,0.1

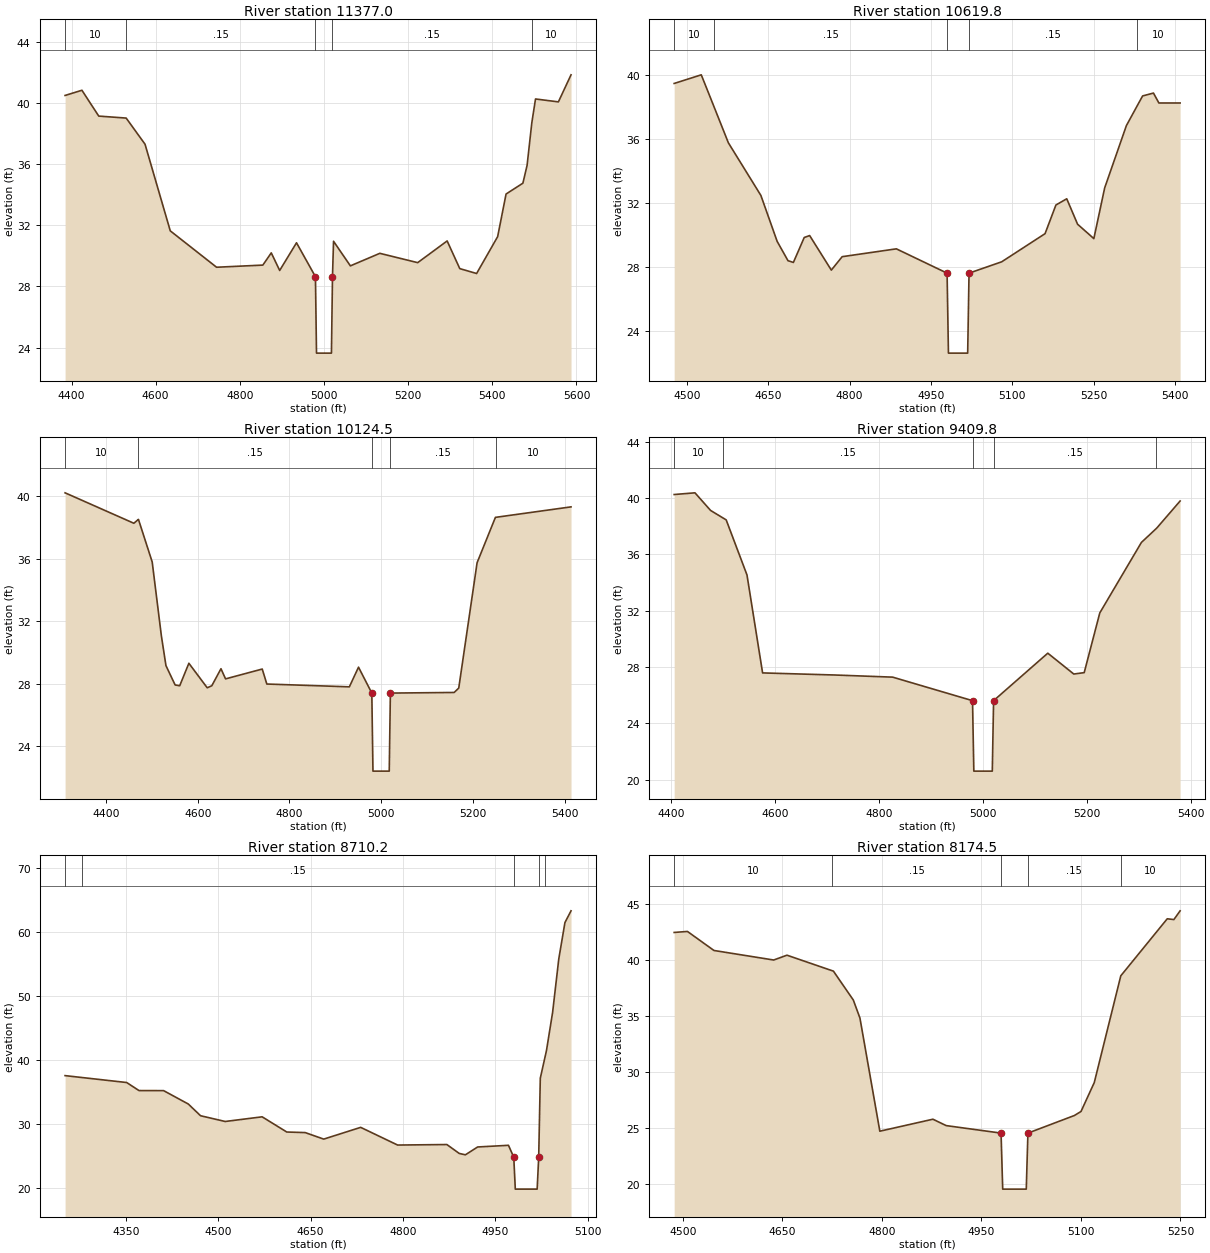
Type RM Length L Ch R = 1 ,11377.0,757.2,757.2,757.2
XS GIS Cut Line= 4
   .873637672727   .582592445769   .892753685790   .582826998076
   .909736663422   .580441656789   .913628841160   .577197742696
BEGIN DESCRIPTION:
Wheat Swamp 9.0
END DESCRIPTION:
#Sta/Elev= 30
  4384.7    40.5  4424.7   40.84  4464.7   39.15  4529.9   39.02  4574.7   37.31
  4634.7   31.64  4744.7   29.26  4854.7    29.4  4874.7    30.2  4894.7   29.05
  4934.7   30.86  4979.7   28.64  4982.2   23.64  5017.7   23.64  5020.2   28.64
  5022.7   30.96  5062.7   29.35  5132.7   30.17  5222.7   29.56  5292.7   30.98
  5322.7   29.17  5362.7   28.85  5412.7   31.26  5432.7   34.05  5472.7   34.76
  5482.7   35.93  5493.9   38.71  5502.7   40.27  5557.1   40.08  5587.1   41.85
#Mann= 5 , 1 , 0
 4384.70      10       0  4529.9    0.15       0  4979.7   0.045       0
  5020.2    0.15       0  5493.9      10       0
Bank Sta=4979.70,5020.20
Exp/Cntr=0.3,0.1

Type RM Length L Ch R = 1 ,10619.8,495.3,495.3,495.3
XS GIS Cut Line= 3
   .893151375283   .601922275115   .907351220355   .594081869860
   .919547406307   .590684360917
BEGIN DESCRIPTION:
Wheat Swamp 8.0
END DESCRIPTION:
#Sta/Elev= 30
  4476.2    39.5  4526.2   40.04  4549.9   38.03  4576.2   35.79  4636.2    32.5
  4666.2   29.63  4686.2   28.42  4696.2   28.31  4716.2   29.87  4726.2   29.99
  4766.2   27.83  4786.2   28.67  4886.2   29.16  4979.8   27.64  4982.3   22.64
  5017.8   22.64  5020.3   27.64  5080.6   28.35  5160.6   30.11  5180.6    31.9
  5200.6   32.29  5220.6    30.7  5250.6    29.8  5270.6   32.97  5310.6   36.86
  5329.9   38.06  5340.6   38.72  5360.6    38.9  5370.6   38.28  5409.8   38.28
#Mann= 5 , 1 , 0
 4476.20      10       0  4549.9    0.15       0  4979.8   0.045       0
  5020.3    0.15       0  5329.9      10       0
Bank Sta=4979.80,5020.30
Exp/Cntr=0.3,0.1

Type RM Length L Ch R = 1 ,10124.5,714.7,714.7,714.7
XS GIS Cut Line= 3
   .894160999635   .606634057290   .915452972452   .606016708970
   .928288360380   .606047676521
BEGIN DESCRIPTION:
Wheat Swamp 7.0
END DESCRIPTION:
#Sta/Elev= 28
  4310.7   40.23  4460.7   38.28  4469.9   38.51  4470.7   38.53  4500.7    35.8
  4520.7   31.07  4530.7   29.16  4550.7   27.92  4560.7   27.87  4580.7   29.31
  4620.7   27.74  4630.7   27.87  4650.7   28.96  4660.7   28.31  4740.7   28.94
  4750.7   27.98  4930.7    27.8  4950.7   29.06  4979.7    27.4  4982.2    22.4
  5017.7    22.4  5020.2    27.4  5159.3   27.44  5169.3   27.72  5209.3   35.75
  5249.3   38.66  5249.9   38.66  5414.2   39.33
#Mann= 5 , 1 , 0
 4310.70      10       0  4469.9    0.15       0  4979.7   0.045       0
  5020.2    0.15       0  5249.9      10       0
Bank Sta=4979.70,5020.20
Exp/Cntr=0.3,0.1

Type RM Length L Ch R = 1 ,9409.8,699.6,699.6,699.6
XS GIS Cut Line= 3
   .902370330398   .627978317274   .919961753463   .622231785740
   .931102988070   .619065329588
BEGIN DESCRIPTION:
Wheat Swamp 6.0
END DESCRIPTION:
#Sta/Elev= 21
  4406.2   40.24  4446.2   40.36  4476.2   39.11  4499.9   38.58  4506.2   38.44
  4546.2   34.53  4576.2   27.58  4716.2   27.43  4826.2   27.28  4979.8   25.61
  4982.3   20.61  5017.8   20.61  5020.3   25.61  5124.5   28.98  5174.5    27.5
  5194.5    27.6  5224.5   31.84  5304.5   36.84  5332.9   37.82  5334.5   37.88
  5378.9   39.78
#Mann= 5 , 1 , 0
 4406.20      10       0  4499.9    0.15       0  4979.8   0.045       0
  5020.3    0.15       0  5332.9      10       0
Bank Sta=4979.80,5020.30
Exp/Cntr=0.3,0.1

Type RM Length L Ch R = 1 ,8710.2,535.7,535.7,535.7
XS GIS Cut Line= 3
   .902956711167   .637360409575   .925645499283   .640775838933
   .927936531918   .641699627264
BEGIN DESCRIPTION:
Wheat Swamp 5.0
END DESCRIPTION:
#Sta/Elev= 30
  4251.2   37.57  4277.9   37.28  4351.2   36.49  4371.2   35.23  4411.2   35.22
  4451.2   33.13  4471.2   31.29  4511.2   30.39  4571.2   31.12  4611.2   28.74
  4641.2   28.65  4671.2   27.63  4731.2   29.47  4791.2    26.7  4871.2   26.78
  4891.2   25.39  4901.2   25.17  4921.2    26.4  4971.2   26.66  4979.8    24.8
  4982.3    19.8  5017.8    19.8  5020.3    24.8  5022.9   37.17  5029.9   40.19
  5032.9   41.48  5042.9   47.48  5052.9   55.83  5062.9   61.53  5072.8   63.37
#Mann= 5 , 1 , 0
 4251.20      10       0  4277.9    0.15       0  4979.8   0.045       0
  5020.3    0.15       0  5029.9      10       0
Bank Sta=4979.80,5020.30
Exp/Cntr=0.3,0.1

Type RM Length L Ch R = 1 ,8174.5,779.1,779.1,779.1
XS GIS Cut Line= 3
   .908585966548   .660815640328   .923714590383   .656007318023
   .931102988070   .653779071102
BEGIN DESCRIPTION:
Wheat Swamp 4.0
END DESCRIPTION:
#Sta/Elev= 24
    4487   42.46    4507   42.55    4547   40.85    4637      40    4657   40.43
  4724.9   39.05    4727   39.01    4757   36.43    4767   34.82    4797   24.72
    4877   25.79    4897   25.22  4979.7   24.55  4982.2   19.55  5017.7   19.55
  5020.2   24.55  5090.2   26.12  5100.2   26.48  5120.2   29.06  5159.9   38.52
  5160.2   38.59  5230.2   43.68  5240.2   43.61  5249.6   44.39
#Mann= 5 , 1 , 0
 4487.00      10       0  4724.9    0.15       0  4979.7   0.045       0
  5020.2    0.15       0  5159.9      10       0
Bank Sta=4979.70,5020.20
Exp/Cntr=0.3,0.1

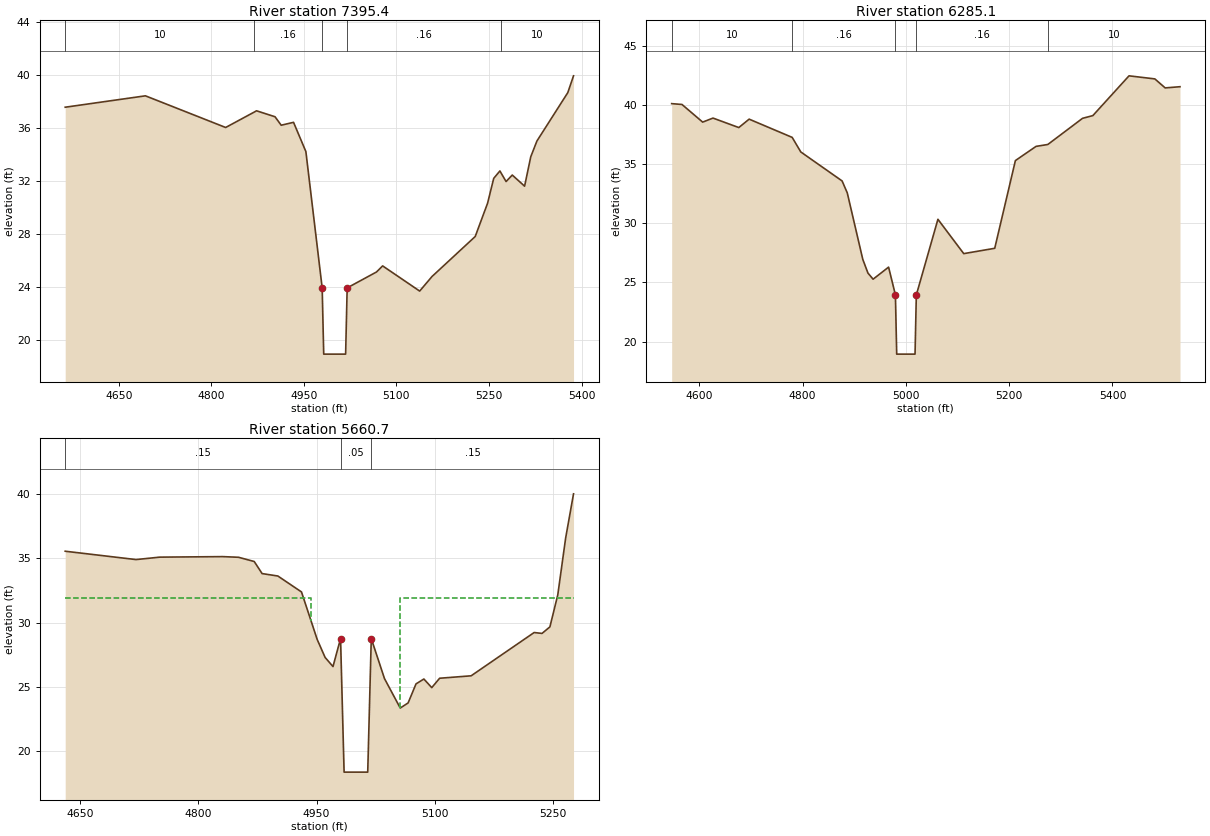
Type RM Length L Ch R = 1 ,7395.4,1110.3,1110.3,1110.3
XS GIS Cut Line= 3
   .901783949630   .674185121856   .929739933138   .678496899769
   .941775118063   .678876168007
BEGIN DESCRIPTION:
Wheat Swamp 3.0
END DESCRIPTION:
#Sta/Elev= 29
  4563.3    37.6  4693.3   38.46  4823.3   36.07  4869.9   37.24  4873.3   37.33
  4903.3   36.88  4913.3   36.24  4933.3   36.46  4953.3   34.25  4979.7   23.96
  4982.2   18.96  5017.7   18.96  5020.2   23.96  5067.7   25.16  5077.7   25.62
  5137.7   23.72  5157.7   24.82  5227.7   27.84  5247.7   30.35  5257.7   32.23
  5267.7   32.79  5269.9   32.61  5277.7   31.99  5287.7   32.48  5307.7   31.64
  5317.7   33.86  5327.7   35.05  5377.7    38.7    5387   39.97
#Mann= 5 , 1 , 0
 4563.30      10       0  4869.9    0.16       0  4979.7    0.05       0
  5020.2    0.16       0  5269.9      10       0
Bank Sta=4979.70,5020.20
Exp/Cntr=0.3,0.1

Type RM Length L Ch R = 1 ,6285.1,624.4,624.4,624.4
XS GIS Cut Line= 3
   .903191263475   .691424716460   .931220898575   .698620606589
   .946935268828   .703152331835
BEGIN DESCRIPTION:
Wheat Swamp 2.0
END DESCRIPTION:
#Sta/Elev= 30
  4546.6    40.1  4566.6   40.03  4606.6   38.54  4626.6   38.88  4676.6   38.08
  4696.6   38.79  4779.9   37.25  4796.6   36.02  4876.6   33.57  4886.6   32.56
  4916.6   26.95  4926.6   25.79  4936.6   25.27  4966.6   26.29  4979.8   23.94
  4982.3   18.94  5017.8   18.94  5020.3   23.94  5062.1   30.33  5112.1   27.43
  5172.1   27.88  5212.1   35.29  5252.1   36.49  5274.9   36.65  5342.1   38.86
  5362.1   39.09  5432.1   42.45  5482.1   42.19  5502.1   41.43  5530.8   41.53
#Mann= 5 , 1 , 0
 4546.60      10       0  4779.9    0.16       0  4979.8    0.05       0
  5020.3    0.16       0  5274.9      10       0
Bank Sta=4979.80,5020.30
Exp/Cntr=0.5,0.3

Type RM Length L Ch R = 1 ,5660.7,45,45,45
XS GIS Cut Line= 4
   .894728296516   .712790112946   .907973821211   .714210286392
   .934917625547   .712486393697   .949727279917   .711353890716
BEGIN DESCRIPTION:
Upstream Section of Bridge/Culvert/Weir
END DESCRIPTION:
#Sta/Elev= 30
  4630.9   35.56  4720.9   34.91  4750.9    35.1  4830.9   35.14  4850.9   35.09
  4870.9   34.76  4880.9   33.82  4900.9   33.63  4930.9   32.39  4950.9   28.68
  4960.9   27.29  4970.9   26.58  4980.5   28.76    4985   18.36    5015   18.36
  5019.5   28.76  5036.3   25.64  5056.3   23.35  5066.3   23.75  5076.3   25.23
  5086.3   25.61  5096.3   24.94  5106.3   25.67  5146.3   25.86  5226.3   29.23
  5236.3   29.16  5246.3   29.67  5256.3   32.16  5266.3   36.59  5276.3   40.03
#Mann= 3 , 1 , 0
 4630.90    0.15       0  4980.5    0.05       0  5019.5    0.15       0
#XS Ineff= 2 , 0
       0    4943    31.9    5056       0    31.9
Bank Sta=4980.50,5019.50
Exp/Cntr=0.5,0.3