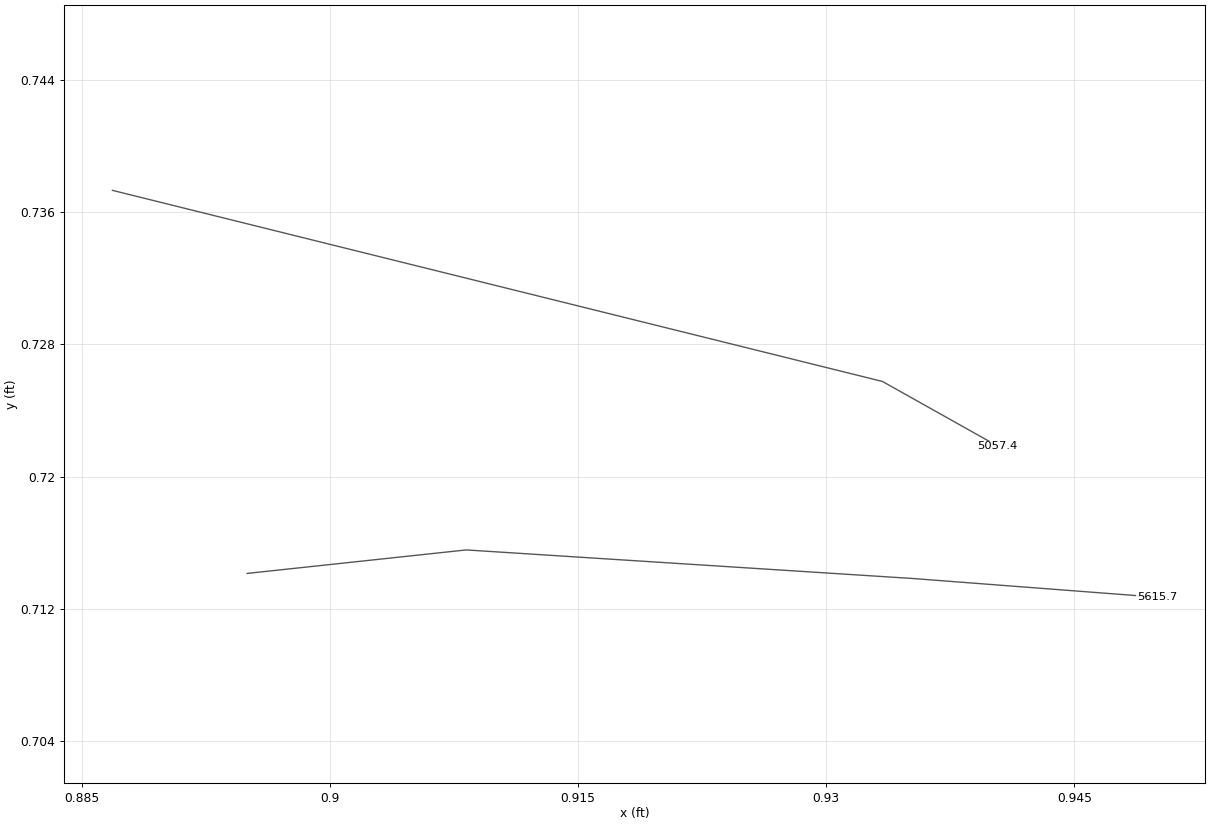
HEC-RAS study 2B CID37079C_DF_WHEAT SWAMP.PRJ: Wheat Swamp

--- 2B CID37079C_DF_WHEAT SWAMP.g01 (geometry) --- (continued)

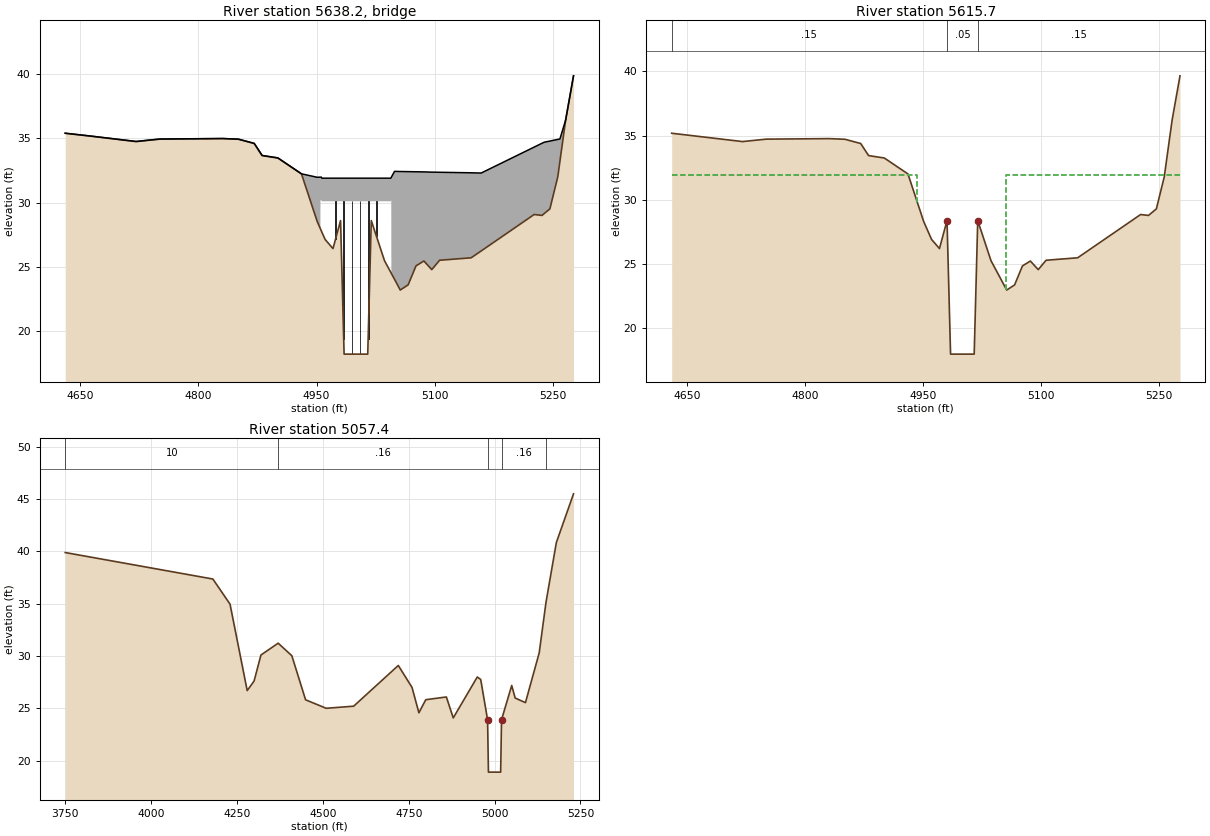
Type RM Length L Ch R = 3 ,5638.2,,,
BEGIN DESCRIPTION:
Hugo Rd-TOR
Structure ID: Hugo Rd-Bridge
Approximate Survey Structure
END DESCRIPTION:
Bridge Culvert--1,0,-1,-1, 0
Deck Dist Width WeirC Skew NumUp NumDn MinLoCord MaxHiCord MaxSubmerge Is_Ogee
10,25,2.6,,46,46,,,0.95,0,1,1,,
  4630.9  4656.2  4666.2  4720.9  4750.9  4830.9  4850.9  4870.9  4880.9  4900.9
  4930.9  4950.9 4954.91    4955  4956.2  4956.7  4960.9    4969  4970.9  4980.5
    4985    5000    5015  5019.5    5031  5036.3  5044.3 5044.89    5045    5049
  5056.3  5066.3  5076.3  5086.3  5096.3  5106.3  5146.3    5159  5226.3  5236.3
    5239  5246.3  5256.3    5259  5266.3  5276.3
    35.4   35.23   35.16   34.76   34.95   34.99   34.94   34.61   33.67   33.48
   32.24   31.97   31.98   31.98   31.98    31.9    31.9    31.9    31.9    31.9
    31.9    31.9    31.9    31.9    31.9    31.9    31.9   31.97   31.98   32.43
   32.42   32.41    32.4   32.39   32.37   32.36   32.32    32.3   34.32   34.62
    34.7   34.79   34.92   34.95   36.43   39.87
    35.4   35.22   35.15   34.75   34.94   34.98   34.93    34.6   33.66   33.47
   32.23   28.52   27.96   30.18   30.18    30.1    30.1    30.1    30.1    30.1
    30.1    30.1    30.1    30.1    30.1    30.1    30.1   30.17   24.48   24.03
   23.19   23.59   25.07   25.45   24.78   25.51    25.7   26.23   29.07      29
   29.14   29.51      32    33.2   36.43   39.87
  4630.9  4656.2  4666.2  4720.9  4750.9  4830.9  4850.9  4870.9  4880.9  4900.9
  4930.9  4950.9 4954.91    4955  4956.2  4956.7  4960.9    4969  4970.9  4980.5
    4985    5000    5015  5019.5    5031  5036.3  5044.3 5044.89    5045    5049
  5056.3  5066.3  5076.3  5086.3  5096.3  5106.3  5146.3    5159  5226.3  5236.3
    5239  5246.3  5256.3    5259  5266.3  5276.3
    35.4   35.23   35.16   34.76   34.95   34.99   34.94   34.61   33.67   33.48
   32.24   31.97   31.98   31.98   31.98    31.9    31.9    31.9    31.9    31.9
    31.9    31.9    31.9    31.9    31.9    31.9    31.9   31.97   31.98   32.43
   32.42   32.41    32.4   32.39   32.37   32.36   32.32    32.3   34.32   34.62
    34.7   34.79   34.92   34.95   36.43   39.87
   35.15   34.97    34.9    34.5   34.69   34.73   34.68   34.35   33.41   33.22
   31.98   28.27   27.71   29.93   29.93   29.85   29.85   29.85   29.85   29.85
   29.85   29.85   29.85   29.85   29.85   29.85   29.85   29.92   24.23   23.78
   22.94   23.34   24.82    25.2   24.53   25.26   25.45   25.98   28.82   28.75
   28.89   29.26   31.75   32.95   36.18   39.62
Pier Skew, UpSta & Num, DnSta & Num=,4974.2, 2 ,4974.2, 2 , 0 , 0 , 0 ,,
       1       1
   26.06    31.1
       1       1
   25.81   30.85
Pier Skew, UpSta & Num, DnSta & Num=,4984.5, 2 ,4984.5, 2 , 0 , 0 , 0 ,,
       1       1
    17.2    31.1
       1       1
   16.95   30.85
Pier Skew, UpSta & Num, DnSta & Num=,4994.9, 2 ,4994.9, 2 , 0 , 0 , 0 ,,
       1       1
    17.2    31.1
       1       1
   16.95   30.85
Pier Skew, UpSta & Num, DnSta & Num=,5005.2, 2 ,5005.2, 2 , 0 , 0 , 0 ,,
       1       1
    17.2    31.1
       1       1
   16.95   30.85
Pier Skew, UpSta & Num, DnSta & Num=,5015.5, 2 ,5015.5, 2 , 0 , 0 , 0 ,,
       1       1
    17.2    31.1
       1       1
   16.95   30.85
Pier Skew, UpSta & Num, DnSta & Num=,5025.9, 2 ,5025.9, 2 , 0 , 0 , 0 ,,
       1       1
   26.32    31.1
       1       1
   26.07   30.85
Abutment Skew #Up #Dn=, 2 , 2
 4954.80 4969.00
   30.18   26.55
 4954.80 4969.00
   29.93   26.30
Abutment Skew #Up #Dn=, 2 , 2
 5031.00 5045.09
   26.46   30.17
 5031.00 5045.09
   26.21   29.92
BR Coef= 1 , 1 , 0 ,1.25, 0 ,,,0.8,0,2,0,
Wspro=,,,, 1 ,,,, 0 ,,,, 0 ,,,,-1 ,-1 ,-1 , 0 , 0 , 0 , 0 , 0
BC Design=,, 0 ,, 0 ,,,,,,
BR U #Sta/Elev= 46
  4630.9    35.4  4656.2   35.22  4666.2   35.15  4720.9   34.75  4750.9   34.94
  4830.9   34.98  4850.9   34.93  4870.9    34.6  4880.9   33.66  4900.9   33.47
  4930.9   32.23  4950.9   28.52 4954.91   27.96    4955   27.95  4956.2   27.78
  4956.7   27.71  4960.9   27.13    4969   26.55  4970.9   26.42  4980.5    28.6
    4985    18.2    5000    18.2    5015    18.2  5019.5    28.6    5031   26.46
  5036.3   25.48  5044.3   24.56 5044.89    24.5    5045   24.48    5049   24.03
  5056.3   23.19  5066.3   23.59  5076.3   25.07  5086.3   25.45  5096.3   24.78
  5106.3   25.51  5146.3    25.7    5159   26.23  5226.3   29.07  5236.3      29
    5239   29.14  5246.3   29.51  5256.3      32    5259    33.2  5266.3   36.43
  5276.3   39.87
BR U #Mann= 3
 4630.90    0.15  4980.5    0.05  5019.5    0.15
BR U Banks=4980.50,5019.50
BR D #Sta/Elev= 46
  4630.9   35.15  4656.2   34.97  4666.2    34.9  4720.9    34.5  4750.9   34.69
  4830.9   34.73  4850.9   34.68  4870.9   34.35  4880.9   33.41  4900.9   33.22
  4930.9   31.98  4950.9   28.27 4954.91   27.71    4955    27.7  4956.2   27.53
  4956.7   27.46  4960.9   26.88    4969    26.3  4970.9   26.17  4980.5   28.35
    4985   17.95    5000   17.95    5015   17.95  5019.5   28.35    5031   26.21
  5036.3   25.23  5044.3   24.31 5044.89   24.25    5045   24.23    5049   23.78
  5056.3   22.94  5066.3   23.34  5076.3   24.82  5086.3    25.2  5096.3   24.53
  5106.3   25.26  5146.3   25.45    5159   25.98  5226.3   28.82  5236.3   28.75
    5239   28.89  5246.3   29.26  5256.3   31.75    5259   32.95  5266.3   36.18
  5276.3   39.62
BR D #Mann= 3
 4630.90    0.15  4980.5    0.05  5019.5    0.15
BR D Banks=4980.50,5019.50

Type RM Length L Ch R = 1 ,5615.7,558.3,558.3,558.3
XS GIS Cut Line= 4
   .895001016599   .714155153787   .908246541295   .715575327232
   .935190345630   .713851434537   .950000000000   .712718931556
BEGIN DESCRIPTION:
Downstream Section of Bridge/Culvert/Weir
END DESCRIPTION:
#Sta/Elev= 30
  4630.9   35.18  4720.9   34.53  4750.9   34.72  4830.9   34.76  4850.9   34.71
  4870.9   34.38  4880.9   33.44  4900.9   33.25  4930.9   32.01  4950.9    28.3
  4960.9   26.91  4970.9    26.2  4980.5   28.38    4985   17.98    5015   17.98
  5019.5   28.38  5036.3   25.26  5056.3   22.97  5066.3   23.37  5076.3   24.85
  5086.3   25.23  5096.3   24.56  5106.3   25.29  5146.3   25.48  5226.3   28.85
  5236.3   28.78  5246.3   29.29  5256.3   31.78  5266.3   36.21  5276.3   39.65
#Mann= 3 , 1 , 0
 4630.90    0.15       0  4980.5    0.05       0  5019.5    0.15       0
#XS Ineff= 2 , 0
       0    4943    31.9    5056       0    31.9
Bank Sta=4980.50,5019.50
Exp/Cntr=0.5,0.3

Type RM Length L Ch R = 1 ,5057.4,0,0,0
XS GIS Cut Line= 3
   .886861671144   .737309094172   .933406038757   .725757937247
   .940370706903   .721850928287
BEGIN DESCRIPTION:
Wheat Swamp 1.0
END DESCRIPTION:
#Sta/Elev= 30
  3749.7   39.89  4179.7   37.36  4229.7   34.96  4279.7    26.7  4299.7   27.61
  4319.7    30.1  4369.9   31.23  4409.7   30.03  4449.7   25.82  4509.7   25.01
  4589.7   25.21  4719.7    29.1  4759.7      27  4779.7   24.58  4799.7   25.83
  4859.7   26.09  4879.7   24.09  4949.7      28  4959.7   27.76  4979.7   23.91
  4982.2   18.91  5017.8   18.91  5020.3   23.91    5050   27.19    5060   25.99
    5090   25.55    5130    30.3  5149.9   35.15    5180   40.85    5230    45.5
#Mann= 5 , 1 , 0
 3749.70      10       0  4369.9    0.16       0  4979.7    0.05       0
  5020.3    0.16       0  5149.9      10       0
Bank Sta=4979.70,5020.30
Exp/Cntr=0.3,0.1

Chan Stop Cuts=-1