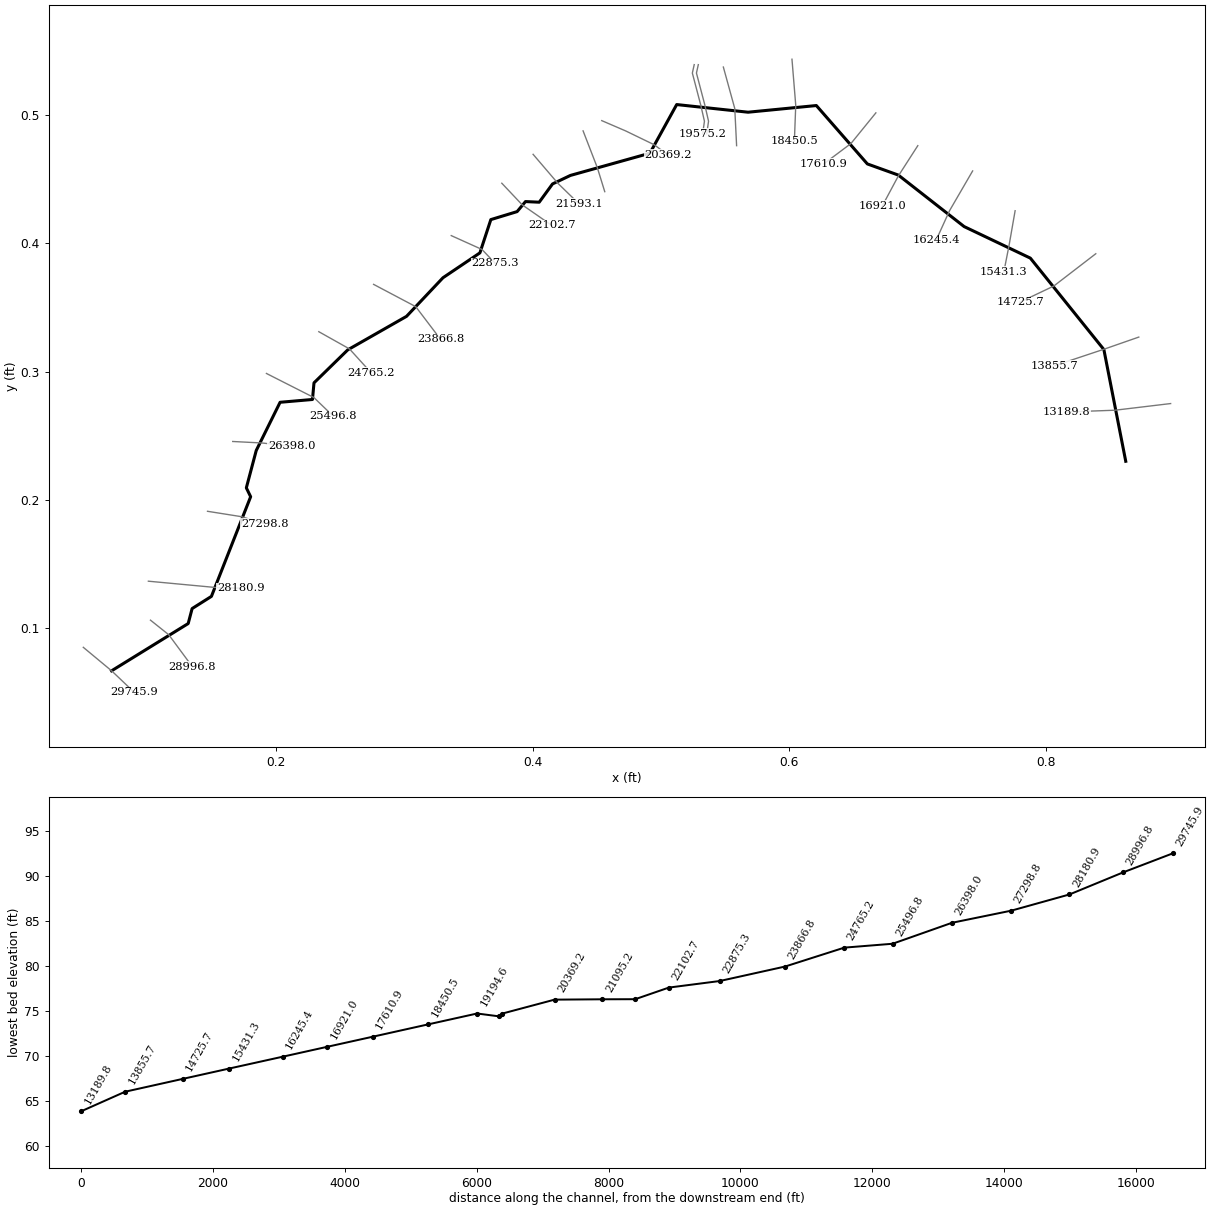
--- Apple_Tree_Swamp_FINAL.prj (project) ---

Proj Title=Apple Tree Swamp
Current Plan=p01
Default Exp/Contr=0.3,0.1
English Units
Geom File=g01
Flow File=f02
Flow File=f01
Plan File=p02
Plan File=p01
Y Axis Title=Elevation
X Axis Title(PF)=Main Channel Distance
X Axis Title(XS)=Station
BEGIN DESCRIPTION:
####(Watershed Name)####
APPLE TREE SWAMP
HCFCD Unit X###-##-##
(Flood Hazard, Floodway) Model
10, 2, 1, 0.2% Event
Filename:  N:\NC_flood\60138\Approximates\Eng\Toisnot_Nahunta\ENG\AppleTree_Swamp\Apple Tree Swamp.prj
Prepared by:  ________     Date: ________
Reviewed by:  ________     Date: ________
STATUS (Draft RAS, SVSQ, FINAL)
END DESCRIPTION:
DSS Export Rating Curves= 0
DSS Export Rating Curve Sorted= 0
DSS Export Volume Flow Curves= 0
DXF OffsetX= 0
DXF OffsetY= 0
DXF ScaleX= 1
DXF ScaleY= 10

--- Apple_Tree_Swamp_FINAL.p01 (plan) ---

Plan Title=100 Year Single
Program Version=4.00
Short Identifier=Plan01
Geom File=g01
Flow File=f01
Subcritical Flow
K Sum by GR= 0
Std Step Tol= 0.01
Critical Tol= 0.01
Num of Std Step Trials= 20
Max Error Tol= 0.3
Flow Tol Ratio= 0.001
Split Flow NTrial= 30
Split Flow Tol= 0.02
Split Flow Ratio= 0.02
Log Output Level= 0
Friction Slope Method= 1
Unsteady Friction Slope Method= 2
Unsteady Bridges Friction Slope Method= 1
Parabolic Critical Depth
Global Vel Dist= 0 , 0 , 0
Global Log Level= 0
CheckData=True
Encroach Param=-1 ,10,10, 2
Encroach River=Apple Tree Swamp
Encroach Reach=Reach - 1
Encroach Node=29745.9
       1    4910    5025
Encroach Node=28996.8
       1    4980    5100
Encroach Node=28180.9
       1    4800    5035
Encroach Node=27298.8
       4      .7
Encroach Node=26398.0
       4      .7
Encroach Node=25496.8
       4      .7
Encroach Node=24765.2
       4      .7
Encroach Node=23866.8
       1    4895    5123
Encroach Node=22875.3
       4      .7
Encroach Node=22102.7
       4      .7
Encroach Node=21593.1
       4      .7
Encroach Node=21095.2
       1    4865    5051
Encroach Node=20369.2
       1    4930    5020
Encroach Node=19575.2
       1    4962    5036
Encroach Node=19531.2
       1    4962    5036
Encroach Node=19194.6
       1    4925    5100
Encroach Node=18450.5
       4      .7
Encroach Node=17610.9
       1    4868    5075
Encroach Node=16921.0
       4      .7
Encroach Node=16245.4
       4      .7
Encroach Node=15431.3
       4      .7
Encroach Node=14725.7
       4      .7
Encroach Node=13855.7
       1    4865    5105
Encroach Node=13189.8
       1 4781.08 5216.87
Computation Interval=1HOUR
Output Interval=1HOUR
Run HTab= 0
Run UNet= 0
Run PostProcess= 0
Run WQNet= 0
UNET Theta= 1
UNET Theta Warmup= 1
UNET ZTol= 0.02
UNET ZSATol= 0.1
UNET MxIter= 20
UNET MaxInSteps= 20
UNET DtIC= 0
UNET DtMin= 0
UNET MaxCRTS= 20
UNET WFStab= 2
UNET SFStab= 1
UNET WFX= 1
UNET SFX= 1
UNET DSS MLevel= 4
UNET DZMax Abort= 100
UNET Convert EG Bridges=-1
UNET Use Existing IB Tables=-1
UNET Froude Reduction=False
UNET Froude Limit= 1
UNET Froude Power= 10
UNET Time Slicing=0,0, 5
Instantaneous Interval=1HOUR
Write IC File= 0
Echo Input=False
Echo Output=False
Write Detailed= 0
Detailed Automatic Start=False, 10
WQ ULTIMATE=-1
WQ Max Comp Step=1HOUR
WQ Output Interval=15MIN
WQ Output Selected Increments= 0
WQ Output face flow=0
WQ Output face velocity=0
WQ Output face area=0
WQ Output face dispersion=0
WQ Output cell volume=0
WQ Output cell surface area=0
WQ Output cell continuity=0
WQ Output face conc=0
WQ Output face dconc_dx=0
WQ Output face courant=0
WQ Output face peclet=0
WQ Output face adv mass=0
WQ Output face disp mass=0
WQ Output cell mass=0
WQ Output cell source sink temp=0
WQ Output cell source sink nsm=0
WQ Output MaxMinRange=-1
WQ Daily Max Min Mean=-1
WQ Daily Range=0
WQ Daily Time=0
WQ Create Restart=0
WQ Fixed Restart=0
WQ System Summary=False
Sorting and Armoring Iterations= 10
XS Update Threshold= 0.02
Hydraulics Update Threshold= 0.02
Energy Slope Method= 1
Volume Change Method= 0
XS Weighting Method= 0
Number of US Weighted Cross Sections= 1
Number of DS Weighted Cross Sections= 1
Upstream XS Weight=0.25
Main XS Weight=0.5
Downstream XS Weight=0.25
Number of DS XS's Weighted with US Boundary= 1
Upstream Boundary Weight= 1
Weight of XSs Associated with US Boundary= 0
Number of US XS's Weighted with DS Boundary= 1
Downstream Boundary Weight= 0.5
Weight of XSs Associated with DS Boundary= 0.5
Sediment Output Level= 4
Mass or Volume Output= 0
Output Increment Type= 1
Profile and TS Output Increment= 10
XS Output Flag= 0
XS Output Increment= 10
Disregard all LS=0
Disregard all Conn=0
Disregard all Breaches=0
Disregard all Pumps=0

--- Apple_Tree_Swamp_FINAL.p02 (plan) ---

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Plan Title=Multi_Profile
Short Identifier=Multi_Pro
Geom File=g01
Flow File=f02

--- Apple_Tree_Swamp_FINAL.f01 (steady flow) ---

Flow Title= 100 Year Single
Program Version=4.00
Number of Profiles= 2
Profile Names=100-Year,100-Year FW
River Rch & RM=Apple Tree Swamp,Reach - 1       ,29745.9
     510     510
River Rch & RM=Apple Tree Swamp,Reach - 1       ,27298.8
     827     827
River Rch & RM=Apple Tree Swamp,Reach - 1       ,23866.8
     878     878
River Rch & RM=Apple Tree Swamp,Reach - 1       ,22102.7
     937     937
River Rch & RM=Apple Tree Swamp,Reach - 1       ,19575.2
    1201    1201
River Rch & RM=Apple Tree Swamp,Reach - 1       ,16921
    1249    1249
River Rch & RM=Apple Tree Swamp,Reach - 1       ,14725.7
    1274    1274
River Rch & RM=Apple Tree Swamp,Reach - 1       ,13855.7
    1320    1320
Boundary for River Rch & Prof#=Apple Tree Swamp,Reach - 1       , 1
Up Type= 0
Dn Type= 1
Dn Known WS=73.24
Boundary for River Rch & Prof#=Apple Tree Swamp,Reach - 1       , 2
Up Type= 0
Dn Type= 1
Dn Known WS=73.54
DSS Import GetInterval= 0
DSS Import GetPeak= 0
DSS Import FillOption= 0

--- Apple_Tree_Swamp_FINAL.f02 (steady flow) ---

Flow Title=Multi_Profile
Program Version=4.00
Number of Profiles= 7
Profile Names=10-yr,25-yr,50-yr,500-yr,100-yr-10%,100-yr-20%,100-yr-35%
River Rch & RM=Apple Tree Swamp,Reach - 1       ,29745.9
     207     308     401     840     900    1154    1410
River Rch & RM=Apple Tree Swamp,Reach - 1       ,27298.8
     349     510     657    1330    1436    1840    2248
River Rch & RM=Apple Tree Swamp,Reach - 1       ,23866.8
     372     543     698    1407    1520    1948    2381
River Rch & RM=Apple Tree Swamp,Reach - 1       ,22102.7
     400     581     746    1497    1619    2074    2535
River Rch & RM=Apple Tree Swamp,Reach - 1       ,19575.2
     524     754     963    1897    2059    2638    3224
River Rch & RM=Apple Tree Swamp,Reach - 1       ,16921
     546     786    1002    1969    2138    2740    3348
River Rch & RM=Apple Tree Swamp,Reach - 1       ,14725.7
     558     802    1022    2006    2178    2792    3411
River Rch & RM=Apple Tree Swamp,Reach - 1       ,13855.7
     582     835    1063    2081    2261    2898    3541
Boundary for River Rch & Prof#=Apple Tree Swamp,Reach - 1       , 1
Up Type= 0
Dn Type= 1
Dn Known WS=71.95
Boundary for River Rch & Prof#=Apple Tree Swamp,Reach - 1       , 2
Up Type= 0
Dn Type= 1
Dn Known WS=72.39
Boundary for River Rch & Prof#=Apple Tree Swamp,Reach - 1       , 3
Up Type= 0
Dn Type= 1
Dn Known WS=72.88
Boundary for River Rch & Prof#=Apple Tree Swamp,Reach - 1       , 4
Up Type= 0
Dn Type= 1
Dn Known WS=73.97
Boundary for River Rch & Prof#=Apple Tree Swamp,Reach - 1       , 5
Up Type= 0
Dn Type= 1
Dn Known WS=74.17
Boundary for River Rch & Prof#=Apple Tree Swamp,Reach - 1       , 6
Up Type= 0
Dn Type= 1
Dn Known WS=74.7
Boundary for River Rch & Prof#=Apple Tree Swamp,Reach - 1       , 7
Up Type= 0
Dn Type= 1
Dn Known WS=75.1
DSS Import GetInterval= 0
DSS Import GetPeak= 0
DSS Import FillOption= 0

--- Apple_Tree_Swamp_FINAL.g01 (geometry) ---

Geom Title=Geom 01 by CodeH2 for Windows
Program Version=4.00

River Reach=Apple Tree Swamp,Reach - 1
Reach XY= 30
       0.0720282       0.0668948       0.1316931       0.1037004
       0.1347585       0.1153691        0.149789       0.1248617
       0.1803439        0.202485       0.1769821        0.209407
       0.1846946       0.2384783       0.2032845       0.2760541
       0.2284999       0.2782294       0.2296864       0.2911833
       0.2559895       0.3168929       0.3017726       0.3429976
       0.3301515       0.3730585       0.3589264       0.3924397
       0.3674309       0.4183468       0.3878996       0.4245764
       0.3944257       0.4323884       0.4051054       0.4318936
       0.4154881       0.4461328       0.4294301       0.4527584
       0.4913313        0.470063       0.5122077       0.5079534
       0.5678052       0.5019977       0.6209774       0.5071919
       0.6607198       0.4617089       0.6848454       0.4530287
       0.7361039       0.4129106       0.7876697       0.3883411
       0.8449426       0.3171261       0.8619791        0.230103

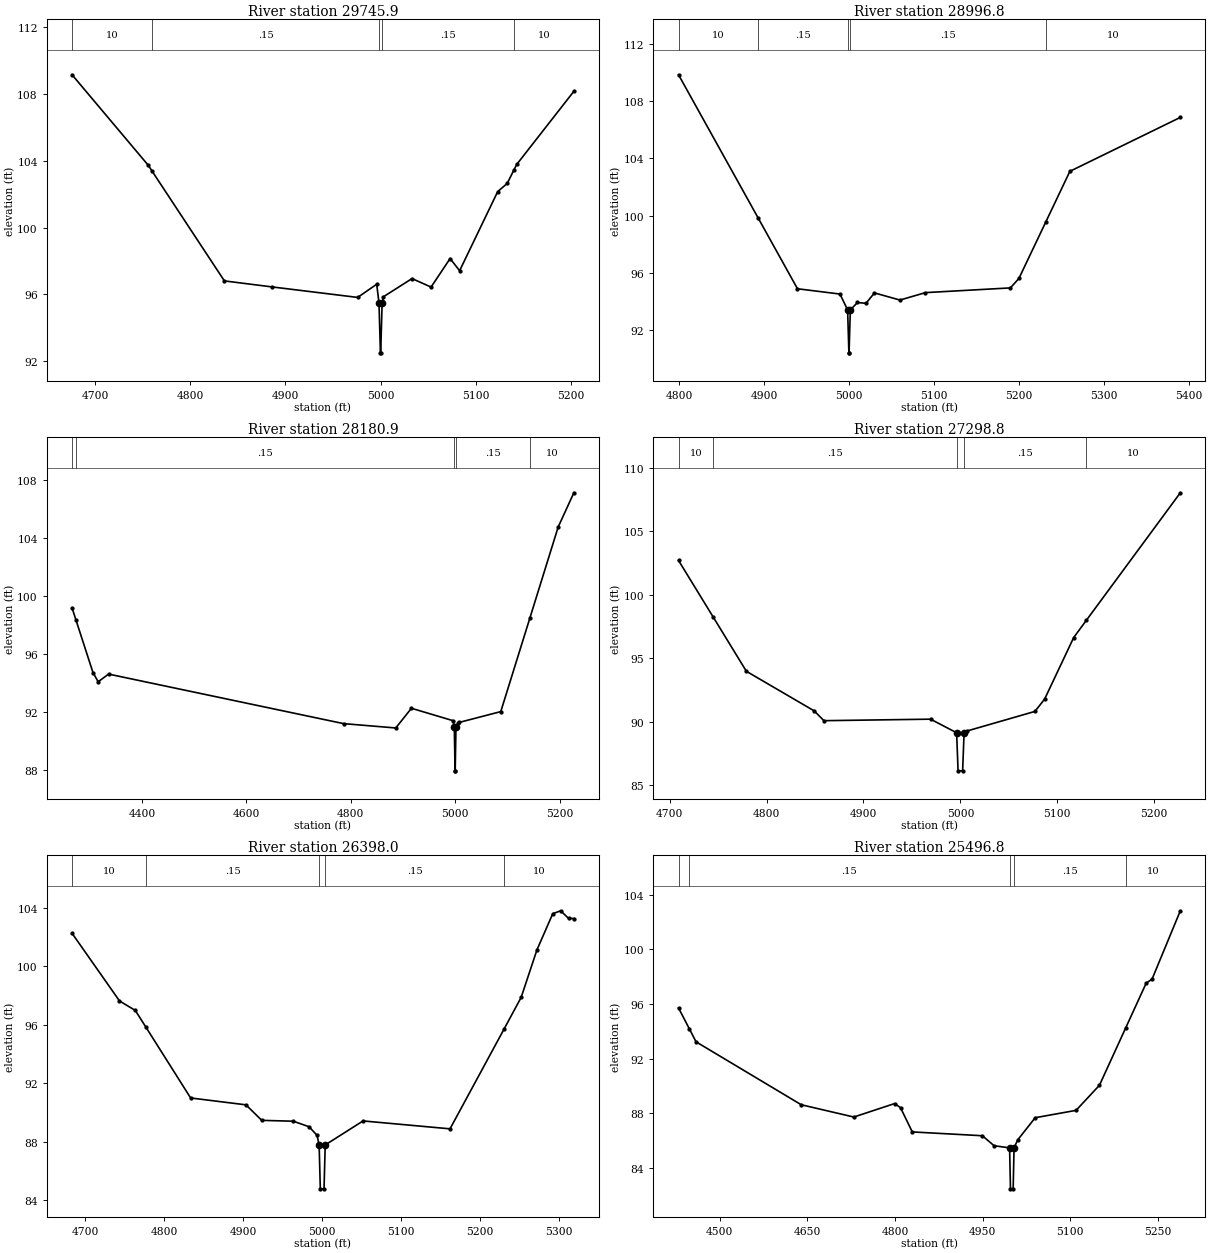
Type RM Length L Ch R = 1 ,29745.9 ,749.1,749.1,749.1
BEGIN DESCRIPTION:
Apple Tree Swamp 22.0
END DESCRIPTION:
XS GIS Cut Line= 3
            0.05       0.0851809       0.0721975       0.0667528
       0.0897879            0.05
#Sta/Elev= 21
    4676  109.16    4756  103.74  4759.9   103.4    4836   96.81    4886   96.45
    4976   95.82    4996   96.61  4998.4    95.5  4999.9    92.5  5000.2    92.5
  5001.7    95.5  5003.1   95.86  5033.1   96.95  5053.1   96.44  5073.1   98.15
  5083.1   97.42  5123.1  102.16  5133.1  102.65  5139.9  103.43  5143.1  103.79
  5203.1  108.17
#Mann= 5 , 1 , 0
    4676      10       0  4759.9     .15       0  4998.4    .045       0
  5001.7     .15       0  5139.9      10       0
Bank Sta=4998.4,5001.7
XS Rating Curve= 0 ,0
Exp/Cntr=0.3,0.1

Type RM Length L Ch R = 1 ,28996.8 ,815.9,815.9,815.9
BEGIN DESCRIPTION:
Apple Tree Swamp 21.0
END DESCRIPTION:
XS GIS Cut Line= 3
       0.1023152       0.1063488       0.1165468       0.0949903
       0.1350106       0.0700205
#Sta/Elev= 18
  4799.4  109.84  4892.9   99.85  4939.4   94.88  4989.4   94.51  4998.4    93.4
  4999.9    90.4  5000.1    90.4  5001.6    93.4    5010   93.92    5020   93.86
    5030   94.59    5060   94.09    5090   94.61    5190   94.94    5200    95.6
  5231.9   99.58    5260  103.09    5390  106.86
#Mann= 5 , 1 , 0
  4799.4      10       0  4892.9     .15       0  4998.4    .045       0
  5001.6     .15       0  5231.9      10       0
Bank Sta=4998.4,5001.6
XS Rating Curve= 0 ,0
Exp/Cntr=0.3,0.1

Type RM Length L Ch R = 1 ,28180.9 ,882.1,882.1,882.1
BEGIN DESCRIPTION:
Apple Tree Swamp 20.0
END DESCRIPTION:
XS GIS Cut Line= 3
       0.1006772       0.1366957       0.1542862       0.1316699
       0.1727142       0.1312511
#Sta/Elev= 19
  4266.3   99.19  4273.9   98.34  4306.3   94.73  4316.3   94.09  4336.3   94.62
  4786.3    91.2  4886.3    90.9  4916.3   92.26  4996.3    91.4  4998.4   90.94
  4999.9   87.94  5000.1   87.94  5001.6   90.94  5006.3   91.25  5007.4   91.28
  5087.4   92.03  5142.9   98.46  5197.4  104.78  5227.4  107.14
#Mann= 5 , 1 , 0
  4266.3      10       0  4273.9     .15       0  4998.4    .045       0
  5001.6     .15       0  5142.9      10       0
Bank Sta=4998.4,5001.6
XS Rating Curve= 0 ,0
Exp/Cntr=0.3,0.1

Type RM Length L Ch R = 1 ,27298.8 ,900.8,900.8,900.8
BEGIN DESCRIPTION:
Apple Tree Swamp 19.0
END DESCRIPTION:
XS GIS Cut Line= 3
       0.1467474       0.1911423       0.1731331       0.1869541
       0.1911423       0.1815095
#Sta/Elev= 16
  4709.2  102.71  4744.9   98.26  4779.2   93.98  4849.2   90.86  4859.2   90.09
  4969.2   90.21  4996.1   89.14  4997.6   86.14  5002.3   86.14  5003.8   89.14
  5006.9   89.28  5076.9   90.82  5086.9   91.79  5116.9   96.64  5129.9   97.99
  5226.9  108.04
#Mann= 5 , 1 , 0
  4709.2      10       0  4744.9     .15       0  4996.1    .045       0
  5003.8     .15       0  5129.9      10       0
Bank Sta=4996.1,5003.8
XS Rating Curve= 0 ,0
Exp/Cntr=0.3,0.1

Type RM Length L Ch R = 1 ,26398.0 ,901.2,901.2,901.2
BEGIN DESCRIPTION:
Apple Tree Swamp 18.0
END DESCRIPTION:
XS GIS Cut Line= 3
       0.1663804       0.2455156        0.189467       0.2443325
       0.2123336       0.2417643
#Sta/Elev= 23
  4683.5  102.25  4743.5   97.63  4763.5   96.98  4776.9   95.84  4833.5      91
  4903.5   90.53  4923.5   89.47  4963.5   89.41  4983.5   89.03  4993.5   88.44
  4996.1   87.79  4997.6   84.79  5002.3   84.79  5003.8   87.79  5051.7   89.43
  5161.7   88.89  5229.9   95.69  5251.7   97.87  5271.7  101.12  5291.7  103.59
  5301.7  103.79  5311.7  103.27  5318.4  103.26
#Mann= 5 , 1 , 0
  4683.5      10       0  4776.9     .15       0  4996.1    .045       0
  5003.8     .15       0  5229.9      10       0
Bank Sta=4996.1,5003.8
XS Rating Curve= 0 ,0
Exp/Cntr=0.3,0.1

Type RM Length L Ch R = 1 ,25496.8 ,731.6,731.6,731.6
BEGIN DESCRIPTION:
Apple Tree Swamp 17.0
END DESCRIPTION:
XS GIS Cut Line= 3
       0.1926394       0.2985024       0.2295971       0.2797509
       0.2446883       0.2652098
#Sta/Elev= 22
  4429.6   95.71  4447.9    94.2  4459.6   93.23  4639.6   88.62  4729.6   87.72
  4799.6   88.71  4809.6    88.4  4829.6   86.63  4949.6   86.35  4969.6   85.62
  4996.2   85.46  4997.7   82.46  5002.3   82.46  5003.8   85.46    5010   86.04
    5040   87.67    5110   88.21    5150   90.05  5194.9   94.25    5230   97.53
    5240   97.82  5288.4  102.83
#Mann= 5 , 1 , 0
  4429.6      10       0  4447.9     .15       0  4996.2    .045       0
  5003.8     .15       0  5194.9      10       0
Bank Sta=4996.2,5003.8
XS Rating Curve= 0 ,0
Exp/Cntr=0.3,0.1

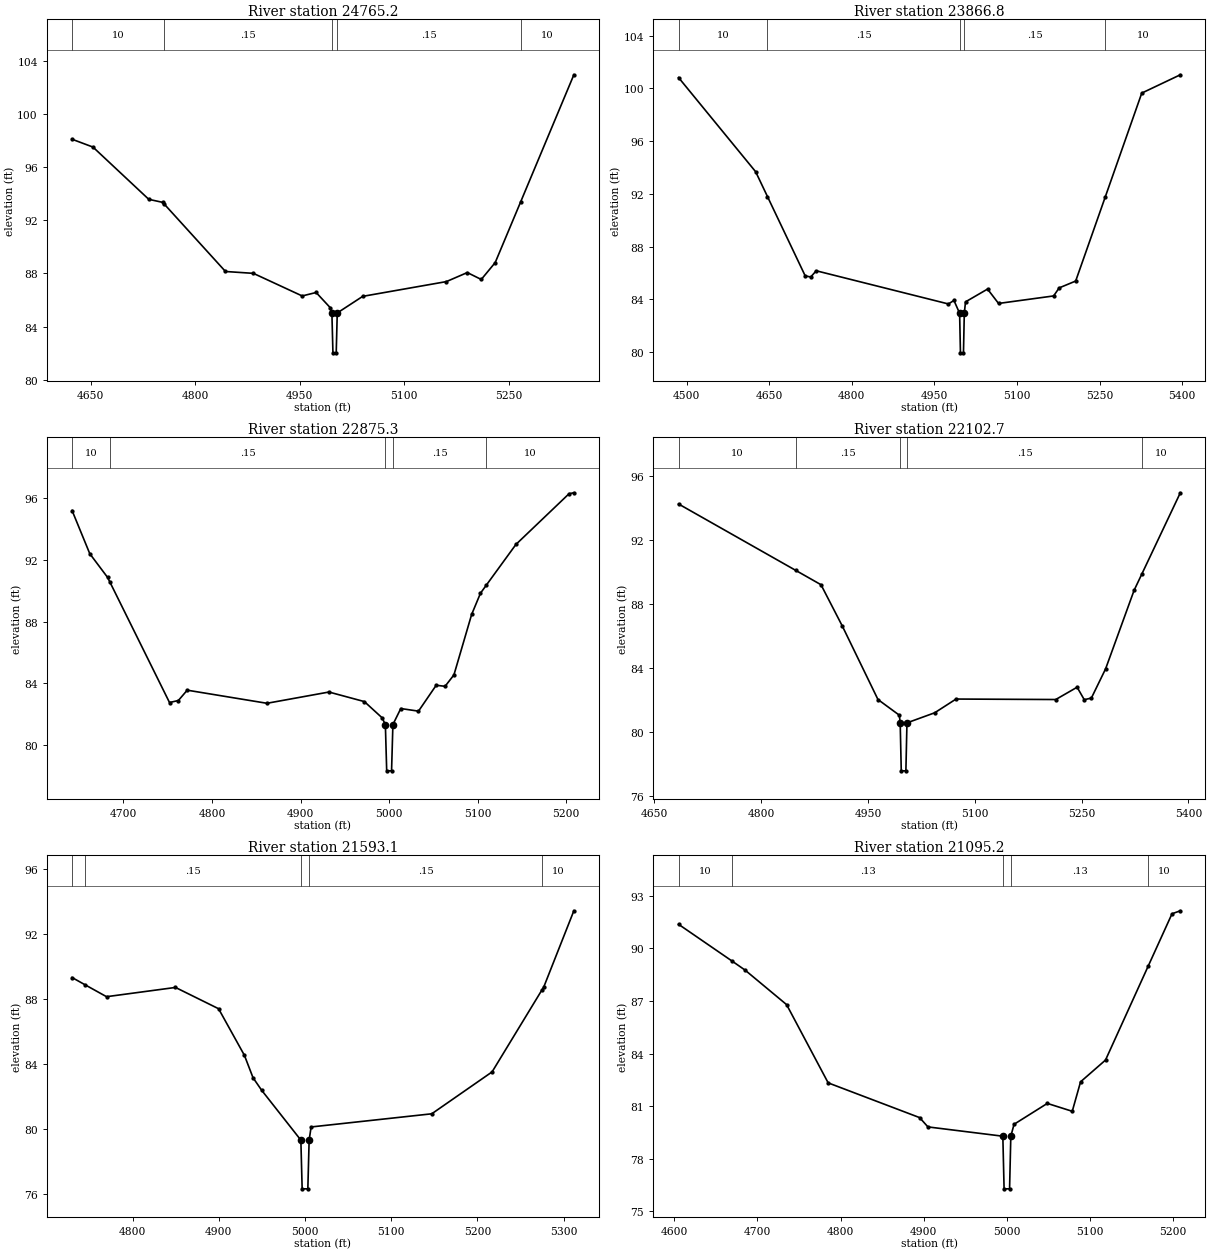
Type RM Length L Ch R = 1 ,24765.2 ,898.4,898.4,898.4
BEGIN DESCRIPTION:
Apple Tree Swamp 16.0
END DESCRIPTION:
XS GIS Cut Line= 3
       0.2334431       0.3310282       0.2573159       0.3176259
       0.2740687       0.2991979
#Sta/Elev= 21
  4623.5    98.1  4653.5   97.51  4733.5   93.58  4753.5   93.35  4755.9   93.21
  4843.5   88.15  4883.5   88.01  4953.5   86.31  4973.5   86.57  4993.5   85.44
  4996.1   85.03  4997.6   82.03  5002.3   82.03  5003.8   85.03  5040.3   86.28
  5160.3   87.39  5190.3   88.07  5210.3   87.55  5230.3   88.82  5266.9    93.4
  5343.1  102.95
#Mann= 5 , 1 , 0
  4623.5      10       0  4755.9     .15       0  4996.1    .045       0
  5003.8     .15       0  5266.9      10       0
Bank Sta=4996.1,5003.8
XS Rating Curve= 0 ,0
Exp/Cntr=0.3,0.1

Type RM Length L Ch R = 1 ,23866.8 ,991.5,991.5,991.5
BEGIN DESCRIPTION:
Apple Tree Swamp 15.0
END DESCRIPTION:
XS GIS Cut Line= 3
       0.2761052        0.367901       0.3089289       0.3505513
       0.3281542       0.3252302
#Sta/Elev= 21
  4485.4  100.83  4625.4   93.68  4646.9   91.79  4715.4   85.77  4725.4   85.69
  4735.4   86.16  4975.4   83.64  4985.4   83.91  4995.7   82.93  4997.2   79.93
  5002.7   79.93  5004.2   82.93  5006.4    83.8  5046.4   84.77  5066.4   83.68
  5166.4   84.25  5176.4   84.86  5206.4   85.38  5259.9   91.74  5326.4   99.65
  5396.4  101.04
#Mann= 5 , 1 , 0
  4485.4      10       0  4646.9     .15       0  4995.7    .045       0
  5004.2     .15       0  5259.9      10       0
Bank Sta=4995.7,5004.2
XS Rating Curve= 0 ,0
Exp/Cntr=0.3,0.1

Type RM Length L Ch R = 1 ,22875.3 ,772.6,772.6,772.6
BEGIN DESCRIPTION:
Apple Tree Swamp 14.0
END DESCRIPTION:
XS GIS Cut Line= 3
       0.3365946       0.4058826       0.3605089       0.3950977
        0.370825       0.3843128
#Sta/Elev= 26
  4642.1    95.2  4662.1    92.4  4682.1   90.87  4684.9   90.55  4752.1   82.75
  4762.1   82.88  4772.1   83.55  4862.1    82.7  4932.1   83.43  4972.1   82.81
  4992.1   81.76  4995.8   81.32  4997.3   78.32  5002.8   78.32  5004.3   81.32
  5013.2   82.36  5033.2   82.19  5053.2   83.87  5063.2    83.8  5073.2   84.54
  5093.2   88.46  5103.2   89.84  5109.9   90.37  5143.2      93  5203.2   96.29
  5208.6   96.35
#Mann= 5 , 1 , 0
  4642.1      10       0  4684.9     .15       0  4995.8    .045       0
  5004.3     .15       0  5109.9      10       0
Bank Sta=4995.8,5004.3
XS Rating Curve= 0 ,0
Exp/Cntr=0.3,0.1

Type RM Length L Ch R = 1 ,22102.7 ,509.6,509.6,509.6
BEGIN DESCRIPTION:
Apple Tree Swamp 13.0
END DESCRIPTION:
XS GIS Cut Line= 3
        0.375983       0.4466777       0.3919259        0.429797
       0.4149024       0.4138541
#Sta/Elev= 20
  4684.1   94.28  4848.9   90.12  4884.1   89.23  4914.1   86.64  4964.1   82.05
  4994.1   81.07  4995.3   80.59  4996.8   77.59  5003.3   77.59  5004.8   80.59
  5043.7   81.22  5073.7   82.08  5213.7   82.05  5243.7   82.82  5253.7   82.04
  5263.7   82.14  5283.7   83.97  5323.7   88.88  5334.9   89.93  5388.6   94.98
#Mann= 5 , 1 , 0
  4684.1      10       0  4848.9     .15       0  4995.3    .045       0
  5004.8     .15       0  5334.9      10       0
Bank Sta=4995.3,5004.8
XS Rating Curve= 0 ,0
Exp/Cntr=0.3,0.1

Type RM Length L Ch R = 1 ,21593.1 ,497.9,497.9,497.9
BEGIN DESCRIPTION:
Apple Tree Swamp 12.0
END DESCRIPTION:
XS GIS Cut Line= 3
       0.4003663       0.4691854       0.4195915       0.4466777
       0.4360034       0.4307348
#Sta/Elev= 18
  4729.7   89.31  4744.9   88.86  4769.7   88.13  4849.7    88.7  4899.7   87.39
  4929.7   84.52  4939.7   83.14  4949.7   82.37  4995.2    79.3  4996.7    76.3
  5003.3    76.3  5004.8    79.3  5007.1   80.11  5147.1   80.92  5217.1    83.5
  5274.9   88.54  5277.1   88.73    5312   93.42
#Mann= 5 , 1 , 0
  4729.7      10       0  4744.9     .15       0  4995.2    .045       0
  5004.8     .15       0  5274.9      10       0
Bank Sta=4995.2,5004.8
XS Rating Curve= 0 ,0
Exp/Cntr=0.3,0.1

Type RM Length L Ch R = 1 ,21095.2 ,726,726,726
BEGIN DESCRIPTION:
Apple Tree Swamp 11.0
END DESCRIPTION:
XS GIS Cut Line= 3
       0.4392857       0.4874729       0.4503919       0.4587683
       0.4561665        0.440113
#Sta/Elev= 19
  4605.1   91.37  4669.9   89.26  4685.1   88.76  4735.1   86.79  4785.1   82.33
  4895.1   80.35  4905.1   79.82  4995.2   79.29  4996.7   76.29  5003.3   76.29
  5004.8   79.29  5008.7   79.97  5048.7   81.16  5078.7   80.71  5088.7   82.39
  5118.7   83.63  5169.9   88.97  5198.7   91.97  5208.7   92.14
#Mann= 5 , 1 , 0
  4605.1      10       0  4669.9     .13       0  4995.2    .042       0
  5004.8     .13       0  5169.9      10       0
Bank Sta=4995.2,5004.8
XS Rating Curve= 0 ,0
Exp/Cntr=0.3,0.1

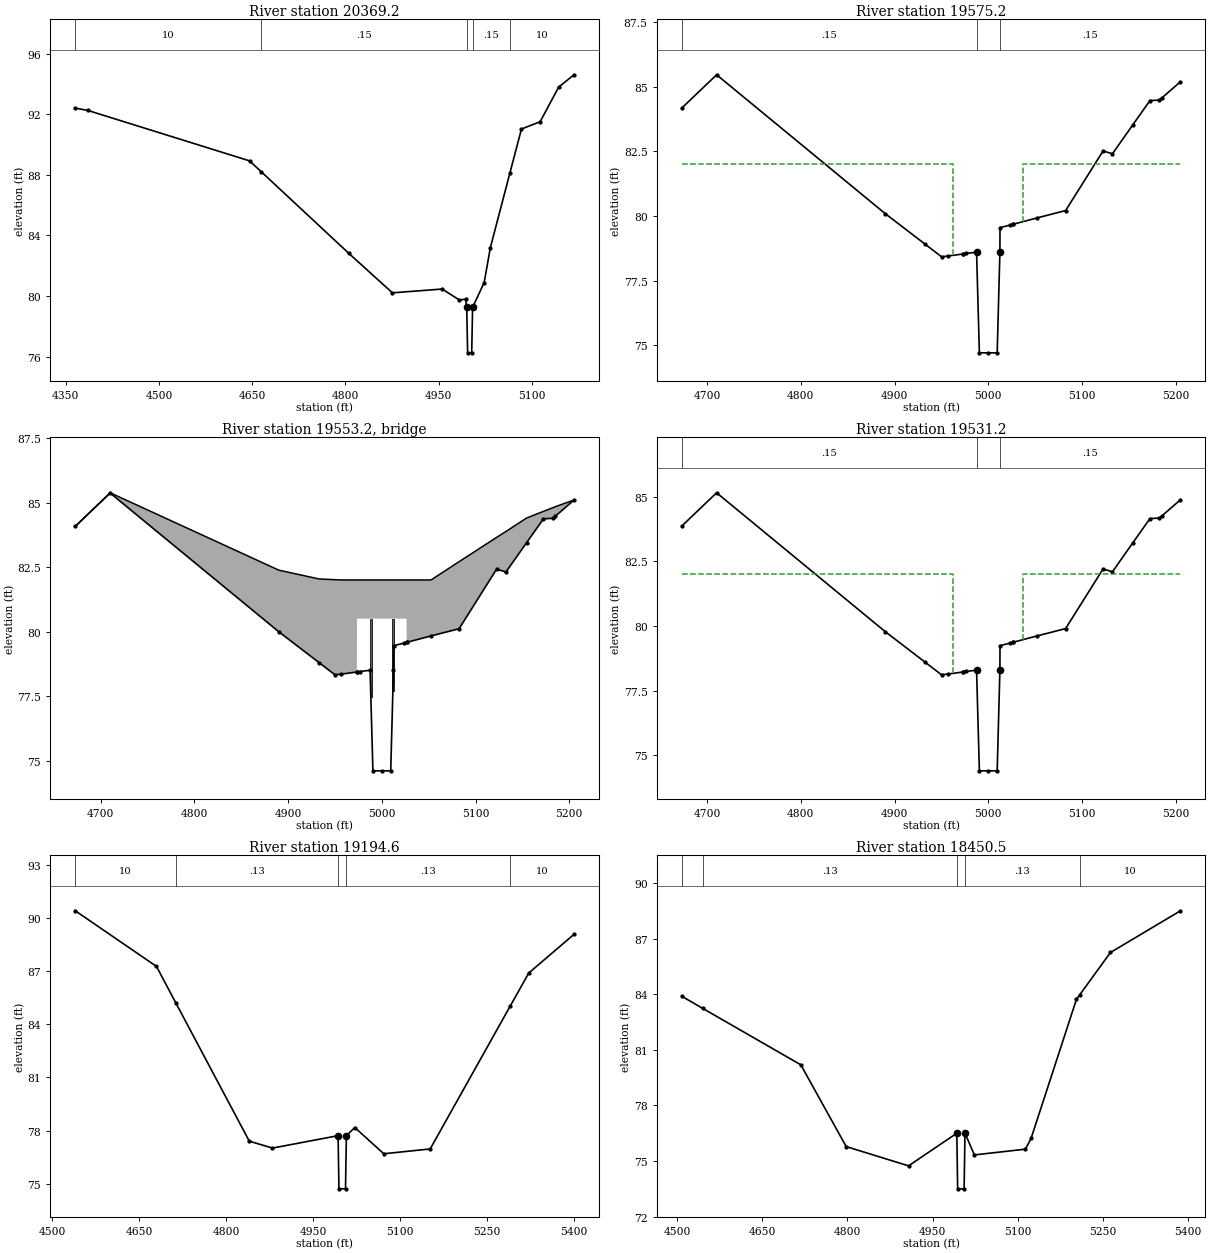
Type RM Length L Ch R = 1 ,20369.2 ,794,794,794
BEGIN DESCRIPTION:
Apple Tree Swamp 10.0
END DESCRIPTION:
XS GIS Cut Line= 4
       0.4538219       0.4954443       0.4725352       0.4873839
       0.4946171        0.476688        0.505402       0.4687165
#Sta/Elev= 20
  4365.3    92.4  4385.3   92.25  4645.7   88.92  4664.9   88.19  4805.7   82.81
  4875.7   80.21  4955.7   80.46  4983.4   79.74  4993.4   79.79  4995.3   79.25
  4996.8   76.25  5003.3   76.25  5004.8   79.25  5023.4   80.89  5033.4    83.2
  5064.9   88.13  5083.4   91.02  5113.4    91.5  5143.4   93.79    5168    94.6
#Mann= 5 , 1 , 0
  4365.3      10       0  4664.9     .15       0  4995.3    .045       0
  5004.8     .15       0  5064.9      10       0
Bank Sta=4995.3,5004.8
XS Rating Curve= 0 ,0
Exp/Cntr=0.5,0.3

Type RM Length L Ch R = 1 ,19575.2 ,44,44,44
BEGIN DESCRIPTION:
Upstream Section of Bridge/Culvert/Weir
END DESCRIPTION:
XS GIS Cut Line= 5
       0.5258423       0.5390529       0.5243964       0.5324779
       0.5308821       0.5077702       0.5338137       0.4949754
        0.532407       0.4851283
#Sta/Elev= 27
  4672.9   84.18  4710.1   85.47  4890.1   80.09  4932.9    78.9  4950.1   78.42
  4956.8   78.45 4973.41   78.53  4973.5   78.53  4976.5   78.55  4987.5    78.6
  4990.5    74.7    5000    74.7  5009.5    74.7  5012.4    78.6  5012.5   79.55
  5023.5   79.65 5026.39   79.68  5026.5   79.68  5052.5   79.93  5082.5   80.21
  5122.5   82.52  5132.5   82.41  5154.4   83.54  5172.5   84.47  5182.5   84.49
  5185.1   84.57  5205.1    85.2
#Mann= 3 , 1 , 0
  4672.9     .15       0  4987.5     .05       0  5012.4     .15       0
#XS Ineff= 2 , 0
       0    4962      82    5037       0      82
Permanent Ineff=
       F       F
Bank Sta=4987.5,5012.4
XS Rating Curve= 0 ,0
Exp/Cntr=0.5,0.3

Type RM Length L Ch R = 3 ,19553.2 ,,,
BEGIN DESCRIPTION:
Pope Farm Rd-TOR
Structure ID: Pope Farm Rd-Bridge
Approximate Survey Structure
END DESCRIPTION:
Bridge Culvert--1,0,-1,-1, 0
Deck Dist Width WeirC Skew NumUp NumDn MinLoCord MaxHiCord MaxSubmerge Is_Ogee
10,24,2.6,0, 27, 27, , , 0.95, 0, 1,1,,
  4672.9  4710.1  4890.1  4932.9  4950.1  4956.8 4973.41  4973.5  4976.5  4987.5
  4990.5    5000  5009.5  5012.4  5012.5  5023.5 5026.39  5026.5  5052.5  5082.5
  5122.5  5132.5  5154.4  5172.5  5182.5  5185.1  5205.1
   84.08   85.38   82.38   82.04   82.01      82      82      82      82      82
      82      82      82      82      82      82      82      82      82   82.71
   83.65   83.88    84.4   84.66    84.8   84.84    85.1
   84.08   85.37   79.99    78.8   78.32   78.35   78.43    80.5    80.5    80.5
    80.5    80.5    80.5    80.5    80.5    80.5    80.5   79.58   79.83   80.11
   82.42   82.31   83.44   84.37   84.39   84.47    85.1
  4672.9  4710.1  4890.1  4932.9  4950.1  4956.8 4973.41  4973.5  4976.5  4987.5
  4990.5    5000  5009.5  5012.4  5012.5  5023.5 5026.39  5026.5  5052.5  5082.5
  5122.5  5132.5  5154.4  5172.5  5182.5  5185.1  5205.1
   84.08   85.38   82.38   82.04   82.01      82      82      82      82      82
      82      82      82      82      82      82      82      82      82   82.71
   83.65   83.88    84.4   84.66    84.8   84.84    85.1
   83.83   85.12   79.74   78.55   78.07    78.1   78.18   80.25   80.25   80.25
   80.25   80.25   80.25   80.25   80.25   80.25   80.25   79.33   79.58   79.86
   82.17   82.06   83.19   84.12   84.14   84.22   84.85
Pier Skew, UpSta & Num, DnSta & Num=  ,4988.3, 2 ,4988.3, 2 , 0 , 0 , 0 ,,
     1.5     1.5
   75.48    81.5
     1.5     1.5
   75.23   81.25
Pier Skew, UpSta & Num, DnSta & Num=  ,5011.8, 2 ,5011.8, 2 , 0 , 0 , 0 ,,
     1.5     1.5
   75.68    81.5
     1.5     1.5
   75.43   81.25
Abutment Skew #Up #Dn= , 2 , 2
  4973.3  4976.5
    80.5   78.45
  4973.3  4976.5
   80.25    78.2
Abutment Skew #Up #Dn= , 2 , 2
  5023.5 5026.59
   79.55    80.5
  5023.5 5026.59
    79.3   80.25
BR Coef= 1 , 1 , 0 ,1.25, 0 ,,,0.8,0,2,0,
WSPro=,,,, 1 ,,,, 0 ,,,, 0 ,,,,-1 ,-1 ,-1 , 0 , 0 , 0 , 0 , 0
BR U #Sta/Elev= 27
  4672.9   84.08  4710.1   85.37  4890.1   79.99  4932.9    78.8  4950.1   78.32
  4956.8   78.35 4973.41   78.43  4973.5   78.43  4976.5   78.45  4987.5    78.5
  4990.5    74.6    5000    74.6  5009.5    74.6  5012.4    78.5  5012.5   79.45
  5023.5   79.55 5026.39   79.58  5026.5   79.58  5052.5   79.83  5082.5   80.11
  5122.5   82.42  5132.5   82.31  5154.4   83.44  5172.5   84.37  5182.5   84.39
  5185.1   84.47  5205.1    85.1
BR U #Mann= 3
  4672.9     .15  4987.5     .05  5012.4     .15
BR U Banks=4987.5,5012.4
BR D #Sta/Elev= 27
  4672.9   83.83  4710.1   85.12  4890.1   79.74  4932.9   78.55  4950.1   78.07
  4956.8    78.1 4973.41   78.18  4973.5   78.18  4976.5    78.2  4987.5   78.25
  4990.5   74.35    5000   74.35  5009.5   74.35  5012.4   78.25  5012.5    79.2
  5023.5    79.3 5026.39   79.33  5026.5   79.33  5052.5   79.58  5082.5   79.86
  5122.5   82.17  5132.5   82.06  5154.4   83.19  5172.5   84.12  5182.5   84.14
  5185.1   84.22  5205.1   84.85
BR D #Mann= 3
  4672.9     .15  4987.5     .05  5012.4     .15
BR D Banks=4987.5,5012.4
BC Design=,, 0 ,, 0 ,,,,,,
BC HTab HWMax=85.47
BC Use User HTab Curves=0
BC User HTab FreeFlow(D)= 0

Type RM Length L Ch R = 1 ,19531.2 ,336.6,336.6,336.6
BEGIN DESCRIPTION:
Downstream Section of Bridge/Culvert/Weir
END DESCRIPTION:
XS GIS Cut Line= 5
       0.5290392       0.5390529       0.5275932       0.5324779
        0.534079       0.5077702       0.5370106       0.4949754
       0.5356039       0.4851283
#Sta/Elev= 27
  4672.9   83.87  4710.1   85.16  4890.1   79.78  4932.9   78.59  4950.1   78.11
  4956.8   78.14 4973.41   78.22  4973.5   78.22  4976.5   78.24  4987.5   78.29
  4990.5   74.39    5000   74.39  5009.5   74.39  5012.4   78.29  5012.5   79.24
  5023.5   79.34 5026.39   79.37  5026.5   79.37  5052.5   79.62  5082.5    79.9
  5122.5   82.21  5132.5    82.1  5154.4   83.23  5172.5   84.16  5182.5   84.18
  5185.1   84.26  5205.1   84.89
#Mann= 3 , 1 , 0
  4672.9     .15       0  4987.5     .05       0  5012.4     .15       0
#XS Ineff= 2 , 0
       0    4962      82    5037       0      82
Permanent Ineff=
       F       F
Bank Sta=4987.5,5012.4
XS Rating Curve= 0 ,0
Exp/Cntr=0.5,0.3

Type RM Length L Ch R = 1 ,19194.6 ,744.1,744.1,744.1
BEGIN DESCRIPTION:
Apple Tree Swamp 9.0
END DESCRIPTION:
XS GIS Cut Line= 3
       0.5485416       0.5371773       0.5574509       0.5048225
       0.5588662       0.4759399
#Sta/Elev= 15
  4539.7    90.4  4679.7   87.26  4712.9   85.21  4839.7    77.4  4879.7   77.01
  4992.8   77.71  4994.3   74.71  5005.6   74.71  5007.1   77.71  5021.6   78.17
  5071.6   76.69  5151.6   76.96  5289.9   85.04  5321.6   86.89  5399.6   89.07
#Mann= 5 , 1 , 0
  4539.7      10       0  4712.9     .13       0  4992.8    .042       0
  5007.1     .13       0  5289.9      10       0
Bank Sta=4992.8,5007.1
XS Rating Curve= 0 ,0
Exp/Cntr=0.3,0.1

Type RM Length L Ch R = 1 ,18450.5 ,839.6,839.6,839.6
BEGIN DESCRIPTION:
Apple Tree Swamp 8.0
END DESCRIPTION:
XS GIS Cut Line= 3
       0.6019973       0.5432731       0.6049364       0.5073514
        0.603873       0.4795014
#Sta/Elev= 16
  4507.7   83.89  4544.9   83.23  4717.7   80.19  4797.7   75.78  4907.7   74.74
  4992.8    76.5  4994.3    73.5  5005.7    73.5  5007.2    76.5  5023.8   75.33
  5113.8   75.64  5123.8   76.22  5203.8   83.72  5209.9   83.98  5263.8   86.25
  5387.3    88.5
#Mann= 5 , 1 , 0
  4507.7      10       0  4544.9     .13       0  4992.8    .042       0
  5007.2     .13       0  5209.9      10       0
Bank Sta=4992.8,5007.2
XS Rating Curve= 0 ,0
Exp/Cntr=0.3,0.1

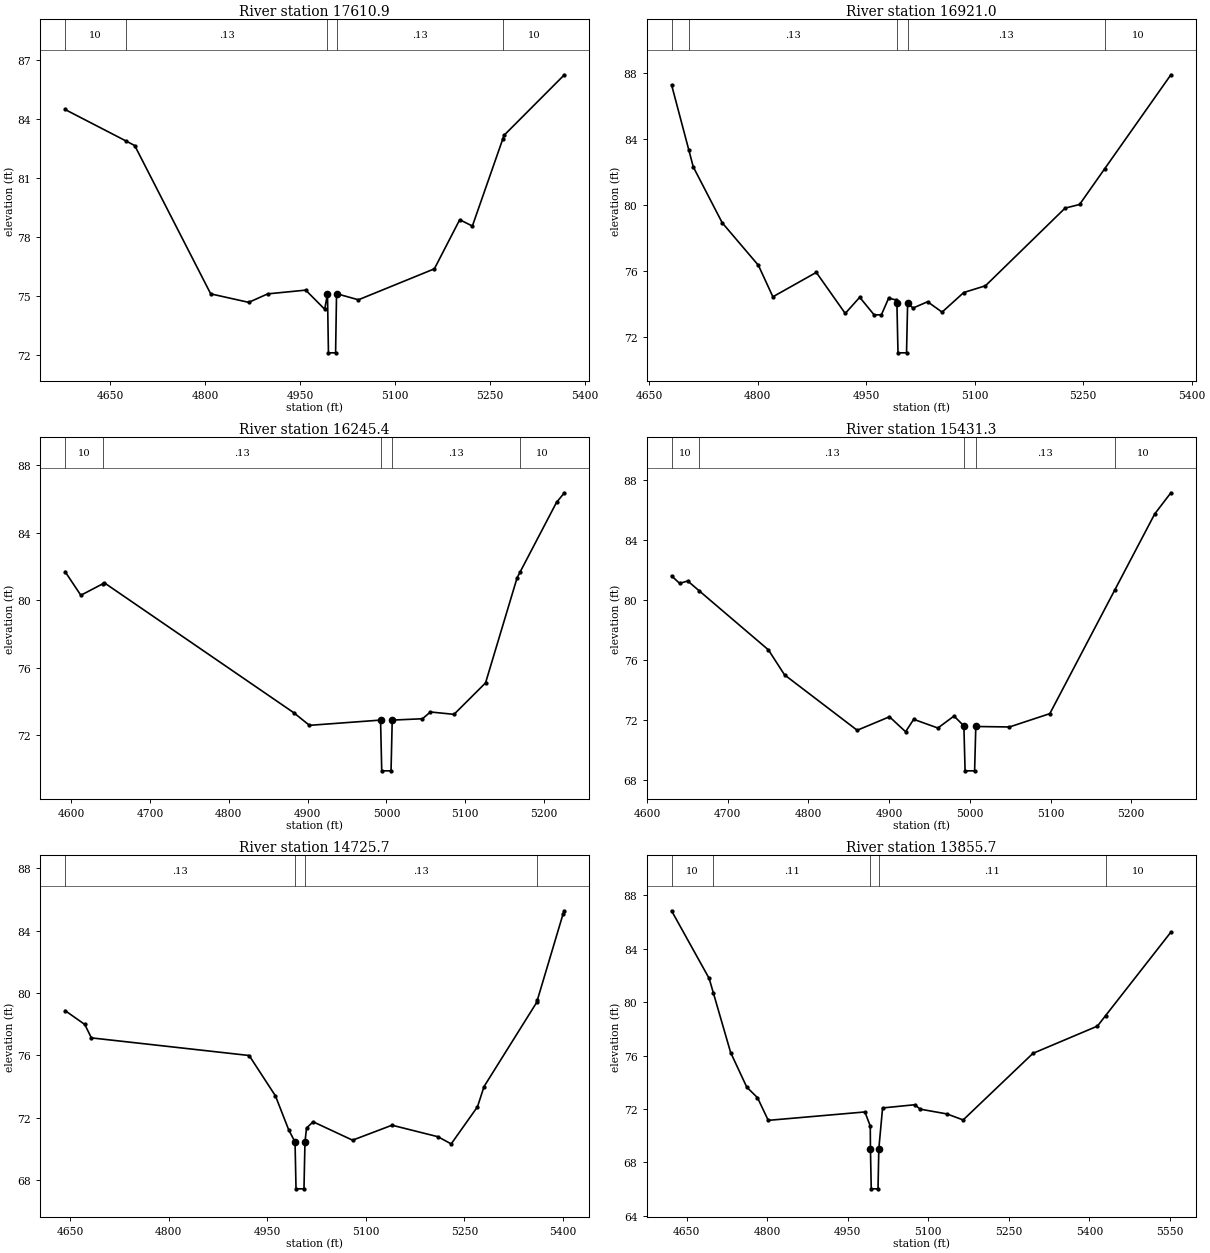
Type RM Length L Ch R = 1 ,17610.9 ,689.9,689.9,689.9
BEGIN DESCRIPTION:
Apple Tree Swamp 7.0
END DESCRIPTION:
XS GIS Cut Line= 3
       0.6673406       0.5014879       0.6479505       0.4776258
       0.6267151          0.4617
#Sta/Elev= 19
  4578.5   84.47  4674.9   82.87  4688.5   82.64  4808.5   75.12  4868.5   74.69
  4898.5   75.12  4958.5   75.31  4988.5   74.34  4992.9   75.13  4994.4   72.13
  5005.7   72.13  5007.2   75.13  5041.7   74.82  5161.7   76.39  5201.7   78.88
  5221.7   78.56  5269.9   82.99  5271.7   83.16    5367   86.23
#Mann= 5 , 1 , 0
  4578.5      10       0  4674.9     .13       0  4992.9    .042       0
  5007.2     .13       0  5269.9      10       0
Bank Sta=4992.9,5007.2
XS Rating Curve= 0 ,0
Exp/Cntr=0.3,0.1

Type RM Length L Ch R = 1 ,16921.0 ,675.6,675.6,675.6
BEGIN DESCRIPTION:
Apple Tree Swamp 6.0
END DESCRIPTION:
XS GIS Cut Line= 3
       0.7000085       0.4759399        0.684931        0.452486
       0.6723664        0.429032
#Sta/Elev= 26
  4681.2   87.27  4704.9   83.34  4711.2   82.29  4751.2    78.9  4801.2   76.32
  4821.2   74.41  4881.2   75.89  4921.2    73.4  4941.2   74.38  4961.2   73.31
  4971.2   73.32  4981.2   74.33  4991.2   74.22  4992.6   74.01  4994.1   71.01
  5005.9   71.01  5007.4   74.01    5015   73.73    5035   74.11    5055   73.48
    5085   74.67    5115   75.08    5225   79.79    5245   80.01  5279.9   82.19
  5371.2   87.88
#Mann= 5 , 1 , 0
  4681.2      10       0  4704.9     .13       0  4992.6    .042       0
  5007.4     .13       0  5279.9      10       0
Bank Sta=4992.6,5007.4
XS Rating Curve= 0 ,0
Exp/Cntr=0.3,0.1

Type RM Length L Ch R = 1 ,16245.4 ,814.1,814.1,814.1
BEGIN DESCRIPTION:
Apple Tree Swamp 5.0
END DESCRIPTION:
XS GIS Cut Line= 3
       0.7427282       0.4562553       0.7247189       0.4252627
       0.7142484       0.4022276
#Sta/Elev= 18
  4592.4   81.69  4612.4   80.29  4639.9   80.96  4642.4   81.02  4882.4   73.35
  4902.4    72.6  4992.6   72.91  4994.1   69.91  5005.9   69.91  5007.4   72.91
  5045.8   72.99  5055.8   73.39  5085.8   73.25  5125.8   75.11  5165.8   81.32
  5169.9   81.69  5215.8   85.78  5225.8   86.35
#Mann= 5 , 1 , 0
  4592.4      10       0  4639.9     .13       0  4992.6    .042       0
  5007.4     .13       0  5169.9      10       0
Bank Sta=4992.6,5007.4
XS Rating Curve= 0 ,0
Exp/Cntr=0.3,0.1

Type RM Length L Ch R = 1 ,15431.3 ,705.6,705.6,705.6
BEGIN DESCRIPTION:
Apple Tree Swamp 4.0
END DESCRIPTION:
XS GIS Cut Line= 3
        0.775815       0.4252627       0.7712079        0.398877
       0.7670197       0.3775172
#Sta/Elev= 22
  4630.4   81.61  4640.4   81.11  4650.4   81.27  4664.9    80.6  4750.4   76.67
  4770.4      75  4860.4    71.3  4900.4    72.2  4920.4    71.2  4930.4   72.03
  4960.4   71.45  4980.4   72.25  4992.6   71.59  4994.1   68.59  5005.9   68.59
  5007.4   71.59  5009.1   71.55  5049.1   71.52  5099.1   72.41  5179.9    80.7
  5229.1   85.75  5249.1   87.16
#Mann= 5 , 1 , 0
  4630.4      10       0  4664.9     .13       0  4992.6    .042       0
  5007.4     .13       0  5179.9      10       0
Bank Sta=4992.6,5007.4
XS Rating Curve= 0 ,0
Exp/Cntr=0.3,0.1

Type RM Length L Ch R = 1 ,14725.7 ,870,870,870
BEGIN DESCRIPTION:
Apple Tree Swamp 3.0
END DESCRIPTION:
XS GIS Cut Line= 3
       0.8386379       0.3917571         0.80597       0.3666279
       0.7795843       0.3540633
#Sta/Elev= 22
  4642.6   78.87  4672.6   77.98  4682.6   77.12  4922.6   75.99  4962.6    73.4
  4982.6   71.24  4992.4   70.44  4993.9   67.44    5006   67.44  5007.5   70.44
  5009.9   71.34  5019.9   71.74  5079.9   70.56  5139.9   71.52  5209.9   70.78
  5229.9   70.32  5269.9    72.7  5279.9      74  5359.9   79.39  5360.9   79.53
  5399.9   85.04  5402.1   85.27
#Mann= 4 , 1 , 0
  4642.6     .13       0  4992.4    .042       0  5007.5     .13       0
  5360.9      10       0
Bank Sta=4992.4,5007.5
XS Rating Curve= 0 ,0
Exp/Cntr=0.3,0.1

Type RM Length L Ch R = 1 ,13855.7 ,665.9,665.9,665.9
BEGIN DESCRIPTION:
Apple Tree Swamp 2.0
END DESCRIPTION:
XS GIS Cut Line= 3
       0.8721435         0.32684       0.8445014       0.3172071
       0.8068076       0.3046425
#Sta/Elev= 22
  4621.9   86.85  4691.9   81.78  4699.9   80.67  4731.9   76.23  4761.9   73.64
  4781.9   72.85  4801.9   71.15  4981.9   71.78  4991.9   70.72  4992.2   69.02
  4993.7   66.02  5006.3   66.02  5007.8   69.02  5014.8   72.08  5074.8   72.32
  5084.8   71.99  5134.8   71.63  5164.8   71.18  5294.8   76.17  5414.8   78.21
  5429.9   78.99  5551.6   85.25
#Mann= 5 , 1 , 0
  4621.9      10       0  4699.9     .11       0  4992.2    .041       0
  5007.8     .11       0  5429.9      10       0
Bank Sta=4992.2,5007.8
XS Rating Curve= 0 ,0
Exp/Cntr=0.3,0.1

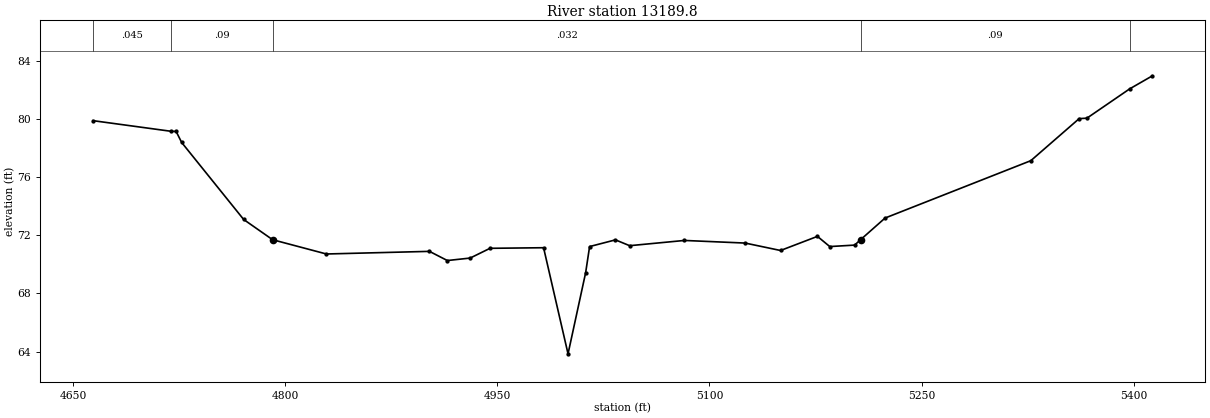
Type RM Length L Ch R = 1 ,13189.8 ,0,0,0
BEGIN DESCRIPTION:
Apple Tree Swamp 1.0
Copied from DTL XS 13125
END DESCRIPTION:
XS GIS Cut Line= 3
       0.8969414       0.2750569       0.8537155       0.2698805
         0.81582       0.2684921
#Sta/Elev= 30
  4664.1  79.869  4719.2   79.14 4722.83   79.13 4726.76   78.37  4770.6   73.08
 4791.08   71.69  4829.1   70.71 4901.99   70.89 4914.64   70.26 4930.78   70.43
 4944.83    71.1  4982.7   71.14    5000   63.85 5012.46   69.43 5015.25   71.22
 5033.53   71.68 5043.56   71.28 5082.33   71.64 5125.29   71.46 5150.29   70.95
 5176.38   71.92  5185.1   71.22 5202.67   71.32 5206.87   71.69 5224.22   73.18
 5327.28   77.12 5361.48   80.01 5366.95   80.04 5397.14   82.05  5413.3  82.953
#Mann= 5 ,-1 , 0
  4664.1    .045       0  4719.2     .09       0 4791.08    .032       0
 5206.87     .09       0 5397.14    .085       0
Bank Sta=4791.08,5206.87
XS Rating Curve= 0 ,0
Exp/Cntr=0.3,0.1

Chan Stop Cuts=-1
Use User Specified Reach Order=0
User Specified Reach Order=Apple Tree Swamp,Reach - 1