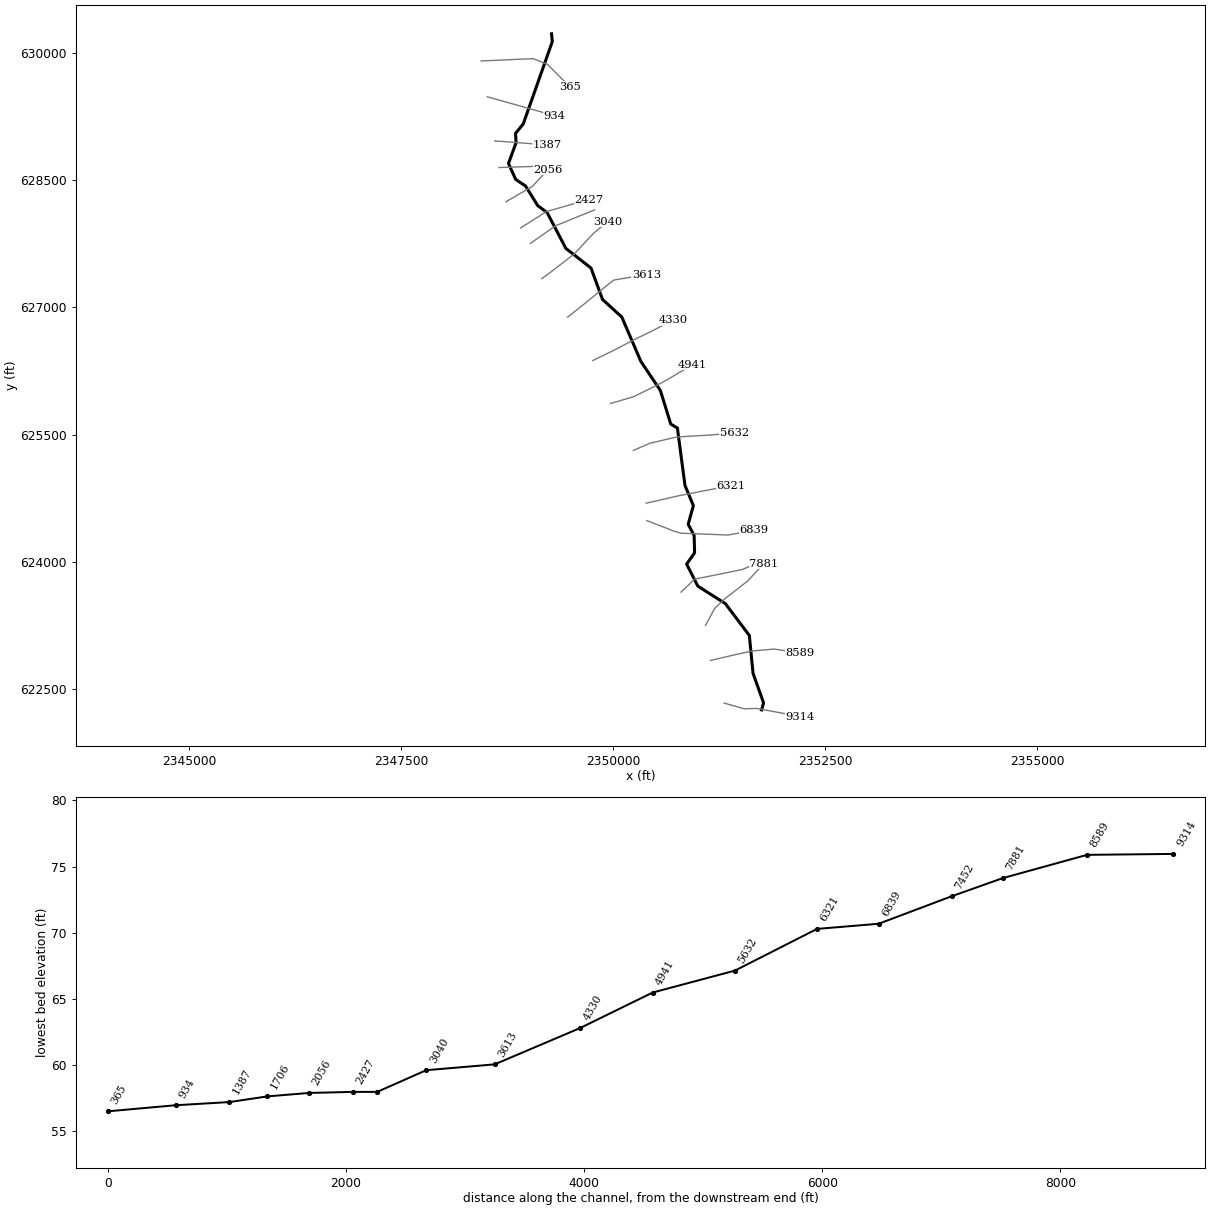
--- LDS_Button_Bch.prj (project) ---

Proj Title=LDS_Button_Bch
Current Plan=p02
Default Exp/Contr=0.3,0.1
English Units
Geom File=g01
Flow File=f01
Flow File=f02
Plan File=p01
Plan File=p02
Y Axis Title=Elevation
X Axis Title(PF)=Main Channel Distance
X Axis Title(XS)=Station
BEGIN DESCRIPTION:
END DESCRIPTION:
DSS Export Rating Curves= 0
DSS Export Rating Curve Sorted= 0
DSS Export Volume Flow Curves= 0
DXF OffsetX= 0
DXF OffsetY= 0
DXF ScaleX= 1
DXF ScaleY= 10

--- LDS_Button_Bch.p02 (plan) ---

Plan Title=LDS_Button_Bch_Multi
Program Version=4.00
Short Identifier=Multi
Geom File=g01
Flow File=f02
Subcritical Flow
K Sum by GR= 0
Std Step Tol= 0.01
Critical Tol= 0.01
Num of Std Step Trials= 20
Max Error Tol= 0.3
Flow Tol Ratio= 0.001
Split Flow NTrial= 30
Split Flow Tol= 0.02
Split Flow Ratio= 0.02
Log Output Level= 0
Friction Slope Method= 1
Unsteady Friction Slope Method= 2
Unsteady Bridges Friction Slope Method= 1
Parabolic Critical Depth
Global Vel Dist= 0 , 0 , 0
Global Log Level= 0
CheckData=True
Encroach Param=-1 ,0,0, 0
Computation Interval=1HOUR
Output Interval=1HOUR
Run HTab= 0
Run UNet= 0
Run PostProcess= 0
Run WQNet= 0
UNET Theta= 1
UNET Theta Warmup= 1
UNET ZTol= 0.02
UNET ZSATol= 0.05
UNET MxIter= 20
UNET MaxInSteps= 0
UNET DtIC= 0
UNET DtMin= 0
UNET MaxCRTS= 20
UNET WFStab= 2
UNET SFStab= 1
UNET WFX= 1
UNET SFX= 1
UNET DSS MLevel= 4
UNET DZMax Abort= 100
UNET Convert EG Bridges= 0
UNET Use Existing IB Tables=-1
UNET Froude Reduction=False
UNET Froude Limit= 1
UNET Froude Power= 10
UNET Time Slicing=0,0, 5
Instantaneous Interval=1HOUR
Write IC File= 0
Echo Input=False
Echo Output=False
Write Detailed= 0
Detailed Automatic Start=False, 10
WQ ULTIMATE=-1
WQ Max Comp Step=1HOUR
WQ Output Interval=15MIN
WQ Output Selected Increments= 0
WQ Output face flow=0
WQ Output face velocity=0
WQ Output face area=0
WQ Output face dispersion=0
WQ Output cell volume=0
WQ Output cell surface area=0
WQ Output cell continuity=0
WQ Output face conc=0
WQ Output face dconc_dx=0
WQ Output face courant=0
WQ Output face peclet=0
WQ Output face adv mass=0
WQ Output face disp mass=0
WQ Output cell mass=0
WQ Output cell source sink temp=0
WQ Output cell source sink nsm=0
WQ Output MaxMinRange=-1
WQ Daily Max Min Mean=-1
WQ Daily Range=0
WQ Daily Time=0
WQ Create Restart=0
WQ Fixed Restart=0
WQ System Summary=False
Sorting and Armoring Iterations= 10
XS Update Threshold= 0.02
Hydraulics Update Threshold= 0.02
Energy Slope Method= 1
Volume Change Method= 0
XS Weighting Method= 0
Number of US Weighted Cross Sections= 1
Number of DS Weighted Cross Sections= 1
Upstream XS Weight=0.25
Main XS Weight=0.5
Downstream XS Weight=0.25
Number of DS XS's Weighted with US Boundary= 1
Upstream Boundary Weight= 1
Weight of XSs Associated with US Boundary= 0
Number of US XS's Weighted with DS Boundary= 1
Downstream Boundary Weight= 0.5
Weight of XSs Associated with DS Boundary= 0.5
Sediment Output Level= 4
Mass or Volume Output= 0
Output Increment Type= 1
Profile and TS Output Increment= 10
XS Output Flag= 0
XS Output Increment= 10
Disregard all LS=0
Disregard all Conn=0
Disregard all Breaches=0
Disregard all Pumps=0

--- LDS_Button_Bch.p01 (plan) ---

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Plan Title=LDS_Button_Bch
Short Identifier=FW
Geom File=g01
Flow File=f01
Encroach Param=-1 ,10,10, 2
Encroach River=Button Brch DS
Encroach Reach=Main
Encroach Node=9314
       1     405     520
Encroach Node=8589
       1     400     615
Encroach Node=7881
       1     320     465
Encroach Node=7452
       1     190     350
Encroach Node=6839
       1     480     650
Encroach Node=6321
       1     415     585
Encroach Node=5632
       1     470     640
Encroach Node=4941
       1     460     630
Encroach Node=4330
       1     390     555
Encroach Node=3613
       1     435     605
Encroach Node=3040
       1     365     530
Encroach Node=2628
       1     311     381
Encroach Node=2427
       1     335     385
Encroach Node=2056
       1     255     325
Encroach Node=1706
       1      90     250
Encroach Node=1387
       1     130     350
Encroach Node=934
       1     230     525
Encroach Node=365
       1     300     800

--- LDS_Button_Bch.f02 (steady flow) ---

Flow Title=LDS_Button_Bch_Multi
Program Version=4.00
Number of Profiles= 8
Profile Names=10-yr,25-yr,50-yr,100-yr,500-yr,100-yr-10%,100-yr-20%,100-yr-35%
River Rch & RM=Button Brch DS,Main            ,9314
     359     524     675     849    1363    1472    1886    2305
River Rch & RM=Button Brch DS,Main            ,6839
     480     694     888    1110    1759    1907    2444    2986
River Rch & RM=Button Brch DS,Main            ,3040
     531     765     976    1217    1921    2085    2673    3266
Boundary for River Rch & Prof#=Button Brch DS,Main            , 1
Up Type= 0
Dn Type= 3
Dn Slope=0.00081
DSS Import GetInterval= 0
DSS Import GetPeak= 0
DSS Import FillOption= 0

--- LDS_Button_Bch.f01 (steady flow) ---

Flow Title=LDS_Button_Bch
Program Version=4.00
Number of Profiles= 2
Profile Names=100-Year,100-Year FW
River Rch & RM=Button Brch DS,Main            ,9314
     849     849
River Rch & RM=Button Brch DS,Main            ,6839
    1110    1110
River Rch & RM=Button Brch DS,Main            ,3040
    1217    1217
Boundary for River Rch & Prof#=Button Brch DS,Main            , 1
Up Type= 0
Dn Type= 3
Dn Slope=0.00081
DSS Import GetInterval= 0
DSS Import GetPeak= 0
DSS Import FillOption= 0

--- LDS_Button_Bch.g01 (geometry) ---

Geom Title=LDS_Button_Bch
Program Version=4.00

River Reach=Button Brch DS  ,Main
Reach XY= 30
2351750.64380549 622251.112542482351774.84530953622332.936675161
2351650.38043162622682.1298047752351606.58723386 623129.28140305
2351324.23635347623504.8008711192350998.30836014623711.882192835
2350866.85673861623971.1840217262350960.49351014624104.436350495
2350955.09138875624309.7169650352350884.86381003624441.168586642
2350946.08785298624660.8548583842350847.04895999624900.348908693
  2350757.662193625576.9280528432350679.34941523 625623.64093782
2350557.07156935626019.3265515572350327.62886974626361.429738477
2350100.93398678626887.6366484312349874.23910397627093.722905576
2349738.22217427627464.6781684762349441.45796388627696.868684888
2349219.91452843628120.717940032 2349110.0040341628200.795585945
2348965.94277903628432.7852365232348849.35914752628510.900195003
2348764.17851444 628698.925647812348853.67705983 628943.08396025
2348848.18153508629054.1720670462348938.80862576629165.603644133
2349281.78824879630137.6245785212349272.42000009 630228.88000001

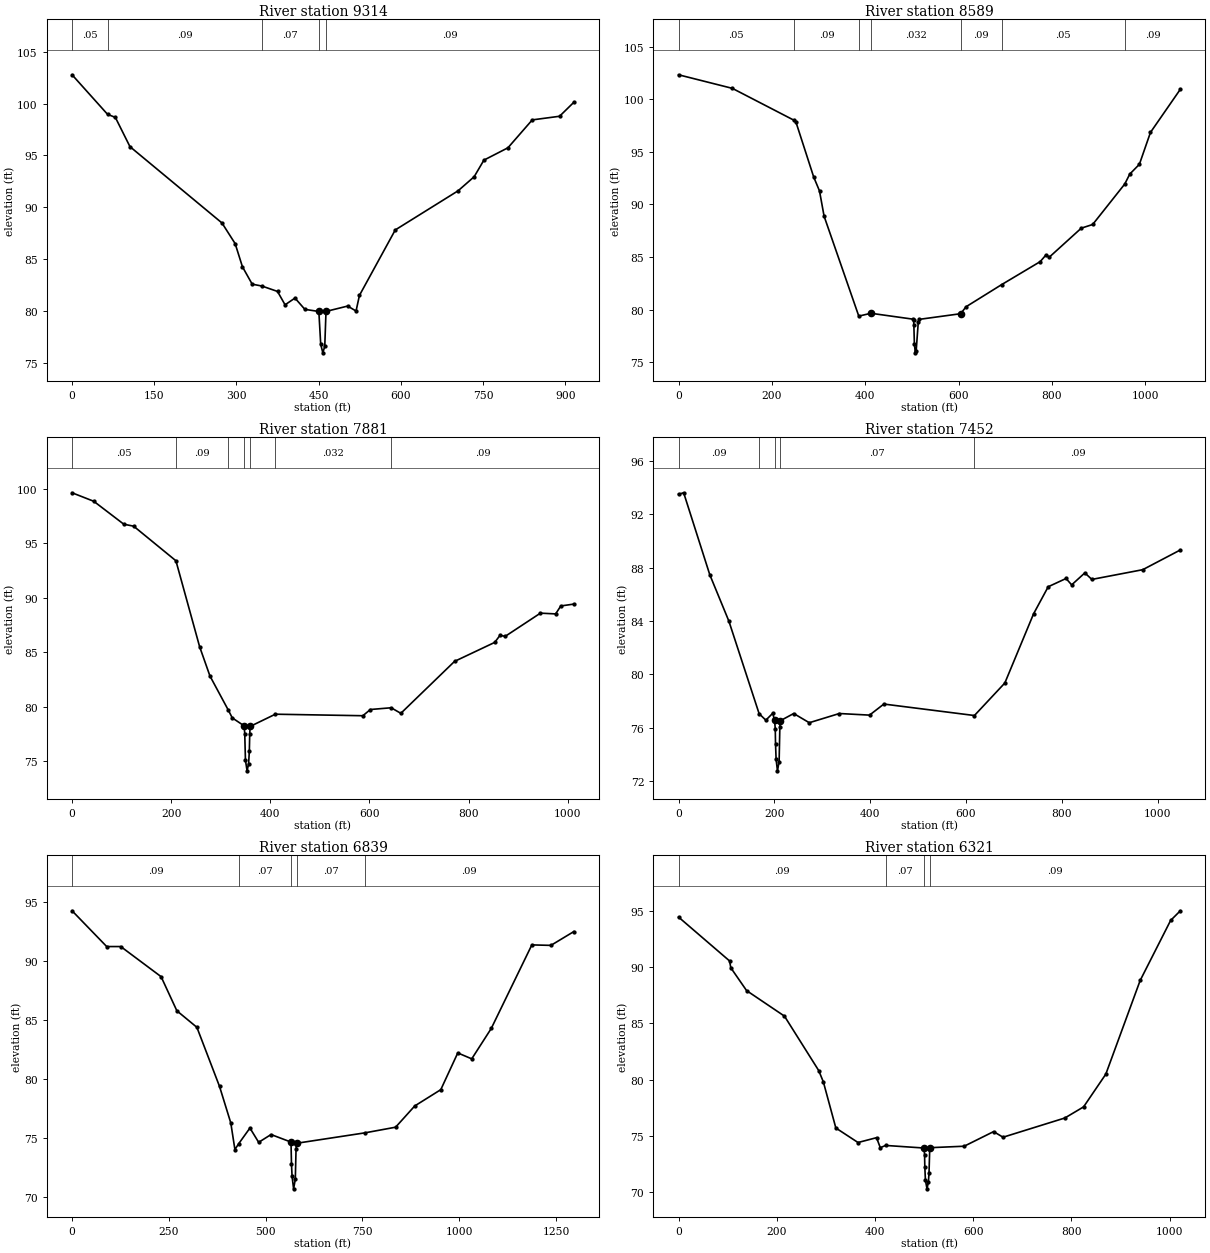
Type RM Length L Ch R = 1 ,9314    ,671.65,725.47,709.32
XS GIS Cut Line= 5
2351308.42572875622331.6889654252351545.25000001      622264.125
2351692.25000001     622268.18752351960.49999999622219.250000015
2352205.54188812622170.723147362
#Sta/Elev= 30
       0  102.77   64.71   98.96      79   98.66  105.66   95.84  273.62   88.48
  297.64   86.49  310.92   84.26  328.75   82.58   346.5    82.4  374.95   81.88
  388.73   80.59  406.83   81.24  424.91   80.15  450.39   79.95  453.78   76.79
  457.67   75.96  461.19   76.59  463.38   79.85  463.95   79.96  503.01   80.47
  518.29   79.99  524.49    81.5  589.87   87.81  704.44   91.58  733.86   92.94
  751.62   94.54   795.5   95.73  839.88   98.42  889.71   98.77  915.81  100.12
#Mann= 5 ,-1 , 0
       0     .05       0   64.71     .09       0   346.5     .07       0
  450.39     .05       0  463.95     .09       0
Bank Sta=450.39,463.95
XS Rating Curve= 0 ,0
Exp/Cntr=0.3,0.1

Type RM Length L Ch R = 1 ,8589    ,666.68,708,775.85
XS GIS Cut Line= 5
2351147.45991068622833.902317807       2351425.5 622899.06250003
2351640.50000004     622946.43752351900.25000001         622969.
2352205.54188812622921.896965012
#Sta/Elev= 30
       0  102.32  115.26  101.03  247.79   97.99  251.28   97.87  289.67    92.6
   302.1   91.28  311.92   88.88  386.29   79.38  412.28   79.65  502.53   79.09
  503.71   78.98  504.29   78.53  505.45   76.72  507.48   75.89  509.23   76.05
  513.86   78.86  515.44   79.07  604.65   79.61  616.15   80.27  692.64   82.38
  775.09   84.56  787.55    85.2  794.45   84.98   863.1   87.74  887.51   88.09
  956.34   91.94     967   92.88  987.62   93.81 1011.35   96.84 1075.36  100.94
#Mann= 7 ,-1 , 0
       0     .05       0  247.79     .09       0  386.29     .07       0
  412.28    .032       0  604.65     .09       0  692.64     .05       0
  956.34     .09       0
Bank Sta=412.28,604.65
XS Rating Curve= 0 ,0
Exp/Cntr=0.3,0.1

Type RM Length L Ch R = 1 ,7881    ,426.6,428.89,271.41
XS GIS Cut Line= 5
2351089.51221617623248.1210229692351200.24999999         623452.
2351331.00000003623573.0625000152351584.00000004623769.000000015
2351776.29970659623975.686520636
#Sta/Elev= 30
       0   99.61   43.81   98.83  104.37   96.73  124.21   96.55  209.55   93.38
  257.34   85.51  278.21   82.82   315.3   79.69  323.31   78.98  347.29   78.25
  348.45   77.52  349.83    75.1  353.15   74.13  356.21   74.77  357.69   75.94
  358.51   77.55  359.34    78.2   410.2   79.32  586.73   79.18  601.98   79.75
  643.82   79.91  663.39    79.4  771.77   84.16  852.82    85.9  863.39   86.54
  874.19   86.46  945.04   88.58  975.72   88.51  986.17   89.24 1012.51   89.41
#Mann= 7 ,-1 , 0
       0     .05       0  209.55     .09       0   315.3     .07       0
  347.29     .05       0  359.34     .07       0   410.2    .032       0
  643.82     .09       0
Bank Sta=347.29,359.34
XS Rating Curve= 0 ,0
Exp/Cntr=0.3,0.1

Type RM Length L Ch R = 1 ,7452    ,596.27,613.23,511.79
XS GIS Cut Line= 4
2350799.50503172623640.5969814362350962.83495876623793.927117035
2351522.82328008623907.2580868152351754.83759749624005.733473331
#Sta/Elev= 30
       0   93.51   10.71   93.62   65.25   87.47   105.1   83.99  168.19   77.05
  182.19   76.56  196.66   77.08  200.48   76.54   201.9   75.92  202.43   74.81
  203.66   73.62   206.5   72.76  209.96   73.46  211.48   76.05  212.52   76.52
   240.4   77.06  272.89   76.37  335.63   77.06   398.7   76.94  428.55   77.77
  617.62   76.91  681.12   79.35   741.1   84.54  771.62   86.57   808.9   87.19
  820.56   86.71  848.11   87.61  862.73   87.12  968.98   87.85 1047.41   89.33
#Mann= 5 ,-1 , 0
       0     .09       0  168.19     .07       0  200.48     .05       0
  212.52     .07       0  617.62     .09       0
Bank Sta=200.48,212.52
XS Rating Curve= 0 ,0
Exp/Cntr=0.3,0.1

Type RM Length L Ch R = 1 ,6839    ,449.41,517.62,503.62
XS GIS Cut Line= 5
2350396.28609304 624484.33850573        2350711.624363.062500015
2350794.75000003      624336.3752351352.74999999     624314.4375
 2351660.4043176 624368.44311671
#Sta/Elev= 30
       0   94.23   89.44    91.2  125.75    91.2   229.9   88.65  270.65   85.76
  322.36   84.36  380.88   79.35  409.95   76.26  420.55   74.01  430.51   74.51
  459.35   75.83  481.94   74.62  513.91   75.28  565.44   74.64  566.66   72.81
  568.18   71.74  572.16   70.68  576.58    71.5  578.44   74.04  579.94   74.54
  756.03   75.42  835.54    75.9  885.02    77.7  952.27   79.08  996.16   82.19
 1032.21   81.69 1082.55   84.26 1187.45   91.34 1236.73    91.3 1295.96   92.47
#Mann= 5 ,-1 , 0
       0     .09       0  430.51     .07       0  565.44     .05       0
  579.94     .07       0  756.03     .09       0
Bank Sta=565.44,579.94
XS Rating Curve= 0 ,0
Exp/Cntr=0.3,0.1

Type RM Length L Ch R = 1 ,6321    ,681.58,688.92,678.1
XS GIS Cut Line= 5
2350389.84746028624690.3747528342350638.00000003     624746.1875
2350748.00000003624772.750000015      2351253.75624871.500000015
2351389.98174323624898.557210863
#Sta/Elev= 30
       0   94.46  103.88   90.56  106.44   89.95  138.59   87.92  215.68   85.65
  285.42   80.81  294.87    79.8  320.32    75.7  365.45   74.41  403.16   74.84
  410.82   73.95  421.61   74.15  499.82   73.92  500.99    73.3  501.48   72.21
  502.68   71.06  505.96   70.29  508.79   70.92  509.99   71.66  511.41   73.81
  511.98   73.95  581.59   74.08  641.52   75.38  660.75   74.88  786.54   76.59
  824.74   77.58     870   80.49  939.91   88.82 1001.94   94.16 1021.71   95.02
#Mann= 4 ,-1 , 0
       0     .09       0  421.61     .07       0  499.82     .05       0
  511.98     .09       0
Bank Sta=499.82,511.98
XS Rating Curve= 0 ,0
Exp/Cntr=0.3,0.1

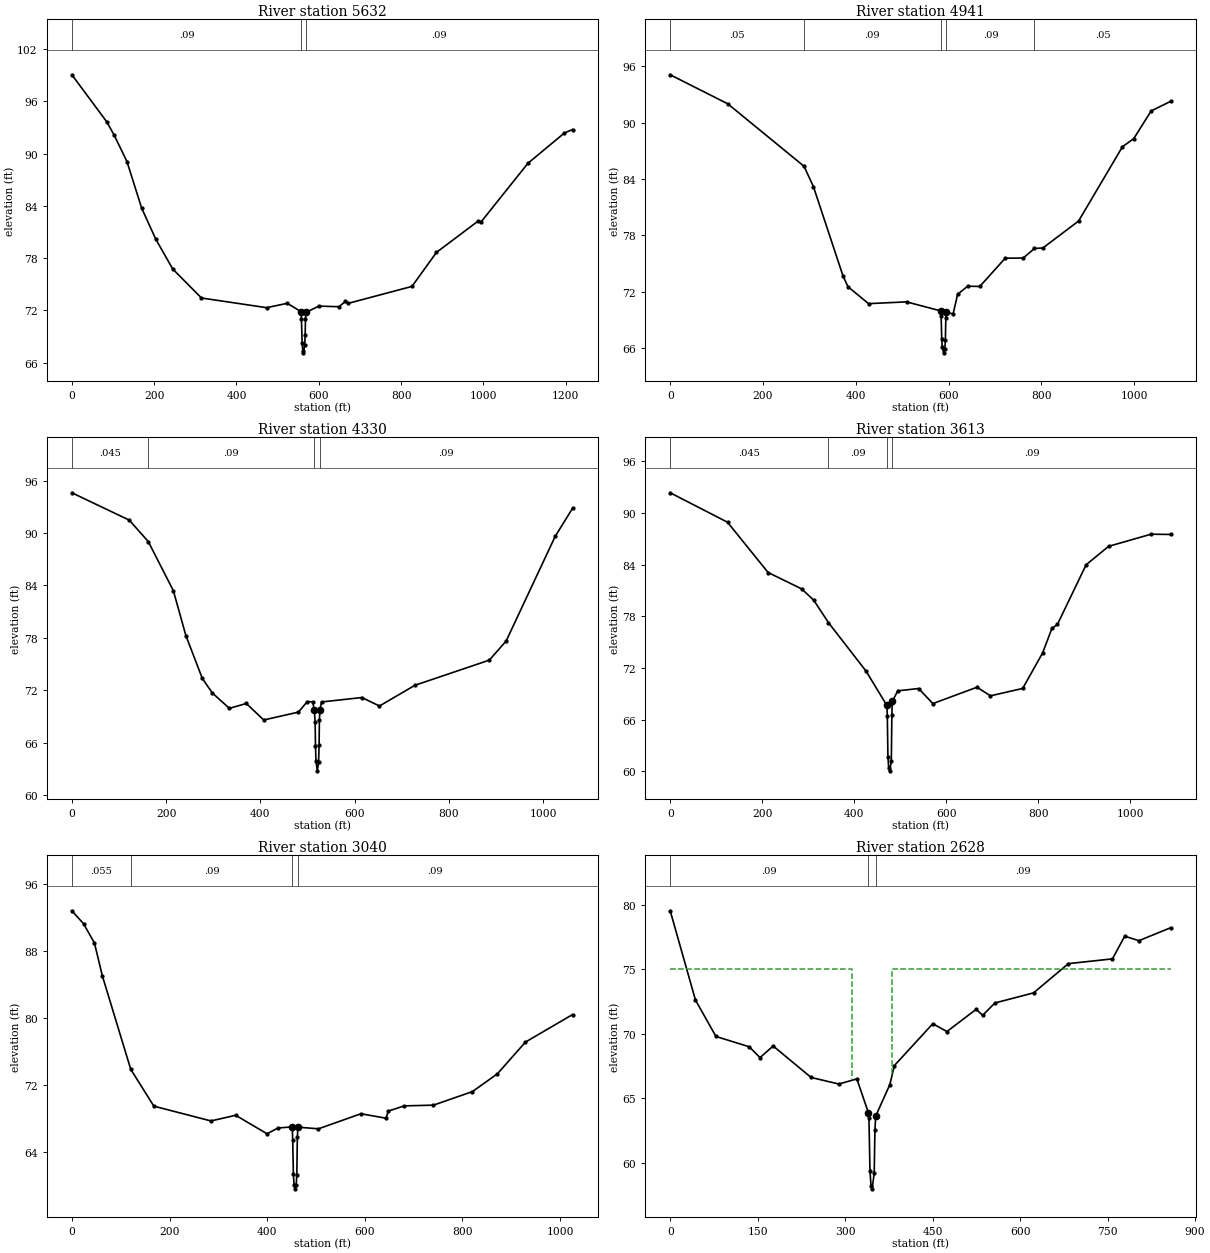
Type RM Length L Ch R = 1 ,5632    ,628.88,691.48,691.62
XS GIS Cut Line= 5
2350237.46648584 625312.775916042350437.25000001625398.437500015
      2350748.25625471.0625000152351113.75000004     625492.5625
2351426.46732862625516.665952265
#Sta/Elev= 30
       0   99.03   85.11   93.61  103.09   92.07  133.82   89.08  169.68   83.72
  204.03   80.16  245.15   76.75  314.91   73.43  473.11   72.32  523.31   72.82
  556.68   71.87  557.82   71.02  559.45   68.26  561.29   67.31   562.8   67.14
  565.84   68.03  566.82    69.2  567.67   71.05  568.72   71.78  600.32    72.5
  648.76   72.43  664.78   73.03   671.1   72.81  826.42   74.76  885.91   78.66
  987.35   82.26  995.11    82.2 1108.18   88.88 1196.69   92.35 1216.52   92.75
#Mann= 3 ,-1 , 0
       0     .09       0  556.68     .05       0  568.72     .09       0
Bank Sta=556.68,568.72
XS Rating Curve= 0 ,0
Exp/Cntr=0.3,0.1

Type RM Length L Ch R = 1 ,4941    ,598.27,610.71,602.79
XS GIS Cut Line= 5
2349967.04391153625866.498330191      2350240.75     625946.3125
      2350552.25626100.2500000152350685.00000003      626175.125
2350937.13124174626325.787464395
#Sta/Elev= 30
       0    95.1  123.96   92.01  288.46   85.35   308.7   83.17  372.58   73.64
   383.1   72.52  427.37   70.72  509.23   70.91  582.71   69.95  583.78    69.4
  585.07   66.98  586.26   66.06  589.08   65.48  591.81    65.9  592.91   66.88
  593.91    69.2   594.9    69.8  609.58   69.63  619.31   71.72  640.97   72.58
  667.07   72.55  721.81   75.56  760.77   75.58  784.88    76.6  803.05   76.65
   879.9   79.52  974.42   87.43   998.8    88.3 1036.33   91.25 1078.69   92.28
#Mann= 5 ,-1 , 0
       0     .05       0  288.46     .09       0  582.71     .05       0
   594.9     .09       0  784.88     .05       0
Bank Sta=582.71,594.9
XS Rating Curve= 0 ,0
Exp/Cntr=0.3,0.1

Type RM Length L Ch R = 1 ,4330    ,694.63,716.59,724.37
XS GIS Cut Line= 5
2349758.86145347626373.0041043612350006.50000001        626493.5
2350240.25000003         626616.2350449.50000004      626717.375
2350707.48667464 626851.60913676
#Sta/Elev= 30
       0   94.61  121.77   91.48  162.12   89.03  215.34   83.41  241.96   78.27
  276.89   73.36  298.16    71.7  334.34   69.94  370.27    70.5  407.19   68.61
   480.9   69.51  499.61   70.71  511.08   70.68  514.63   69.74  516.28    68.4
  517.09   65.63  518.05   63.95  520.92   62.79  523.66    63.8  524.76   65.76
  525.35   68.64  526.65   69.76  529.86   70.67  615.38   71.18  652.87   70.21
  728.11   72.58  886.07   75.46   921.7   77.64 1025.76   89.61 1062.64   92.83
#Mann= 4 ,-1 , 0
       0    .045       0  162.12     .09       0  514.63     .05       0
  526.65     .09       0
Bank Sta=514.63,526.65
XS Rating Curve= 0 ,0
Exp/Cntr=0.3,0.1

Type RM Length L Ch R = 1 ,3613    ,539.05,573.85,550.08
XS GIS Cut Line= 6
2349462.68434824626885.948511273        2349678.         627057.
      2349892.25      627232.3752350005.50000001627322.625000015
      2350248.25     627364.18752350391.99367122627388.161863655
#Sta/Elev= 30
       0   92.34  124.65   88.92  212.93   83.08  285.87   81.18  312.09   79.87
   344.2   77.26  425.93   71.63  470.97   67.66  471.49   67.54  472.15   66.37
   473.5   61.64  475.13   60.41  477.23   60.05  480.86   61.16  482.08   66.58
  482.77   67.88  483.38   68.14  494.78   69.34  540.23   69.61  571.22   67.86
  667.18   69.76  696.48   68.76  766.57   69.62  809.86   73.74  830.13   76.59
  842.01   77.05   904.5   83.98  953.34   86.12 1045.65   87.53 1088.69    87.5
#Mann= 4 ,-1 , 0
       0    .045       0   344.2     .09       0  470.97     .05       0
  483.38     .09       0
Bank Sta=470.97,483.38
XS Rating Curve= 0 ,0
Exp/Cntr=0.3,0.1

Type RM Length L Ch R = 1 ,3040    ,410.67,411.67,368.67
XS GIS Cut Line= 5
2349157.63210227627340.5318263472349224.22916667627387.083333373
2349538.75000009        627629.52349769.75000006 627876.56250003
 2349930.1290839628010.348405764
#Sta/Elev= 30
       0   92.83   23.94   91.28   46.28   88.97   62.37   85.06  120.57   73.89
  167.85   69.49  284.89   67.72  335.44    68.4  399.68   66.19  422.38   66.88
  450.99   67.01  451.61   66.72  452.33   65.42   453.7   61.33   455.1   60.12
  457.15   59.61  459.38   60.03  460.75   61.28   461.8    65.8  463.09   66.98
  505.06   66.78  591.97   68.58  643.45   68.05  648.16    68.9  680.74   69.52
  740.63   69.61  820.51   71.23  871.72   73.36  928.96   77.14 1025.44   80.43
#Mann= 4 ,-1 , 0
       0    .055       0  120.57     .09       0  450.99     .05       0
  463.09     .09       0
Bank Sta=450.99,463.09
XS Rating Curve= 0 ,0
Exp/Cntr=0.5,0.3

Type RM Length L Ch R = 1 ,2628    ,201.97,200.78,190.23
XS GIS Cut Line= 5
2349023.08343731627755.8438390052349306.50010398627954.729255661
2349306.50010398 627954.750088992349317.00010398627962.125089005
2349779.20378092628150.968152314
#Sta/Elev= 30
       0   79.54   43.28   72.62   78.47   69.79   135.5   68.99  153.98   68.15
  176.56   69.05  241.57   66.61  289.21    66.1  319.99    66.5  339.75   63.89
  340.75    63.5  342.51   59.39  344.33   58.22  346.26   57.97   349.8   59.19
  351.03   62.56  352.37   63.62  376.56   66.05  384.32   67.53  450.27   70.78
   474.5   70.17  524.68    71.9  535.69   71.43  556.83   72.39  622.97   73.17
  682.73   75.44  758.31   75.81  779.27   77.57  803.59   77.22  858.38   78.23
#Mann= 3 ,-1 , 0
       0     .09       0  339.75     .05       0  352.37     .09       0
#XS Ineff= 2 , 0
       0     311   75.03     381       0   75.05
Permanent Ineff=
       F       F
Bank Sta=339.75,352.37
XS Rating Curve= 0 ,0
Exp/Cntr=0.5,0.3

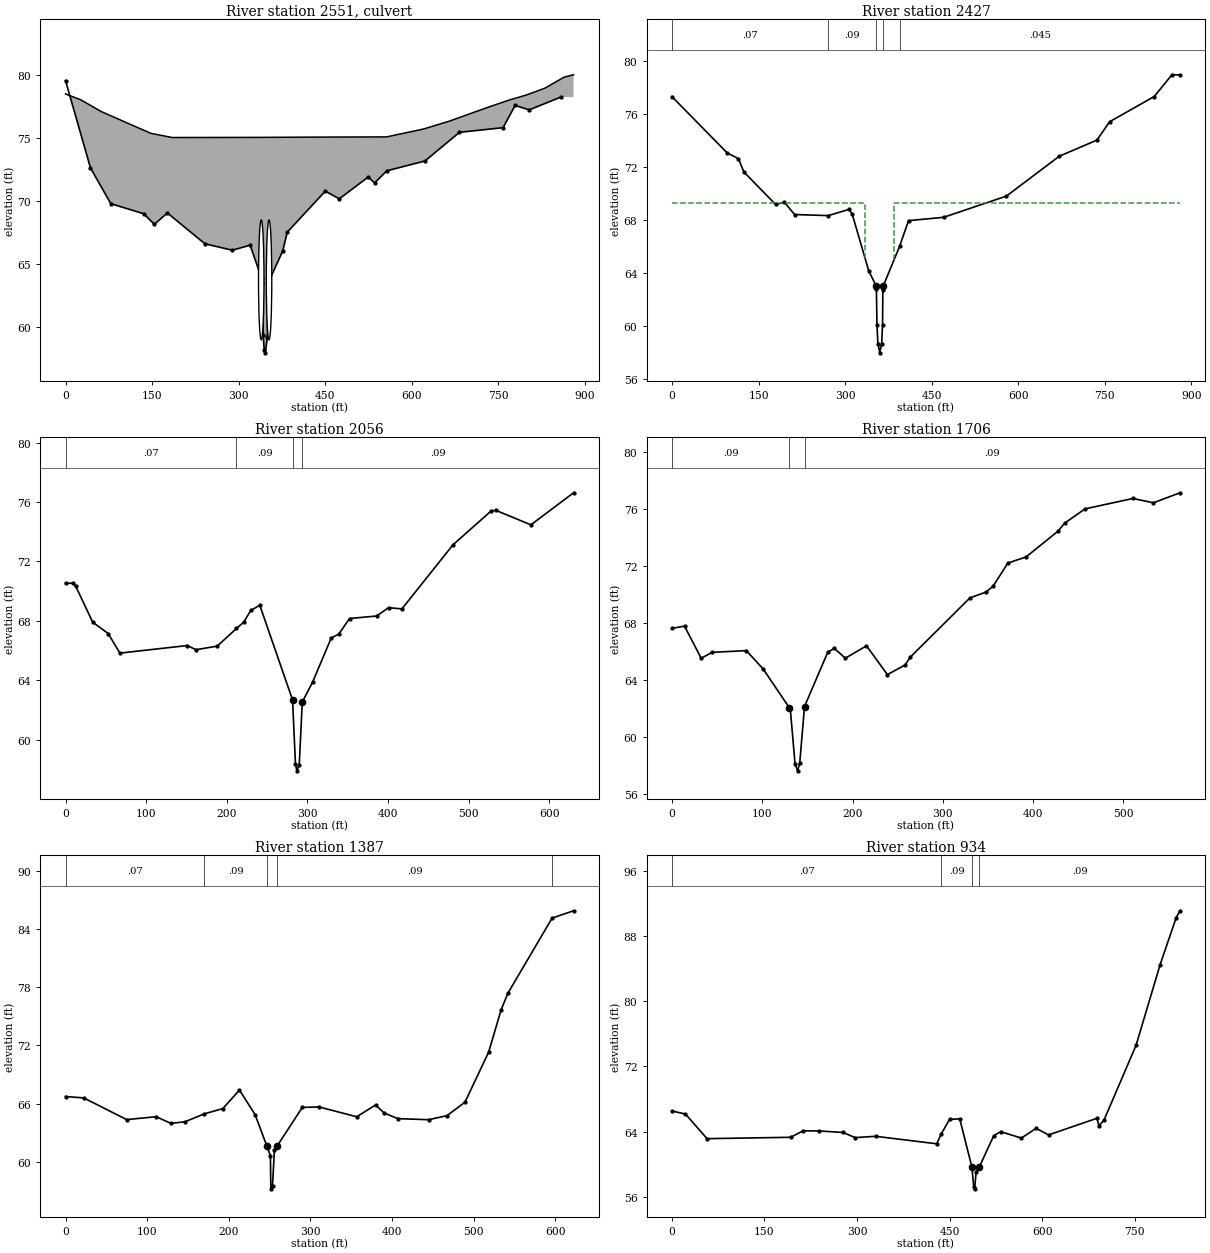
Type RM Length L Ch R = 2 ,2551    ,,,
Bridge Culvert--1,0,-1,-1, 0
Deck Dist Width WeirC Skew NumUp NumDn MinLoCord MaxHiCord MaxSubmerge Is_Ogee
66,23,2.6,0, 17, 17, , , 0.98, 0, 1,1,,
       0   26.33   62.24  119.46  148.04   184.9  335.24  421.36  556.63  620.27
  664.78     735  768.31  798.76  830.85  864.06  880.49
   78.48   78.02   77.08   75.93   75.36   75.03   75.04   75.06   75.08    75.7
   76.32   77.47   77.99    78.4   78.94   79.81      80
                                                                                
                                                        
       0   26.33   62.24  119.46  148.04   184.9  335.24  421.36  556.63  620.27
  664.78     735  768.31  798.76  830.85  864.06  880.49
   78.48   78.02   77.08   75.93   75.36   75.03   75.04   75.06   75.08    75.7
   76.32   77.47   77.99    78.4   78.94   79.81      80
                                                                                
                                                        
BR Coef=-1 , 1 , 0 ,1.25, 0 ,,,0.8,0,2,0,
WSPro=,,,, 1 ,,,, 0 ,,,, 0 ,,,,-1 ,-1 ,-1 , 0 , 0 , 0 , 0 , 0
Multiple Barrel Culv=1,9.5,,81,0.024,0.7,1,2,2,59,58.2, 2,Culvert #1  , 0 ,36.5
  339.25  353.25  352.75  366.75
Culvert Bottom n=0.024
BC Design=,, 0 ,, 0 ,,,,,,
BC Use User HTab Curves=0
BC User HTab FreeFlow(D)= 0

Type RM Length L Ch R = 1 ,2427    ,347.79,371.26,362.76
XS GIS Cut Line= 3
2348907.46039085 627937.882251622349212.07588856628130.838049188
2349712.04597066628273.432394624
#Sta/Elev= 30
       0   77.29   96.12   73.03  115.19   72.62  124.48   71.62  179.58   69.16
   194.9   69.33  212.45    68.4  270.71   68.32  307.06   68.79  312.53   68.41
  340.89   64.17  353.79   63.02  354.32   62.76  355.25   60.07  356.94   58.67
  360.21   57.97  363.39   58.67  364.92   60.04   365.5    62.7  366.21   63.02
  394.42   65.99  409.99   67.94  470.72   68.19   579.6   69.79   671.3    72.8
  736.37   74.01  758.55    75.4   835.8    77.3  866.37   78.94  880.49   78.93
#Mann= 5 ,-1 , 0
       0     .07       0  270.71     .09       0  353.79     .05       0
  366.21     .09       0  394.42    .045       0
#XS Ineff= 2 , 0
       0     335   69.25     385       0   69.25
Permanent Ineff=
       F       F
Bank Sta=353.79,366.21
XS Rating Curve= 0 ,0
Exp/Cntr=0.5,0.3

Type RM Length L Ch R = 1 ,2056    ,349,349.76,283.53
XS GIS Cut Line= 3
 2348733.7313858628247.1165908872349044.56390777628426.393439665
2349228.99980256628625.016710967
#Sta/Elev= 30
       0   70.51    9.57   70.54   12.56   70.34   33.73    67.9   52.92   67.14
   67.43   65.82  150.97   66.33  161.71   66.05  188.08   66.29     212   67.48
  220.85    67.9   229.8    68.7   240.9   69.04  281.49   62.67  285.14   58.32
  286.91   57.89  289.81   58.31  293.59   62.53  306.45   63.88  329.47   66.84
  338.77    67.1  352.15   68.15  385.76   68.32  400.57   68.88   417.1    68.8
  480.49   73.12  527.62   75.39  533.41   75.44  576.99   74.46  629.88   76.62
#Mann= 4 ,-1 , 0
       0     .07       0     212     .09       0  281.49     .05       0
  293.59     .09       0
Bank Sta=281.49,293.59
XS Rating Curve= 0 ,0
Exp/Cntr=0.3,0.1

Type RM Length L Ch R = 1 ,1706    ,304.46,319.54,290.24
XS GIS Cut Line= 2
2348652.47641115628650.8119410132349214.81242603628668.868602037
#Sta/Elev= 30
       0   67.62   13.91   67.78   32.38   65.52   44.45   65.94   82.36   66.06
  100.78   64.79  130.05   62.05  131.04   61.97  136.29   58.11  139.15   57.63
   141.5   58.19  146.78   62.14  172.48   65.94  179.65   66.22  192.02   65.53
  215.41    66.4  238.56   64.38  258.19   65.05  263.69   65.59  330.04   69.76
  347.93   70.17  355.76   70.59  371.93    72.2  392.13   72.63  427.56   74.44
  434.88      75  457.38      76  510.41   76.73  533.24   76.43  562.63   77.13
#Mann= 3 ,-1 , 0
       0     .09       0  130.05     .05       0  146.78     .09       0
Bank Sta=130.05,146.78
XS Rating Curve= 0 ,0
Exp/Cntr=0.3,0.1

Type RM Length L Ch R = 1 ,1387    ,448.72,452.69,408.17
XS GIS Cut Line= 2
2348602.17571257628965.5137475132349222.55099505628917.792571917
#Sta/Elev= 30
       0   66.72   22.26   66.58   74.92   64.34  111.01   64.64  129.12   63.95
  146.38   64.12  169.88   64.93  192.72   65.48  213.04   67.39  232.16   64.86
  246.77   61.58  250.94   60.63  251.47    57.2  253.51   57.53  255.86   61.19
  258.84   61.57  290.03    65.6   310.5   65.65  356.65   64.63  379.68   65.85
  390.33   65.02  407.09   64.44  444.68   64.33  467.26   64.75  489.25   66.14
  518.18   71.29  533.39   75.63  541.62   77.35  595.89   85.12  622.21   85.88
#Mann= 5 ,-1 , 0
       0     .07       0  169.88     .09       0  246.77     .05       0
  258.84     .09       0  595.89     .05       0
Bank Sta=246.77,258.84
XS Rating Curve= 0 ,0
Exp/Cntr=0.3,0.1

Type RM Length L Ch R = 1 ,934     ,578.79,569.1,507.58
XS GIS Cut Line= 2
2348514.47193043629485.2876328232349307.67525415629263.448654473
#Sta/Elev= 30
       0   66.52   21.89   66.14   56.89   63.12  192.49   63.29  212.35   64.08
  238.04   64.07   277.4   63.88  296.83   63.25  330.13   63.41  429.35   62.49
  436.51    63.7  449.96   65.48  466.51   65.56  486.29   59.62  489.23   57.14
  490.74   56.96  492.95   58.97  498.34   59.65  521.68    63.5  532.91   63.98
  566.45   63.19  590.34   64.39  610.56   63.58  688.89   65.62   692.1   64.71
   700.3   65.38  752.39   74.58  791.24   84.45  817.52   90.27  823.64    91.1
#Mann= 4 ,-1 , 0
       0     .07       0  436.51     .09       0  486.29     .05       0
  498.34     .09       0
Bank Sta=486.29,498.34
XS Rating Curve= 0 ,0
Exp/Cntr=0.3,0.1

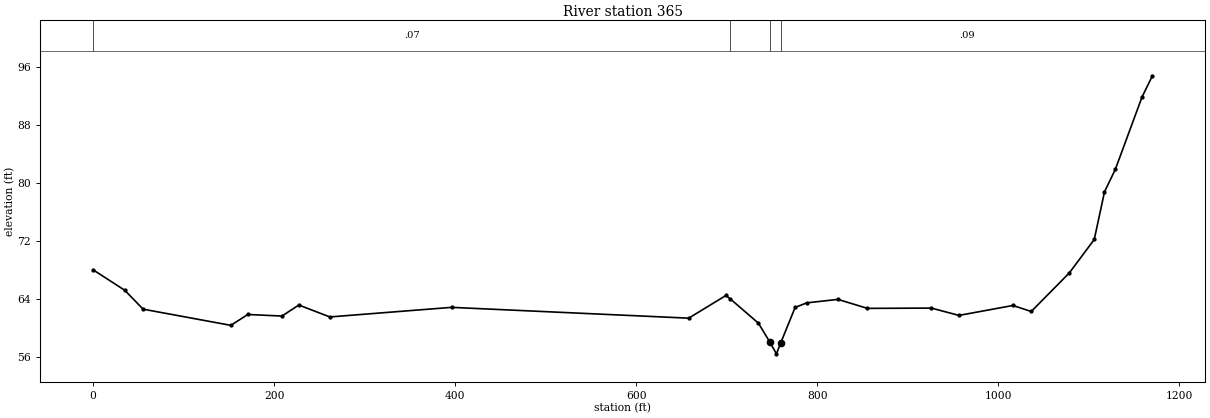
Type RM Length L Ch R = 1 ,365     ,295.51,364.8,459.43
XS GIS Cut Line= 4
2348441.43918538629908.4906256942349055.68810074629935.898057595
  2349223.357096629869.7977806332349487.75820392629603.784470826
#Sta/Elev= 30
       0   68.09   34.85   65.28   55.29   62.66  152.15   60.43  170.96   61.93
  208.59   61.71  227.28   63.23  261.52   61.59  395.96   62.91  657.91   61.42
  699.04   64.55  703.52   64.11  734.92   60.73  747.34   58.16  754.81    56.5
  759.57   58.01  775.45    62.9  788.25   63.53  822.77   64.01  855.32   62.77
  925.97   62.81  956.42    61.8 1016.01   63.17 1036.29   62.34 1078.32   67.66
 1105.87   72.27 1117.18   78.84 1129.18   81.95 1158.66   91.93 1170.15   94.85
#Mann= 4 ,-1 , 0
       0     .07       0  703.52     .09       0  747.34     .05       0
  759.57     .09       0
Bank Sta=747.34,759.57
XS Rating Curve= 0 ,0
Exp/Cntr=0.3,0.1

Chan Stop Cuts=-1
Use User Specified Reach Order=0