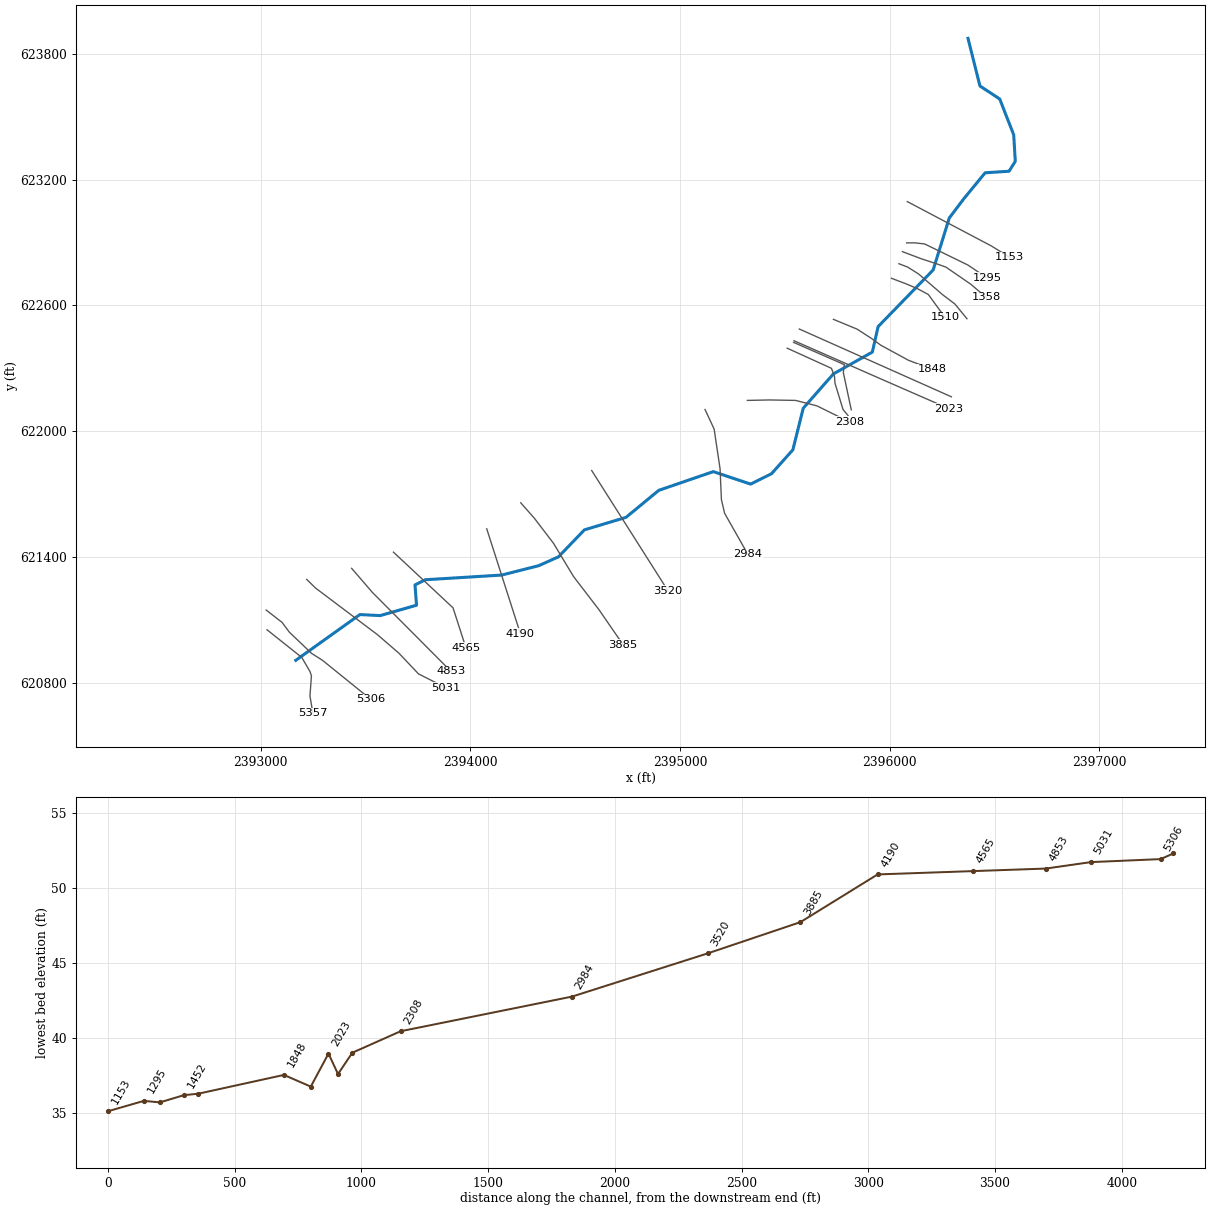
--- LDS_Contentnea_Crk_Trib8.prj (project) ---

Proj Title=LDS_Contentnea_Crk_Trib8
Current Plan=p01
Default Exp/Contr=0.3,0.1
English Units
Geom File=g01
Flow File=f02
Flow File=f01
Plan File=p02
Plan File=p01
Y Axis Title=Elevation
X Axis Title(PF)=Main Channel Distance
X Axis Title(XS)=Station
BEGIN DESCRIPTION:
END DESCRIPTION:
DSS Export Rating Curves= 0
DSS Export Rating Curve Sorted= 0
DSS Export Volume Flow Curves= 0
DXF OffsetX= 0
DXF OffsetY= 0
DXF ScaleX= 1
DXF ScaleY= 10

--- LDS_Contentnea_Crk_Trib8.p01 (plan) ---

Plan Title=LDS_Contentnea_Crk_Trib8
Program Version=4.00
Short Identifier=Fway
Geom File=g01
Flow File=f01
Subcritical Flow
K Sum by GR= 0
Std Step Tol= 0.01
Critical Tol= 0.01
Num of Std Step Trials= 20
Max Error Tol= 0.3
Flow Tol Ratio= 0.001
Split Flow NTrial= 30
Split Flow Tol= 0.02
Split Flow Ratio= 0.02
Log Output Level= 0
Friction Slope Method= 1
Unsteady Friction Slope Method= 2
Unsteady Bridges Friction Slope Method= 1
Parabolic Critical Depth
Global Vel Dist= 0 , 0 , 0
Global Log Level= 0
CheckData=True
Encroach Param=-1 ,5,5, 2
Encroach River=Contentnea Trib8
Encroach Reach=Main
Encroach Node=5357
       1     177     250
Encroach Node=5306
       1   276.5   303.5
Encroach Node=5031
       1   271.5   308.5
Encroach Node=4853
       4      .7
Encroach Node=4565
       1     180     230
Encroach Node=4190
       1     224     239
Encroach Node=3885
       1     290     320
Encroach Node=3520
       1     265     285
Encroach Node=2984
       4      .7
Encroach Node=2308
       4      .7
Encroach Node=2117
       1  242.34   270.4
Encroach Node=2061
       1  268.35   296.8
Encroach Node=2023
       1     290     325
Encroach Node=1953
       1     317     351
Encroach Node=1848
       4      .7
Encroach Node=1510
       1      92     164
Encroach Node=1452
       1   133.5  166.51
Encroach Node=1358
       1     155   181.5
Encroach Node=1295
       1     163     195
Encroach Node=1153
       1     203     227
Encroach Node=1074
       1   204.7  220.45
Encroach Node=977
       1   239.5   261.6
Encroach Node=862
       1     198  219.97
Encroach Node=635
       1     310     345
Encroach Node=387
       1     258  305.08
Encroach Node=314
       1     238  291.02
Computation Interval=1HOUR
Output Interval=1HOUR
Run HTab= 0
Run UNet= 0
Run PostProcess= 0
Run WQNet= 0
UNET Theta= 1
UNET Theta Warmup= 1
UNET ZTol= 0.02
UNET ZSATol= 0.05
UNET MxIter= 20
UNET MaxInSteps= 0
UNET DtIC= 0
UNET DtMin= 0
UNET MaxCRTS= 20
UNET WFStab= 2
UNET SFStab= 1
UNET WFX= 1
UNET SFX= 1
UNET DSS MLevel= 4
UNET DZMax Abort= 100
UNET Convert EG Bridges=-1
UNET Use Existing IB Tables=-1
UNET Froude Reduction=False
UNET Froude Limit= 1
UNET Froude Power= 10
UNET Time Slicing=0,0, 5
Instantaneous Interval=1HOUR
Write IC File= 0
Echo Input=False
Echo Output=False
Write Detailed= 0
Detailed Automatic Start=False, 10
WQ ULTIMATE=-1
WQ Max Comp Step=1HOUR
WQ Output Interval=15MIN
WQ Output Selected Increments= 0
WQ Output face flow=0
WQ Output face velocity=0
WQ Output face area=0
WQ Output face dispersion=0
WQ Output cell volume=0
WQ Output cell surface area=0
WQ Output cell continuity=0
WQ Output face conc=0
WQ Output face dconc_dx=0
WQ Output face courant=0
WQ Output face peclet=0
WQ Output face adv mass=0
WQ Output face disp mass=0
WQ Output cell mass=0
WQ Output cell source sink temp=0
WQ Output cell source sink nsm=0
WQ Output MaxMinRange=-1
WQ Daily Max Min Mean=-1
WQ Daily Range=0
WQ Daily Time=0
WQ Create Restart=0
WQ Fixed Restart=0
WQ System Summary=False
Sorting and Armoring Iterations= 10
XS Update Threshold= 0.02
Hydraulics Update Threshold= 0.02
Energy Slope Method= 1
Volume Change Method= 0
XS Weighting Method= 0
Number of US Weighted Cross Sections= 1
Number of DS Weighted Cross Sections= 1
Upstream XS Weight=0.25
Main XS Weight=0.5
Downstream XS Weight=0.25
Number of DS XS's Weighted with US Boundary= 1
Upstream Boundary Weight= 1
Weight of XSs Associated with US Boundary= 0
Number of US XS's Weighted with DS Boundary= 1
Downstream Boundary Weight= 0.5
Weight of XSs Associated with DS Boundary= 0.5
Sediment Output Level= 4
Mass or Volume Output= 0
Output Increment Type= 1
Profile and TS Output Increment= 10
XS Output Flag= 0
XS Output Increment= 10
Disregard all LS=0
Disregard all Conn=0
Disregard all Breaches=0
Disregard all Pumps=0

--- LDS_Contentnea_Crk_Trib8.p02 (plan) ---

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Plan Title=Multi_Profile
Program Version=3.13
Short Identifier=Multi_Pro
Geom File=g01
Flow File=f02

--- LDS_Contentnea_Crk_Trib8.f01 (steady flow) ---

Flow Title=LDS_Contentnea_Crk_Trib8
Program Version=3.13
Number of Profiles= 2
Profile Names=Wsel100,Wselfway
River Rch & RM=Contentnea Trib8,Main            ,5357
     520     520
Boundary for River Rch & Prof#=Contentnea Trib8,Main            , 1
Up Type= 0
Dn Type= 3
Dn Slope=0.0045
Boundary for River Rch & Prof#=Contentnea Trib8,Main            , 2
Up Type= 0
Dn Type= 3
Dn Slope=0.0045
DSS Import GetInterval= 0
DSS Import GetPeak= 0
DSS Import FillOption= 0

--- LDS_Contentnea_Crk_Trib8.f02 (steady flow) ---

Flow Title=Multi_Profile
Program Version=4.00
Number of Profiles= 8
Profile Names=10-yr,25-yr,50-yr,500-yr,100-yr-10%,100-yr-20%,100-yr-35%,100-yr
River Rch & RM=Contentnea Trib8,Main            ,5357
     210     310     410     850     910    1160    1420     520
Boundary for River Rch & Prof#=Contentnea Trib8,Main            , 1
Up Type= 0
Dn Type= 3
Dn Slope=0.0045
Boundary for River Rch & Prof#=Contentnea Trib8,Main            , 2
Up Type= 0
Dn Type= 3
Dn Slope=0.0045
DSS Import GetInterval= 0
DSS Import GetPeak= 0
DSS Import FillOption= 0

--- LDS_Contentnea_Crk_Trib8.g01 (geometry) ---

Geom Title=LDS_Contentnea_Crk_Trib8
Program Version=4.00

River Reach=Contentnea Trib8,Main
Reach XY= 30
 2393167.3451322  620907.8125193 2393472.9909658  621125.9375195
 2393569.5117992  621121.0000195 2393743.0013827  621170.5625196
 2393735.7513827  621267.1875197 2393785.2513828  621292.0000197
 2394149.5013831  621314.3125197 2394325.5013833  621358.9375198
 2394419.7513834  621401.0625198 2394543.7513835  621529.9375199
 2394742.0118003    621589.43752 2394898.2513838  621718.3125201
 2395158.4076341  621807.5521035 2395336.7513842  621748.0625201
 2395435.9909676  621797.6146035 2395537.7513844  621911.6250203
 2395587.2513845  622109.9375205 2395730.9701346  622273.5416873
 2395916.7513848  622377.6250207 2395944.2409681  622499.0521041
  2396206.751385  622769.2500211 2396283.7513851   623017.135438
 2396353.0534685   623108.885438 2396454.7513853  623232.7500215
 2396568.7513854  623240.1875215 2396598.5013854  623287.3125215
 2396591.0013854  623413.6875217 2396524.2513853  623584.7500218
 2396430.0013852  623646.6875219 2396373.0013852  623873.9375221

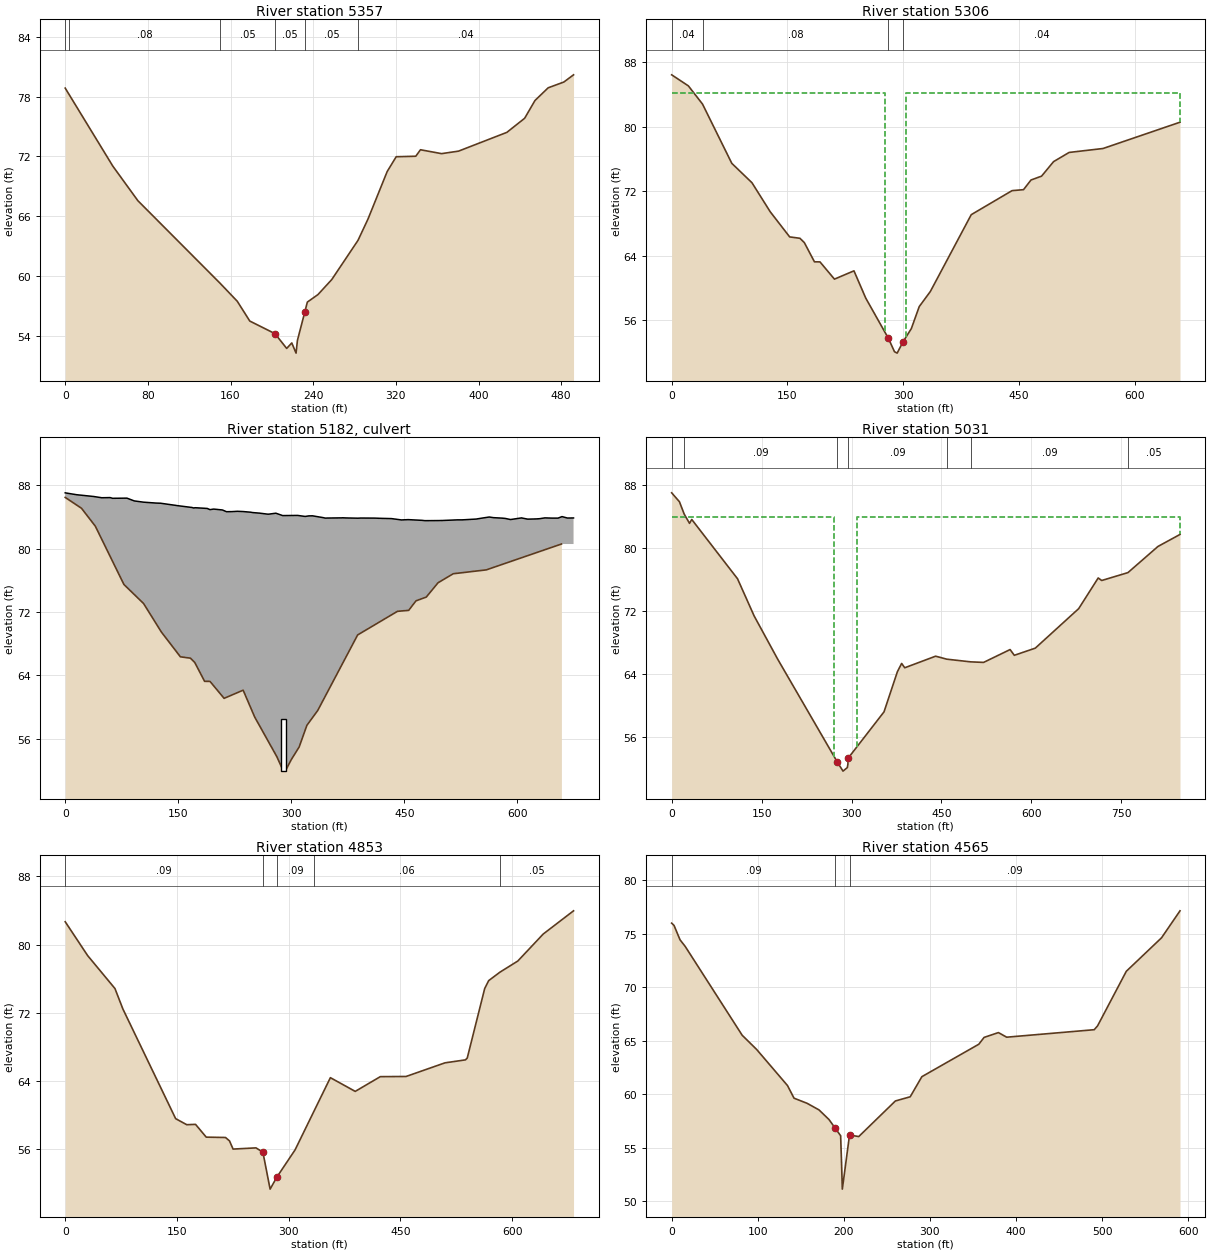
Type RM Length L Ch R = 1 ,5357    ,50.64,50.86,57.21
XS GIS Cut Line= 6
 2393029.9896873  621053.3855057 2393195.8646873  620921.4896723
 2393234.8334373   620854.531339 2393241.8334373  620833.5521723
 2393234.8334373   620737.625089 2393248.8230207   620654.687589
#Sta/Elev= 30
       0   78.84     3.3   78.28   46.08   71.03   70.32   67.57  149.83   59.31
  166.52    57.5  178.62   55.52  202.99   54.26  214.32   52.78  219.26   53.33
  223.39   52.31  224.71   53.58  231.74   56.38  234.33   57.42  244.57   58.17
  257.91   59.67  283.34    63.6  293.08   65.75  311.58   70.49  320.29   71.97
  339.24   72.02  343.79   72.67  364.19   72.28  380.59   72.53  427.39   74.41
  444.59   75.82   454.6    77.6  467.36   78.87  482.56   79.45   491.9   80.17
#Mann= 6 ,-1 , 0
       0     .04       0     3.3     .08       0  149.83     .05       0
  202.99     .05       0  231.74     .05       0  283.34     .04       0
#XS Ineff= 2 , 0
       0     177             256       0
Permanent Ineff=
       F       F
Bank Sta=202.99,231.74
XS Rating Curve= 0 ,0
Exp/Cntr=0.5,0.3

Type RM Length L Ch R = 1 ,5306    ,271.8,275.02,282.99
XS GIS Cut Line= 6
 2393026.0105207   621147.406339 2393101.9584373  621088.4584223
 2393136.9271873  621041.4896723 2393242.8542707   620940.562589
  2393294.812604   620907.593839 2393524.6355207  620721.7292557
#Sta/Elev= 30
       0   86.46   21.61   85.09   39.97   82.83   77.88   75.48  104.04   73.07
  127.67   69.47  152.87   66.35  166.15   66.18  171.88   65.64  184.98   63.26
  192.14   63.25  210.88   61.11  236.15   62.14  251.46   58.75   280.8   53.76
  288.63   52.11  292.12   51.93  299.77   53.34  310.47   54.97   320.7    57.7
  335.13   59.58  388.11   69.11  440.97   72.09  455.82   72.21   465.5   73.41
  479.21   73.89  494.77   75.69  514.93   76.83  558.89   77.32  658.54   80.58
#Mann= 4 ,-1 , 0
       0     .04       0   39.97     .08       0   280.8     .05       0
  299.77     .04       0
#XS Ineff= 2 , 0
       0   276.5   84.17   303.5       0   84.17
Permanent Ineff=
       T       T
Bank Sta=280.8,299.77
XS Rating Curve= 0 ,0
Exp/Cntr=0.5,0.3

Type RM Length L Ch R = 2 ,5182    ,,,
BEGIN DESCRIPTION:
Kingold Road
END DESCRIPTION:
Bridge Culvert--1,0,-1,-1, 0
Deck Dist Width WeirC Skew NumUp NumDn MinLoCord MaxHiCord MaxSubmerge Is_Ogee
105,43,2.6,0, 81, 82, , , 0.95, 0, 1,1,,
       0     8.7   15.35   35.45   37.62   48.52    59.6   62.85   81.94   91.64
  104.14  120.42   126.4   147.3  148.22   148.3   148.4  168.36  170.32  172.74
  188.43  192.13  196.94  208.57     214  221.16  228.51  235.87  245.68  248.77
  257.74  268.81  270.03  279.59  288.57  308.51  318.34  323.28  328.18   342.4
  345.16  347.91  366.45  367.07   367.7  373.46  388.86  392.22  410.88  419.15
  432.99  446.22  455.08  473.37  477.37     495  499.45  499.79  500.54  520.53
  522.42  526.75  541.73  545.28  553.07  562.86  568.12  579.44  584.04  590.95
  605.01  605.35  613.79  625.55  629.76  636.58  645.96  654.03   659.3  666.51
  674.58
   87.04    86.9    86.8    86.6   86.58   86.42   86.44   86.35   86.37   86.02
   85.86   85.75   85.73   85.45   85.43   85.43   85.43   85.19   85.13   85.16
   85.07   84.92   84.99   84.88   84.66   84.67   84.71   84.68    84.6   84.55
   84.48   84.35   84.35   84.47   84.17   84.19   84.06   84.13   84.14   83.91
   83.85   83.86   83.88   83.88   83.89   83.87   83.84   83.86   83.85   83.82
   83.79   83.62   83.66   83.57   83.53   83.54   83.55   83.54   83.55   83.63
   83.63   83.63   83.71   83.73   83.85   83.99   83.91   83.85   83.81   83.67
   83.87   83.88   83.72   83.75   83.78   83.88   83.85   83.85   84.04   83.86
   83.87
                                                                                
                                                                                
                                                                                
                                                                                
                                                                                
                                                                                
                                                                                
                                                                                
        
       0     8.7   15.35   35.45   37.62   48.52    59.6   62.85   81.94   91.64
  104.14  120.42   126.4   147.3  148.22   148.3   148.4  168.36  170.32  172.74
  188.43  192.13  196.94  208.57     214  221.16  228.51  235.87  245.68  248.77
  257.74  268.81  270.03  279.59  288.57  308.51  318.34  323.28  328.18   342.4
  345.16  347.91  366.45  367.07   367.7  373.46  388.86  392.22  410.88  419.15
  432.99  446.22  455.08  473.37  477.37     495  499.45  499.79  500.54  520.53
  522.42  526.75  541.73  545.28  553.07  562.86  568.12  579.44  584.04  590.95
  605.01  605.35  613.79  625.55  629.76  636.58  645.96  654.03   659.3  666.51
  674.58   847.8
   87.04    86.9    86.8    86.6   86.58   86.42   86.44   86.35   86.37   86.02
   85.86   85.75   85.73   85.45   85.43   85.43   85.43   85.19   85.13   85.16
   85.07   84.92   84.99   84.88   84.66   84.67   84.71   84.68    84.6   84.55
   84.48   84.35   84.35   84.47   84.17   84.19   84.06   84.13   84.14   83.91
   83.85   83.86   83.88   83.88   83.89   83.87   83.84   83.86   83.85   83.82
   83.79   83.62   83.66   83.57   83.53   83.54   83.55   83.54   83.55   83.63
   83.63   83.63   83.71   83.73   83.85   83.99   83.91   83.85   83.81   83.67
   83.87   83.88   83.72   83.75   83.78   83.88   83.85   83.85   84.04   83.86
   83.87   83.87
                                                                                
                                                                                
                                                                                
                                                                                
                                                                                
                                                                                
                                                                                
                                                                                
                
BR Coef=-1 , 1 , 0 ,1.25, 0 ,,,0.8,0,2,0,
WSPro=,,,, 1 ,,,, 0 ,,,, 0 ,,,,-1 ,-1 ,-1 , 0 , 0 , 0 , 0 , 0
Culvert=2,6.5,7,250,0.012,0.4,1,59,1,52,290,51.8,290,Culvert #1  , 0 ,16
Culvert Bottom n=0.012
BC Design=,, 0 ,, 0 ,,,,,,
BC Use User HTab Curves=0
BC User HTab FreeFlow(D)= 0

Type RM Length L Ch R = 1 ,5031    ,153.93,178.02,155.08
XS GIS Cut Line= 6
  2393219.187604  621293.6355057  2393261.156354  621252.6667557
 2393556.9271873  621029.8334223 2393658.8542707  620941.8959223
 2393752.3646873   620843.125089 2393883.1355207  620776.8230057
#Sta/Elev= 30
       0   87.03   12.94    85.9   21.03   84.31   29.77   83.16   33.51   83.65
  109.85   76.13  137.45   71.43   176.6   65.96  276.53   52.85  285.77   51.73
  292.97   52.18  293.92    52.6  294.26   53.37  354.18   59.25  376.41   64.33
  383.55   65.39  388.73   64.84  440.22   66.31  458.75   65.93  498.76   65.59
  520.23   65.52  564.44   67.15  571.45   66.42  606.48   67.33  678.83   72.34
  711.38   76.23  717.28   75.91  760.99   76.91   811.1   80.23   847.8   81.75
#Mann= 7 ,-1 , 0
       0     .05       0   21.03     .09       0  276.53     .05       0
  294.26     .09       0  458.75     .06       0  498.76     .09       0
  760.99     .05       0
#XS Ineff= 2 , 0
       0   271.5      84   308.5       0      84
Permanent Ineff=
       F       F
Bank Sta=276.53,294.26
XS Rating Curve= 0 ,0
Exp/Cntr=0.5,0.3

Type RM Length L Ch R = 1 ,4853    ,223.61,288.18,243.57
XS GIS Cut Line= 3
  2393433.562604621346.4584223182393532.11468735621232.073005646
2393906.93760401620855.489672318
#Sta/Elev= 30
       0   82.68    30.1   78.71   66.78   74.84   77.38   72.45  148.25   59.57
  163.11   58.86  174.92    58.9  189.32    57.4  215.16   57.36  220.53   56.96
  225.33      56  256.05   56.14  265.35   55.64  275.04    51.3  284.11   52.71
  308.57   55.91  334.33   60.52  355.94   64.38   389.3   62.77  422.96    64.5
  457.53   64.52  509.77   66.12  537.27   66.47  539.67   66.69  563.07   74.84
  568.44   75.77  583.51   76.76  607.53   78.07  641.67   81.24  682.31   83.96
#Mann= 5 ,-1 , 0
       0     .09       0  265.35     .05       0  284.11     .09       0
  334.33     .06       0  583.51     .05       0
Bank Sta=265.35,284.11
XS Rating Curve= 0 ,0
Exp/Cntr=0.3,0.1

Type RM Length L Ch R = 1 ,4565    ,376.85,375.13,296.55
XS GIS Cut Line= 3
  2393632.968854621423.6042556612393917.20843735621157.895922333
2393979.01052068620966.333422318
#Sta/Elev= 30
       0   75.99    2.77   75.77    9.72   74.43   15.75   73.81   81.91   65.51
   98.73   64.18  134.53   60.81  142.11   59.63  157.32   59.15  171.19   58.53
  182.76   57.63  189.98   56.82  196.24   56.12  197.35   53.45   198.2   51.13
  206.58    56.2  206.99   56.19  217.25   56.04  259.83   59.37  277.04   59.76
  290.59   61.64  356.69   64.67  362.85   65.31  379.48   65.76  389.09   65.33
  490.77   66.03  494.65   66.39  528.04   71.49  568.96   74.62  590.38   77.14
#Mann= 3 ,-1 , 0
       0     .09       0  189.98     .05       0  206.99     .09       0
Bank Sta=189.98,206.99
XS Rating Curve= 0 ,0
Exp/Cntr=0.3,0.1

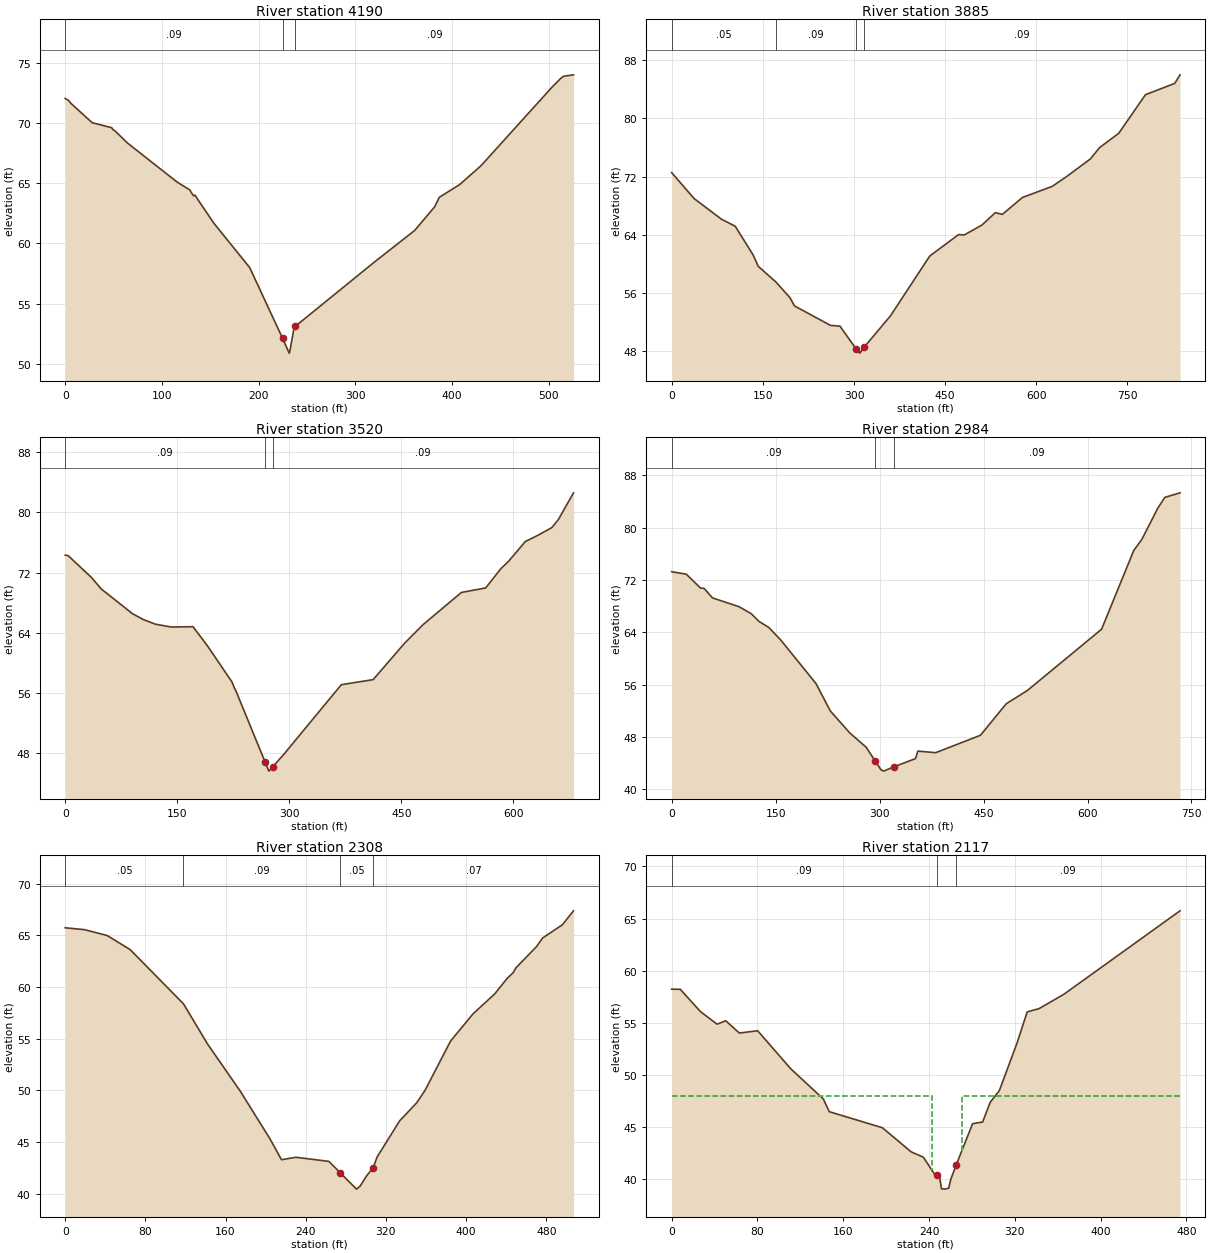
Type RM Length L Ch R = 1 ,4190    ,289.71,304.78,307.92
XS GIS Cut Line= 2
2394077.87510403621534.8230056462394238.53135401621034.312589005
#Sta/Elev= 29
       0   72.02    3.75   71.84    5.57   71.64    27.9   70.01   48.01    69.6
    49.6   69.42   51.46   69.34   64.19   68.34  115.72   65.09  128.64   64.45
  132.55   63.96   134.1   64.01  153.71   61.68  190.79      58  224.77   52.14
  231.59   50.91  232.13   50.99  236.76   53.05  238.07   53.14  319.76   58.46
  361.26   61.07  381.96   63.03  386.91   63.83  407.86   64.88  429.93   66.44
  503.57   72.97     512   73.65  515.19   73.86  525.66   73.98
#Mann= 3 ,-1 , 0
       0     .09       0  224.77     .05       0  238.07     .09       0
Bank Sta=224.77,238.07
XS Rating Curve= 0 ,0
Exp/Cntr=0.3,0.1

Type RM Length L Ch R = 1 ,3885    ,342.36,365.4,342.63
XS GIS Cut Line= 6
2394240.03135398621658.9167556612394305.13552065 621585.12508899
2394396.28135401621465.7709223182394491.76052068621307.354255661
2394613.29177065621148.9271723182394728.31260401620981.833422318
#Sta/Elev= 30
       0   72.55   36.89   68.99   82.06   66.14  104.62   65.18  134.32   61.19
  142.42   59.67  171.81   57.49   194.7   55.35  202.16   54.22  261.44   51.54
  276.86   51.45  303.22   48.34   309.7   47.73  316.69   48.54  360.16   52.87
  424.58   61.07  472.04   64.03  481.43   63.98  510.57   65.34  532.45   67.04
  544.14   66.81  577.38   69.14  626.44   70.67  649.87   72.01  688.96   74.43
  704.11   75.99  735.67   77.96  779.65   83.27   827.8   84.82  836.47      86
#Mann= 4 ,-1 , 0
       0     .05       0  171.81     .09       0  303.22     .05       0
  316.69     .09       0
Bank Sta=303.22,316.69
XS Rating Curve= 0 ,0
Exp/Cntr=0.3,0.1

Type RM Length L Ch R = 1 ,3520    ,550.88,535.4,500.59
XS GIS Cut Line= 2
2394578.39593734621812.8959223182394942.96885398 621238.21883899
#Sta/Elev= 30
       0   74.33     3.7   74.29   35.14   71.37    48.1   69.86   90.04   66.56
   104.4   65.79  120.94   65.16  141.88   64.79  171.12   64.83  190.03   62.35
  223.33   57.48   226.3   56.75  228.24   56.38  267.39   46.92  272.64   45.65
  277.87   46.23  292.58   47.87  369.67   57.13  412.27    57.8  454.58   62.66
  479.19   65.11  530.45   69.38  562.95   69.98  583.33   72.54  593.71   73.53
  616.01   76.14  633.11   76.98   651.6      78  660.28   79.06  680.56   82.61
#Mann= 3 ,-1 , 0
       0     .09       0  267.39     .05       0  277.87     .09       0
Bank Sta=267.39,277.87
XS Rating Curve= 0 ,0
Exp/Cntr=0.3,0.1

Type RM Length L Ch R = 1 ,2984    ,529.61,676.71,695.36
XS GIS Cut Line= 6
  2395118.937604  622103.7917557 2395162.3334373  622010.4792557
 2395190.5521873  621821.6771723  2395197.062604  621674.1042557
  2395212.250104   621609.000089 2395322.9271873   621413.687589
#Sta/Elev= 30
       0   73.24   21.03   72.87   41.73   70.74   46.88   70.69   58.95   69.24
   97.41   67.89  114.92   66.82  125.73   65.67  140.05   64.73   157.2   62.83
  208.19   56.16  228.88   51.97  256.93   48.61  280.56   46.43  293.87   44.28
  301.83      43  305.85   42.77  321.28   43.46  351.77   44.68  355.17   45.83
  380.96   45.59  445.53   48.25  482.77   53.07  513.18   55.09  620.26   64.45
  666.68   76.48  678.37   78.18  701.46   82.97  711.47    84.6  733.42    85.3
#Mann= 3 , 0 , 0
       0     .09       0  293.87     .05       0  321.28     .09       0
Bank Sta=293.87,321.28
XS Rating Curve= 0 ,0
Exp/Cntr=0.3,0.1

Type RM Length L Ch R = 1 ,2308    ,210.27,190.32,149.27
XS GIS Cut Line= 5
 2395320.7605207  622147.1980057 2395424.9271873  622149.3646723
 2395550.7917707  622147.1980057 2395652.7917707   622121.156339
 2395806.8230207  622044.8959223
#Sta/Elev= 30
       0   65.72   19.27   65.54   41.98   64.97   64.81   63.61  118.03   58.37
  142.15   54.47  174.67   49.93  204.46    45.3  215.83    43.3  230.19   43.54
  263.11   43.14  274.46   42.04  290.64   40.46  294.32   40.75  300.46   41.71
  307.34   42.53  311.13   43.55  333.65   47.05  350.67    48.8  358.96   49.99
  384.52   54.77  406.82   57.39  428.57   59.33  440.65   60.79  447.09    61.4
  449.77   61.85  470.34   63.91   476.3   64.73  495.94      66  507.22   67.36
#Mann= 4 ,-1 , 0
       0     .05       0  118.03     .09       0  274.46     .05       0
  307.34     .07       0
Bank Sta=274.46,307.34
XS Rating Curve= 0 ,0
Exp/Cntr=0.5,0.3

Type RM Length L Ch R = 1 ,2117    ,43.39,56.6,48.6
XS GIS Cut Line= 6
  2395510.812604   622396.250089  2395721.718854  622300.2605057
 2395736.1667707  622262.4896723  2395738.625104   622229.281339
  2395777.156354  622103.5521723  2395800.812604   622075.156339
#Sta/Elev= 30
       0   58.22    8.02   58.21   26.73   56.08   42.38   54.86   50.41   55.19
   63.12   54.01    80.2   54.23  111.17   50.57  141.46   47.68  147.04   46.46
  196.58   44.92  223.44    42.6  234.72    42.1  245.35   40.43  247.34   40.38
  249.88    40.2  251.69   39.06  254.87   39.03   258.4   39.13  260.26   39.95
   265.4   41.36  280.68   45.31  290.04   45.47  297.01   47.35  305.64   48.49
  322.17   53.07   331.6   56.04  342.62   56.35  365.92   57.74   474.1   65.74
#Mann= 3 ,-1 , 0
       0     .09       0  247.34     .05       0   265.4     .09       0
#XS Ineff= 2 ,-1
       0  242.34      48   270.4     500      48
Permanent Ineff=
       F       F
Bank Sta=247.34,265.4
XS Rating Curve= 0 ,0
Exp/Cntr=0.5,0.3

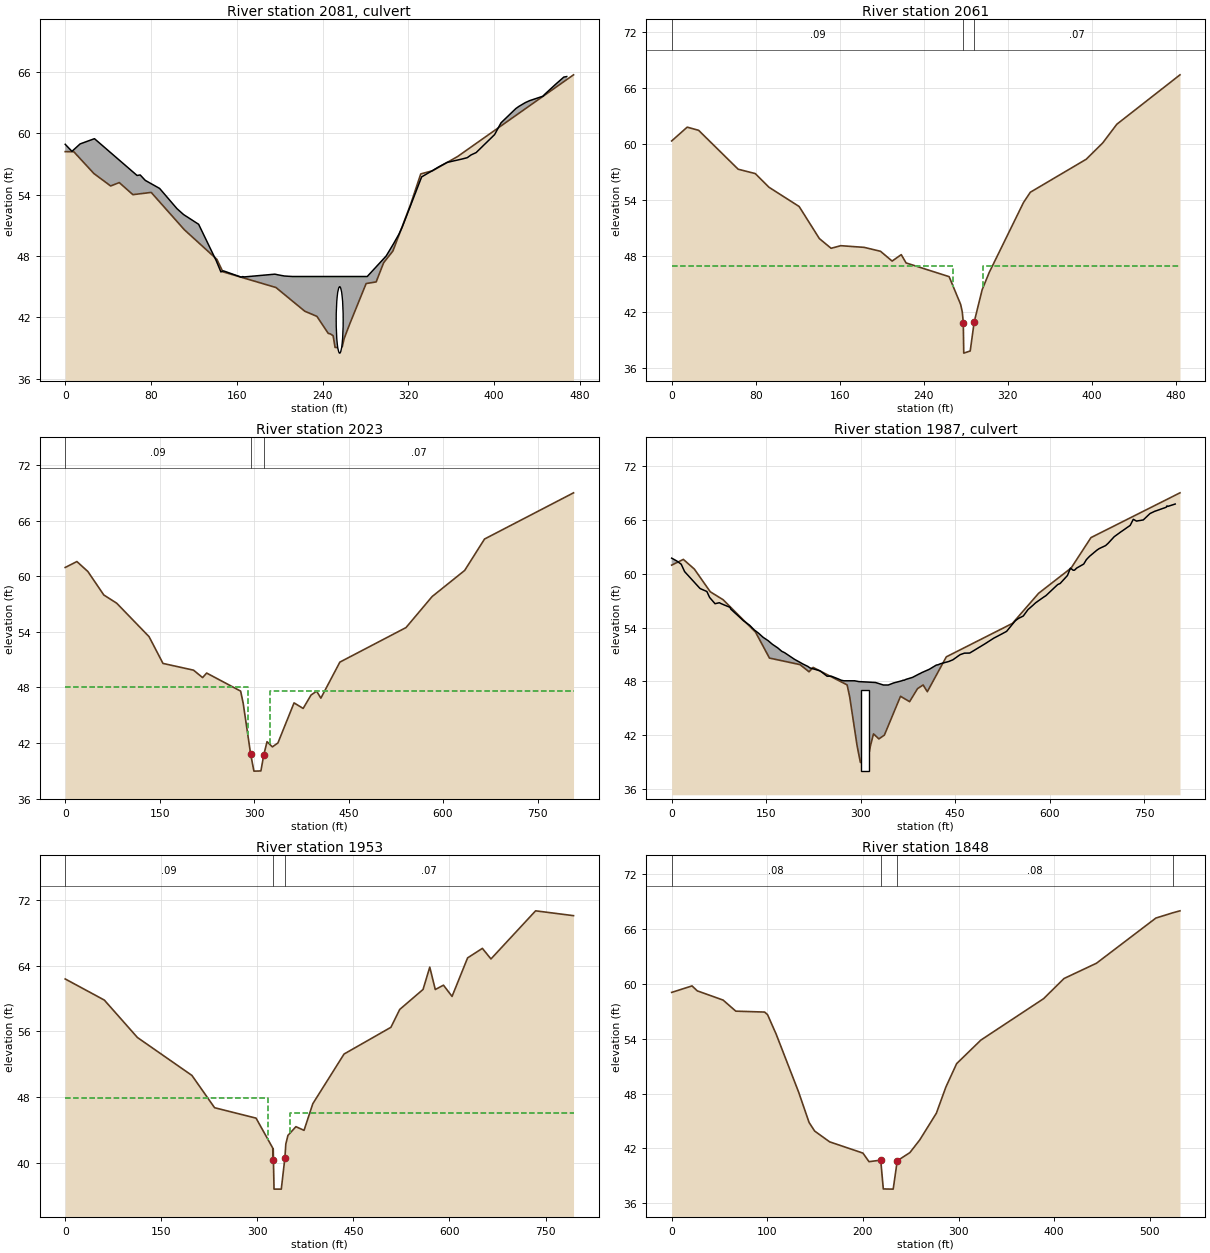
Type RM Length L Ch R = 2 ,2081    ,,,
BEGIN DESCRIPTION:
St. Barnabas Rd
END DESCRIPTION:
Bridge Culvert--1,0,-1,-1, 0
Deck Dist Width WeirC Skew NumUp NumDn MinLoCord MaxHiCord MaxSubmerge Is_Ogee
26,14,2.2,0, 55, 55, , , 0.95, 0, 1,1,,
       0    6.29   13.92   27.29   67.01   69.94   74.66   88.06  104.25  110.44
  124.46  140.84   145.2  147.63  164.05  165.48  167.12   195.6  198.15  204.31
   211.6  222.11  224.86  235.24  249.89  257.79  261.12  269.93  273.68  277.38
  281.69  299.36  306.35  311.35  314.46  332.42  337.67  343.08   348.2  356.23
  369.79  374.98  378.53  383.29  400.48  406.45   420.3  423.13  429.11  433.08
  445.63   446.9  457.13  465.03  467.78
   58.94   58.25   58.98   59.49   55.89   55.94   55.41   54.62   52.64   52.06
   51.11   47.55   46.45   46.55   45.94   45.99   45.96   46.23   46.17   46.05
      46      46      46      46      46      46      46      46      46      46
      46   48.01   49.23   50.16   50.87   55.75   56.07    56.4   56.72   57.17
   57.49   57.63    57.9   58.13   59.89   61.04   62.44   62.65   63.02   63.21
   63.65    63.8   64.79   65.52   65.57
                                                                                
                                                                                
                                                                                
                                                                                
                                                                                
                                        
       0    6.29   13.92   27.29   67.01   69.94   74.66   88.06  104.25  110.44
  124.46  140.84   145.2  147.63  164.05  165.48  167.12   195.6  198.15  204.31
   211.6  222.11  224.86  235.24  249.89  257.79  261.12  269.93  273.68  277.38
  281.69  299.36  306.35  311.35  314.46  332.42  337.67  343.08   348.2  356.23
  369.79  374.98  378.53  383.29  400.48  406.45   420.3  423.13  429.11  433.08
  445.63   446.9  457.13  465.03  467.78
   58.94   58.25   58.98   59.49   55.89   55.94   55.41   54.62   52.64   52.06
   51.11   47.55   46.45   46.55   45.94   45.99   45.96   46.23   46.17   46.05
      46      46      46      46      46      46      46      46      46      46
      46   48.01   49.23   50.16   50.87   55.75   56.07    56.4   56.72   57.17
   57.49   57.63    57.9   58.13   59.89   61.04   62.44   62.65   63.02   63.21
   63.65    63.8   64.79   65.52   65.57
                                                                                
                                                                                
                                                                                
                                                                                
                                                                                
                                        
BR Coef=-1 , 1 , 0 ,1.25, 0 ,,,0.8,0,2,0,
WSPro=,,,, 1 ,,,, 0 ,,,, 0 ,,,,-1 ,-1 ,-1 , 0 , 0 , 0 , 0 , 0
Culvert=1,6.5,,35,0.024,0.9,1,1,1,38.5,256,38.4,282,Culvert #1  , 0 ,15
Culvert Bottom n=0.024
BC Design=,, 0 ,, 0 ,,,,,,
BC Use User HTab Curves=0
BC User HTab FreeFlow(D)= 0

Type RM Length L Ch R = 1 ,2061    ,8.32,37.61,82.11
XS GIS Cut Line= 4
 2395541.2292707   622423.968839 2395783.2396873   622317.843839
  2395778.500104  622279.9792557 2395816.3542707  622102.1980057
#Sta/Elev= 30
       0   60.36   14.79   61.84   25.66    61.5   63.33   57.33   79.64   56.86
   92.64    55.4  121.42   53.33  140.69   49.89  151.86   48.85  161.06   49.13
  183.36   48.95  198.92   48.53  209.98   47.48  218.67   48.17  223.28   47.28
  264.26   45.81  275.26   42.83  276.81   42.03  277.77   40.87   278.2   37.61
  284.37   37.84  288.14   40.95  295.72    44.4  302.42   46.25  335.12   53.76
  341.62   54.86  394.88    58.4  410.59   60.15  423.99   62.15  484.18   67.45
#Mann= 3 ,-1 , 0
       0     .09       0  277.77     .05       0  288.14     .07       0
#XS Ineff= 2 , 0
       0  268.21      47  296.95       0      47
Permanent Ineff=
       F       F
Bank Sta=277.77,288.14
XS Rating Curve= 0 ,0
Exp/Cntr=0.5,0.3

Type RM Length L Ch R = 1 ,2023    ,67.37,69.89,75.07
XS GIS Cut Line= 3
 2395543.4167707  622431.7605057  2395944.250104   622255.437589
 2396282.6667707   622107.593839
#Sta/Elev= 30
       0   60.96   18.55    61.6   36.04   60.52   61.31   57.99   81.81    57.1
  133.16   53.49  155.27    50.6  203.83   49.87  218.16   49.07  224.63   49.56
  278.58   47.61  282.61   46.31  294.45   40.82  299.68   38.97  310.76   38.99
   315.4   40.75  320.51   42.15  329.02   41.59  337.77   42.01  363.41   46.34
  377.84   45.74  390.42   47.19  399.28    47.6  405.98   46.85  436.15   50.74
  541.18   54.47  582.65   57.82  634.35   60.64  665.85   64.03   807.2   69.02
#Mann= 3 ,-1 , 0
       0     .09       0  294.45     .05       0   315.4     .07       0
#XS Ineff= 2 , 0
       0     290   48.07     325       0    47.6
Permanent Ineff=
       T       T
Bank Sta=294.45,315.4
XS Rating Curve= 0 ,0
Exp/Cntr=0.5,0.3

Type RM Length L Ch R = 2 ,1987    ,,,
BEGIN DESCRIPTION:
SE Fourth Street
END DESCRIPTION:
Bridge Culvert--1,0,-1,-1, 0
Deck Dist Width WeirC Skew NumUp NumDn MinLoCord MaxHiCord MaxSubmerge Is_Ogee
17,25,2.6,0, 103, 103, , , 0.95, 0, 1,1,,
       0       8   15.17   20.53   44.43    45.1   45.43    55.9   60.23   68.88
   75.64   78.83   84.54   92.55   94.01  109.28     114  123.78  131.15  138.04
  145.31  153.22  159.91  168.58  174.72  179.43  194.89  208.72  216.51  219.46
  235.03  236.36  246.77  253.63  264.82  269.26  273.42  290.48  297.11   323.7
  336.19  343.99  352.48  365.48  367.66  368.84  371.72  382.43  393.96   395.1
  396.12  409.08  420.19   423.2  426.77  440.07  446.59  458.02  464.84  473.06
  476.56  485.02  497.75  511.21  517.45  523.14  531.89  541.66   545.9   550.4
  558.32  565.74  573.73  577.91  590.77  594.36  608.96  612.93  616.95  628.51
  633.22  637.59  639.72  643.05  654.31   658.6  663.83  675.07  678.78  689.07
  693.01  702.73  712.94  728.11  733.02  738.14  748.92  759.53  766.67   785.2
  786.47  787.51  799.57
   61.74   61.43   61.06   60.24    58.4   58.36   58.34   58.02   57.36   56.66
   56.77   56.66   56.49   56.26   56.05   55.07   54.76   54.26   53.74   53.37
   52.91   52.54   52.14   51.73   51.36    51.2   50.47   49.93   49.66   49.51
   49.19   49.14   48.58   48.58   48.27   48.13   48.07   48.07   47.98   47.88
    47.6    47.6   47.83   48.07   48.14   48.12   48.22   48.45   48.87   48.89
   48.95   49.35   49.82   49.86   49.97   50.22   50.41   50.98   51.15   51.16
    51.3   51.66    52.2   52.81   53.04   53.25   53.58   54.42   54.77   55.01
   55.29      56   56.49   56.76    57.4   57.56   58.53   58.79   58.92   59.81
   60.63   60.39    60.4   60.63   61.08   61.58   61.96   62.62    62.8   63.14
   63.39   64.13   64.65   65.39   66.07   65.87      66   66.71   66.95   67.41
   67.56    67.5   67.77
                                                                                
                                                                                
                                                                                
                                                                                
                                                                                
                                                                                
                                                                                
                                                                                
                                                                                
                                                                                
                        
       0       8   15.17   20.53   44.43    45.1   45.43    55.9   60.23   68.88
   75.64   78.83   84.54   92.55   94.01  109.28     114  123.78  131.15  138.04
  145.31  153.22  159.91  168.58  174.72  179.43  194.89  208.72  216.51  219.46
  235.03  236.36  246.77  253.63  264.82  269.26  273.42  290.48  297.11   323.7
  336.19  343.99  352.48  365.48  367.66  368.84  371.72  382.43  393.96   395.1
  396.12  409.08  420.19   423.2  426.77  440.07  446.59  458.02  464.84  473.06
  476.56  485.02  497.75  511.21  517.45  523.14  531.89  541.66   545.9   550.4
  558.32  565.74  573.73  577.91  590.77  594.36  608.96  612.93  616.95  628.51
  633.22  637.59  639.72  643.05  654.31   658.6  663.83  675.07  678.78  689.07
  693.01  702.73  712.94  728.11  733.02  738.14  748.92  759.53  766.67   785.2
  786.47  787.51  799.57
   61.74   61.43   61.06   60.24    58.4   58.36   58.34   58.02   57.36   56.66
   56.77   56.66   56.49   56.26   56.05   55.07   54.76   54.26   53.74   53.37
   52.91   52.54   52.14   51.73   51.36    51.2   50.47   49.93   49.66   49.51
   49.19   49.14   48.58   48.58   48.27   48.13   48.07   48.07   47.98   47.88
    47.6    47.6   47.83   48.07   48.14   48.12   48.22   48.45   48.87   48.89
   48.95   49.35   49.82   49.86   49.97   50.22   50.41   50.98   51.15   51.16
    51.3   51.66    52.2   52.81   53.04   53.25   53.58   54.42   54.77   55.01
   55.29      56   56.49   56.76    57.4   57.56   58.53   58.79   58.92   59.81
   60.63   60.39    60.4   60.63   61.08   61.58   61.96   62.62    62.8   63.14
   63.39   64.13   64.65   65.39   66.07   65.87      66   66.71   66.95   67.41
   67.56    67.5   67.77
                                                                                
                                                                                
                                                                                
                                                                                
                                                                                
                                                                                
                                                                                
                                                                                
                                                                                
                                                                                
                        
BR Coef=-1 , 1 , 0 ,1.25, 0 ,,,0.8,0,2,0,
WSPro=,,,, 1 ,,,, 0 ,,,, 0 ,,,,-1 ,-1 ,-1 , 0 , 0 , 0 , 0 , 0
Culvert=2,9,14,35,0.011,0.4,1,8,1,38,307,37.9,334,Culvert #1  , 0 ,12
Culvert Bottom n=0.011
BC Design=,, 0 ,, 0 ,,,,,,
BC Use User HTab Curves=0
BC User HTab FreeFlow(D)= 0

Type RM Length L Ch R = 1 ,1953    ,114.5,105.78,89.73
XS GIS Cut Line= 2
 2395568.6146873  622487.6146723 2396293.6146873  622164.5417557
#Sta/Elev= 30
       0   62.41   61.13   59.83  112.72   55.27  197.87   50.64  233.27    46.7
     298   45.43     324   41.79  324.75   40.29  324.77   41.69  326.07   36.77
  337.42   36.77  343.02   40.57  344.48   42.27  347.77   43.32  360.25   44.39
  372.93   43.94  386.62   47.19  435.41   53.25  508.57   56.51  522.35   58.69
  558.78   61.13  569.24   63.85  577.88   61.12  590.65   61.65  604.05   60.28
  628.33   64.98  651.39   66.14  664.82   64.85  734.51   70.72  793.73   70.13
#Mann= 3 ,-1 , 0
       0     .09       0  324.75     .05       0  343.02     .07       0
#XS Ineff= 2 , 0
       0     317    47.9     351       0      46
Permanent Ineff=
       F       F
Bank Sta=324.75,343.02
XS Rating Curve= 0 ,0
Exp/Cntr=0.5,0.3

Type RM Length L Ch R = 1 ,1848    ,320.35,337.47,323.26
XS GIS Cut Line= 6
  2395731.218854  622533.8334223  2395844.500104  622486.9584223
  2395914.812604  622441.3855057  2395957.781354  622410.1355057
 2396089.2917707  622338.5209223  2396203.875104  622295.5521723
#Sta/Elev= 30
       0   59.06    21.3   59.77   26.77   59.23   53.81   58.22   67.05   57.01
   97.26   56.91  100.32   56.62  109.34   54.48  132.82   48.15  143.71   44.84
  149.55    43.9  165.21   42.72  200.02   41.49  206.39   40.55  218.64   40.72
  221.35   37.57  231.69   37.55  235.93   40.65   249.1   41.54  259.52   42.94
  276.83   45.85  286.74    48.7  298.03   51.27  323.44   53.85  388.93   58.37
  410.37   60.58   444.3   62.25  506.43   67.19  524.26   67.77  531.65   67.98
#Mann= 4 ,-1 , 0
       0     .08       0  218.64     .05       0  235.93     .08       0
  524.26     .09       0
Bank Sta=218.64,235.93
XS Rating Curve= 0 ,0
Exp/Cntr=0.3,0.1

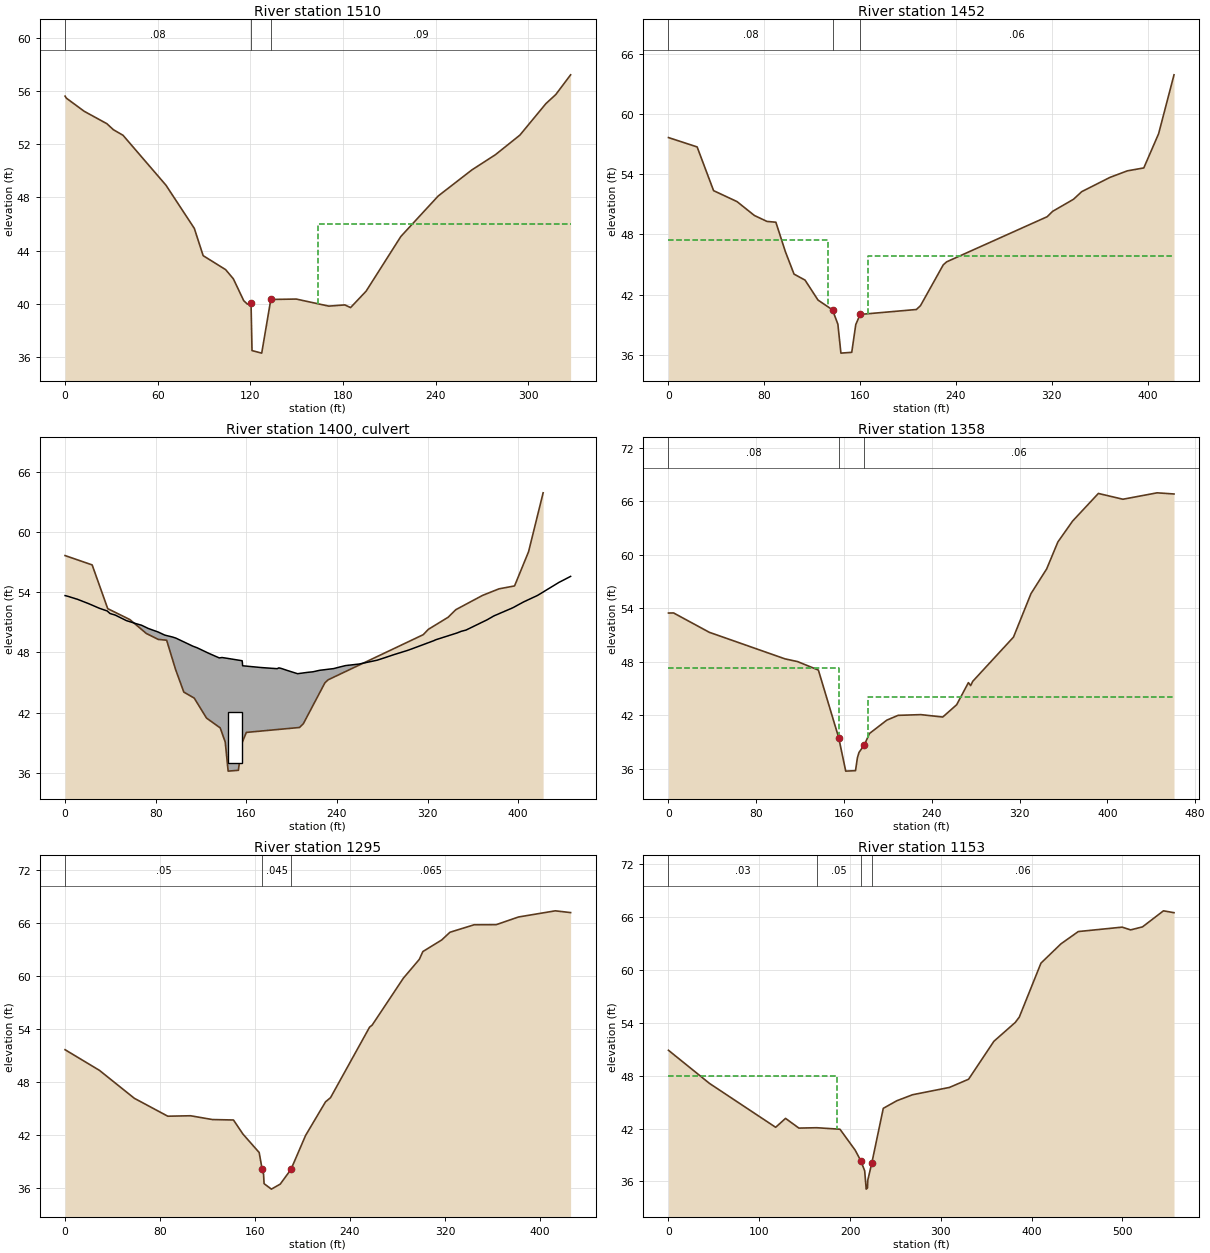
Type RM Length L Ch R = 1 ,1510    ,74.47,57.6,48.61
XS GIS Cut Line= 5
 2396008.0521873  622729.6042557  2396081.968854  622701.4584223
 2396134.7605207  622678.5730057  2396184.031354  622652.1771723
  2396263.218854  622543.0730057
#Sta/Elev= 30
       0    55.6     .82   55.45   12.41   54.46   27.08   53.53   31.27   53.08
   37.53   52.66   65.34   48.91   83.69   45.67   89.41   43.62  103.97   42.57
  108.97   41.88  115.68   40.24  118.05   39.98  120.42   40.03  121.05   36.49
  127.33    36.3  133.22   40.33  149.71   40.36  170.78   39.83  181.19   39.92
  184.87   39.72  194.91   40.95  217.42   45.06   241.6    48.1  263.42   50.06
  278.64    51.2  294.48   52.67  311.36   55.04  317.75   55.72  327.34    57.2
#Mann= 3 , 0 , 0
       0     .08       0  120.42     .05       0  133.22     .09       0
#XS Ineff= 2 , 0
       0                     164       0      46
Permanent Ineff=
       F       F
Bank Sta=120.42,133.22
XS Rating Curve= 0 ,0
Exp/Cntr=0.5,0.3

Type RM Length L Ch R = 1 ,1452    ,83.29,94.46,105.18
XS GIS Cut Line= 6
 2396043.5417707   622799.062589  2396085.500104   622782.843839
  2396136.968854  622750.3959223  2396253.343854   622650.250089
 2396310.9584373  622606.6146723  2396368.031354   622536.687589
#Sta/Elev= 30
       0   57.64   23.92   56.71   37.67   52.36   57.26   51.27   71.74   49.89
   82.23    49.3   89.67   49.22   97.59    46.3  104.84   44.06  114.05   43.46
  124.84   41.48  136.97    40.5  141.44   39.08  143.98    36.2  153.02   36.28
  156.38   39.04  160.05   40.05  206.99   40.54  210.41   40.92  229.42   44.98
  232.25   45.28  316.21   49.77  320.72    50.3  338.14    51.5  345.03   52.26
  368.62   53.68  383.11   54.33  396.85   54.62  409.22   58.02  422.08   63.88
#Mann= 3 ,-1 , 0
       0     .08       0  136.97     .05       0  160.05     .06       0
#XS Ineff= 2 , 0
       0   133.5   47.46   166.5       0   45.89
Permanent Ineff=
       T       T
Bank Sta=136.97,160.05
XS Rating Curve= 0 ,0
Exp/Cntr=0.5,0.3

Type RM Length L Ch R = 2 ,1400    ,,,
BEGIN DESCRIPTION:
SE Third Street
END DESCRIPTION:
Bridge Culvert--1,0,-1,-1, 0
Deck Dist Width WeirC Skew NumUp NumDn MinLoCord MaxHiCord MaxSubmerge Is_Ogee
40,26,3,0, 61, 61, , , 0.95, 0, 0.5,0.5,,
       0    2.37   10.96   20.97   30.45   37.19   39.35   39.59    44.3   54.13
   62.62   67.56   73.43   82.33    87.8   89.03   94.84   97.84  112.99  116.57
  126.85  136.14  138.59  142.64  156.32  156.55  156.74  173.44  187.24  188.74
  190.74   195.2  198.53   205.3  213.78  218.81  224.81  237.21  242.63  247.79
  259.52  275.42     282  290.17  301.64  304.71  323.79  325.41  327.38   346.3
  349.88     354   372.6  378.65  394.96     396  404.85  417.23  436.17  439.33
  446.34
   53.66   53.59   53.29   52.85   52.39   52.13   51.91   51.88   51.72   51.17
   50.87   50.71   50.39   50.03   49.74    49.7   49.54   49.43   48.62   48.47
   47.92   47.46    47.5   47.43   47.18   47.01   46.68    46.5   46.39   46.47
   46.42   46.25   46.13   45.89   46.02   46.08   46.23    46.4   46.56    46.7
   46.85   47.23   47.47   47.78   48.18    48.3    49.1   49.17   49.27   49.95
   50.11   50.23   51.25   51.64   52.43   52.49   53.03   53.68   54.98   55.16
   55.57
                                                                                
                                                                                
                                                                                
                                                                                
                                                                                
                                                                                
        
       0    2.37   10.96   20.97   30.45   37.19   39.35   39.59    44.3   54.13
   62.62   67.56   73.43   82.33    87.8   89.03   94.84   97.84  112.99  116.57
  126.85  136.14  138.59  142.64  156.32  156.55  156.74  173.44  187.24  188.74
  190.74   195.2  198.53   205.3  213.78  218.81  224.81  237.21  242.63  247.79
  259.52  275.42     282  290.17  301.64  304.71  323.79  325.41  327.38   346.3
  349.88     354   372.6  378.65  394.96     396  404.85  417.23  436.17  439.33
  446.34
   53.66   53.59   53.29   52.85   52.39   52.13   51.91   51.88   51.72   51.17
   50.87   50.71   50.39   50.03   49.74    49.7   49.54   49.43   48.62   48.47
   47.92   47.46    47.5   47.43   47.18   47.01   46.68    46.5   46.39   46.47
   46.42   46.25   46.13   45.89   46.02   46.08   46.23    46.4   46.56    46.7
   46.85   47.23   47.47   47.78   48.18    48.3    49.1   49.17   49.27   49.95
   50.11   50.23   51.25   51.64   52.43   52.49   53.03   53.68   54.98   55.16
   55.57
                                                                                
                                                                                
                                                                                
                                                                                
                                                                                
                                                                                
        
BR Coef=-1 , 1 , 0 ,1.25, 0 ,,,0.8,0,2,0,
WSPro=,,,, 1 ,,,, 0 ,,,, 0 ,,,,-1 ,-1 ,-1 , 0 , 0 , 0 , 0 , 0
Culvert=2,5,13,30,0.011,0.4,1,8,3,37.04,150,35.9,165,Culvert #1  , 0 ,38
Culvert Bottom n=0.011
BC Design=,, 0 ,, 0 ,,,,,,
BC Use User HTab Curves=0
BC User HTab FreeFlow(D)= 0

Type RM Length L Ch R = 1 ,1358    ,64.97,63.11,57.15
XS GIS Cut Line= 6
 2396060.3334373   622856.687589 2396152.0834373   622822.000089
 2396219.2084373   622800.187589 2396267.8855207   622782.843839
 2396386.4896873  622701.1667557  2396459.781354   622638.500089
#Sta/Elev= 30
       0   53.46    4.67   53.47    37.2    51.3  106.16   48.32  117.71   48.01
  136.64   47.06  155.15   39.48  161.57   35.72  170.47   35.77  172.23   37.23
  173.67   37.82  178.55   38.67   183.2   39.94  198.99   41.44  209.31   41.98
  230.08   42.06     250   41.79  262.67   43.17  273.36   45.65  275.43   45.32
  277.36    45.8  314.48   50.76  330.42   55.64  344.71   58.41  354.91   61.43
  368.34   63.78  391.83   66.88  414.24   66.23  445.41   66.95  460.78   66.82
#Mann= 3 ,-1 , 0
       0     .08       0  155.15     .05       0  178.55     .06       0
#XS Ineff= 2 , 0
       0     155   47.32   181.5       0      44
Permanent Ineff=
       F       F
Bank Sta=155.15,178.55
XS Rating Curve= 0 ,0
Exp/Cntr=0.5,0.3

Type RM Length L Ch R = 1 ,1295    ,143.41,141.64,142.23
XS GIS Cut Line= 5
 2396080.2084373  622898.5417557 2396120.6771873  622898.5417557
  2396166.437604  622893.2605057 2396372.3230207  622792.9584223
 2396463.8230207  622731.3646723
#Sta/Elev= 30
       0   51.63   28.95   49.29   58.35   46.12   86.53   44.09  105.72   44.14
   124.1   43.71  141.86   43.66  149.86   42.06  163.52   39.97  166.04   38.06
  167.19   37.52  167.64   36.44   173.8   35.82  181.25   36.39  190.27   38.05
  202.61   41.91  219.41   45.72  223.61   46.19  256.52   54.19  258.68   54.42
  284.96   59.74  298.43   61.88  301.38   62.76  317.31   64.08  324.23   64.95
  344.62    65.8   363.2   65.81  381.92   66.68  412.94   67.38  425.85   67.18
#Mann= 3 , 0 , 0
       0     .05       0  166.04    .045       0  190.27    .065       0
Bank Sta=166.04,190.27
XS Rating Curve= 0 ,0
Exp/Cntr=0.3,0.1

Type RM Length L Ch R = 1 ,1153    ,74.11,78.85,83.69
XS GIS Cut Line= 3
 2396083.5834373  623095.3334223 2396484.6042707   622883.687589
 2396572.4896873   622829.218839
#Sta/Elev= 30
       0   50.87   45.25   47.11  118.06   42.14  128.96   43.15  143.64   42.05
  163.38   42.09  188.92   41.92   205.7   39.54  211.77   38.36  216.12   37.21
  217.81   35.13  219.19   35.26  219.55   36.15  224.02   38.11  236.61   44.29
  251.53   45.15  268.84   45.83   309.5   46.66  330.58   47.59  358.44   51.89
  381.93   54.02  386.46   54.64  410.29   60.75  432.24   62.93  451.39   64.33
  499.67   64.83  509.08   64.52  522.13   64.86  545.21   66.68  556.84   66.47
#Mann= 4 ,-1 , 0
       0     .03       0  163.38     .05       0  211.77    .045       0
  224.02     .06       0
#XS Ineff= 2 , 0
       0     186      48               0
Permanent Ineff=
       F       F
Bank Sta=211.77,224.02
XS Rating Curve= 0 ,0
Exp/Cntr=0.5,0.3