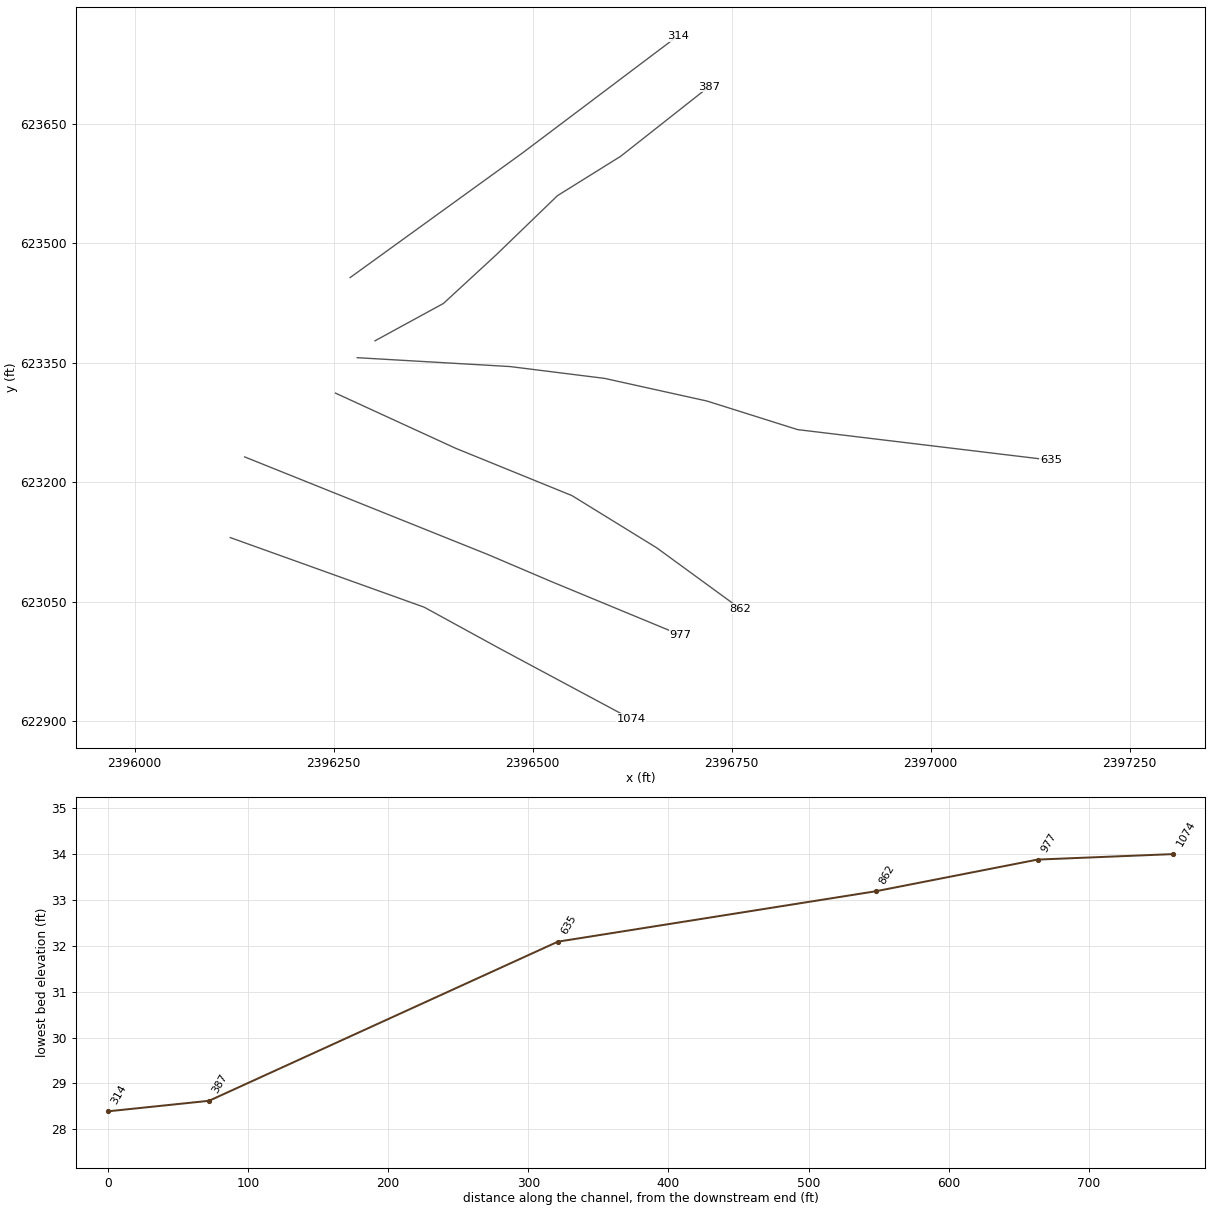
HEC-RAS study LDS_Contentnea_Crk_Trib8.prj: LDS_Contentnea_Crk_Trib8

--- LDS_Contentnea_Crk_Trib8.g01 (geometry) --- (continued)

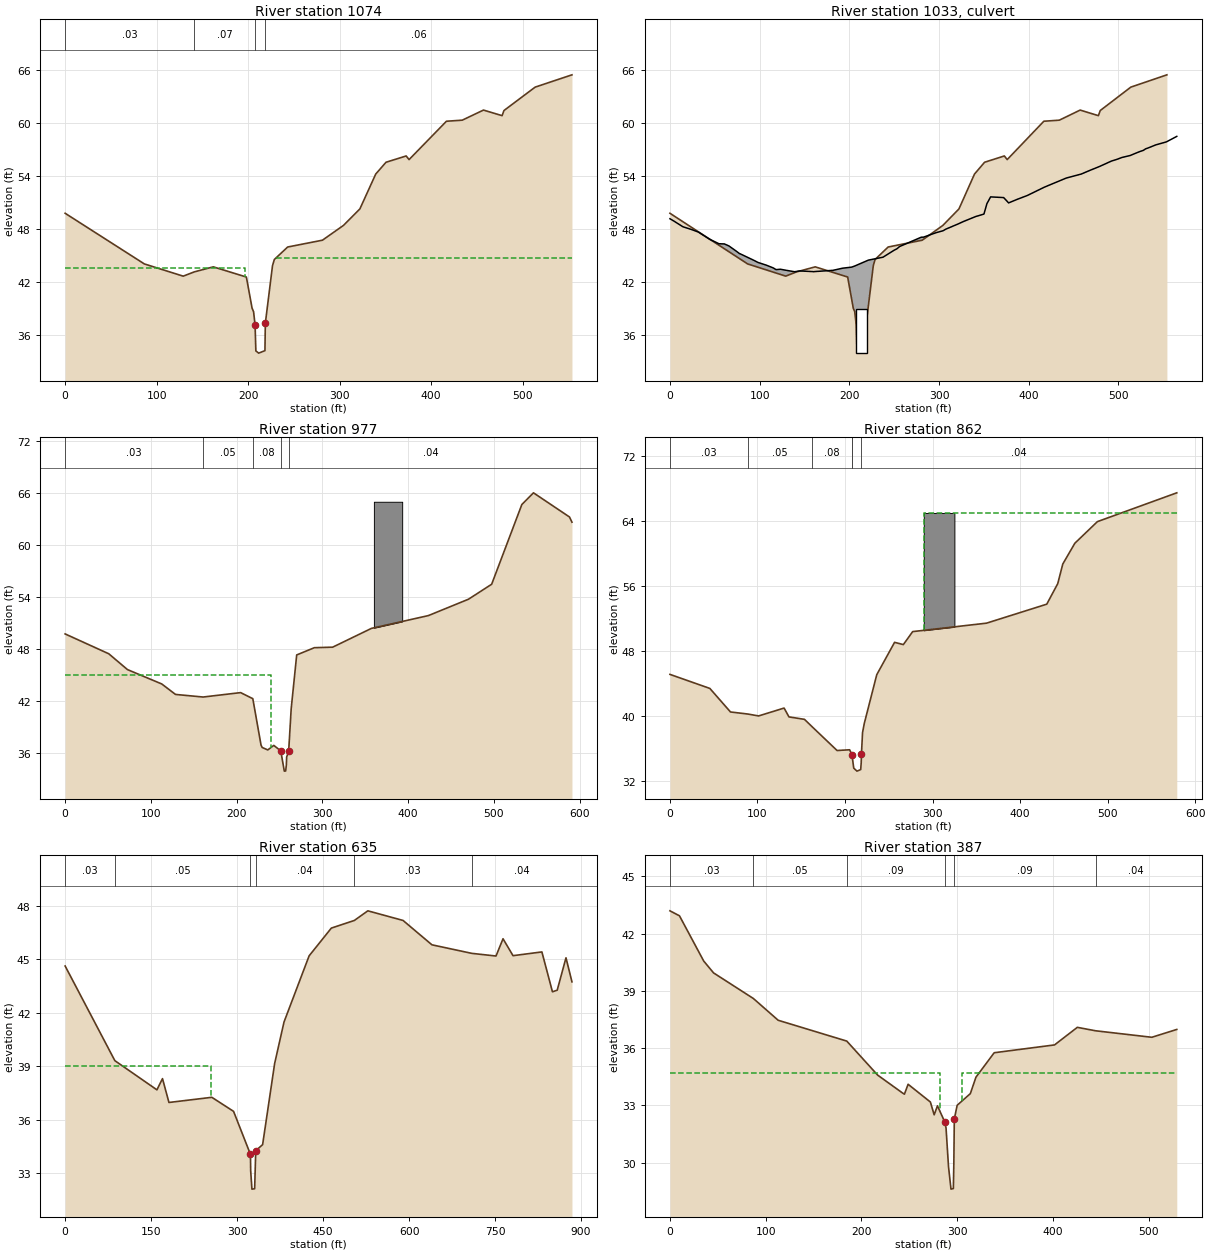
Type RM Length L Ch R = 1 ,1074    ,94.96,96.92,94.87
XS GIS Cut Line= 4
 2396120.0521873  623130.3959223  2396363.718854  623042.9271723
 2396458.8230207  622990.8646723  2396623.343854  622902.6980057
#Sta/Elev= 30
       0   49.79    86.6   44.07  129.06   42.69   141.1   43.17  161.96   43.74
   198.1   42.59  204.35   39.07  205.97   38.68   207.6    37.2  208.47   34.25
  211.54      34   218.4   34.28  218.83   37.38  226.67   43.87  228.65   44.57
  243.24   45.98  281.25   46.75  304.23   48.42  322.16   50.28  339.51   54.22
  350.74   55.55  372.76   56.26  375.94   55.85  416.78   60.18  434.04    60.3
  457.26   61.44   477.6   60.81  479.67   61.39  513.72   64.03  553.97   65.42
#Mann= 4 ,-1 , 0
       0     .03       0   141.1     .07       0   207.6    .045       0
  218.83     .06       0
#XS Ineff= 2 , 0
       0     197   43.64     230       0   44.73
Permanent Ineff=
       T       T
Bank Sta=207.6,218.83
XS Rating Curve= 0 ,0
Exp/Cntr=0.5,0.3

Type RM Length L Ch R = 2 ,1033    ,,,
BEGIN DESCRIPTION:
SE Second Street
END DESCRIPTION:
Bridge Culvert--1,0,-1,-1, 0
Deck Dist Width WeirC Skew NumUp NumDn MinLoCord MaxHiCord MaxSubmerge Is_Ogee
15,35,2.6,0, 71, 71, , , 0.95, 0, 1,1,,
       0    4.07   14.37   24.76    29.5   31.85      35   44.59   54.61   60.68
   65.76   73.84   77.58   78.38    94.1    98.1  107.19  114.95  118.28  123.25
  129.61  139.01  144.83  158.06  159.68  160.19  161.63   181.8  192.48  202.48
  205.58  221.17  237.49  249.58  253.19   255.9  280.16   282.5  296.76  304.51
  307.59  321.12   327.4   340.8     350  353.34  357.46     372  377.51   386.8
  398.43  417.01  419.57  420.73  440.66  441.96  458.54   468.8  478.78  492.04
  498.34  503.88  512.99  523.53  527.68  530.35  532.96  541.56   553.4  557.88
  564.97
   49.17   48.93   48.27   47.93   47.75   47.66   47.45   46.84   46.35   46.33
    46.1   45.52   45.23   45.21   44.45   44.24   43.94   43.63   43.43   43.47
   43.35   43.19   43.28   43.21    43.2   43.19   43.21   43.35   43.59   43.71
   43.82    44.5   44.83    45.6   45.79   46.03   47.09   47.09    47.6   47.82
      48   48.58   48.87   49.42    49.7   50.88   51.64   51.56   50.96   51.35
    51.8   52.72   52.83   52.88   53.72   53.77   54.22   54.66   55.07   55.68
   55.88   56.09   56.31   56.75   56.89   57.07   57.16   57.51   57.85   58.09
   58.47
                                                                                
                                                                                
                                                                                
                                                                                
                                                                                
                                                                                
                                                                                
        
       0    4.07   14.37   24.76    29.5   31.85      35   44.59   54.61   60.68
   65.76   73.84   77.58   78.38    94.1    98.1  107.19  114.95  118.28  123.25
  129.61  139.01  144.83  158.06  159.68  160.19  161.63   181.8  192.48  202.48
  205.58  221.17  237.49  249.58  253.19   255.9  280.16   282.5  296.76  304.51
  307.59  321.12   327.4   340.8     350  353.34  357.46     372  377.51   386.8
  398.43  417.01  419.57  420.73  440.66  441.96  458.54   468.8  478.78  492.04
  498.34  503.88  512.99  523.53  527.68  530.35  532.96  541.56   553.4  557.88
  564.97
   49.17   48.93   48.27   47.93   47.75   47.66   47.45   46.84   46.35   46.33
    46.1   45.52   45.23   45.21   44.45   44.24   43.94   43.63   43.43   43.47
   43.35   43.19   43.28   43.21    43.2   43.19   43.21   43.35   43.59   43.71
   43.82    44.5   44.83    45.6   45.79   46.03   47.09   47.09    47.6   47.82
      48   48.58   48.87   49.42    49.7   50.88   51.64   51.56   50.96   51.35
    51.8   52.72   52.83   52.88   53.72   53.77   54.22   54.66   55.07   55.68
   55.88   56.09   56.31   56.75   56.89   57.07   57.16   57.51   57.85   58.09
   58.47
                                                                                
                                                                                
                                                                                
                                                                                
                                                                                
                                                                                
                                                                                
        
BR Coef=-1 , 1 , 0 ,1.25, 0 ,,,0.8,0,2,0,
WSPro=,,,, 1 ,,,, 0 ,,,, 0 ,,,,-1 ,-1 ,-1 , 0 , 0 , 0 , 0 , 0
Culvert=2,5,13,50,0.012,0.4,1,8,1,34,213.5,33.9,256,Culvert #1  , 0 ,7
Culvert Bottom n=0.012
BC Design=,, 0 ,, 0 ,,,,,,
BC Use User HTab Curves=0
BC User HTab FreeFlow(D)= 0

Type RM Length L Ch R = 1 ,977     ,111.91,115.27,121.26
XS GIS Cut Line= 4
 2396138.1042707   623231.750089  2396444.250104   623108.875089
 2396524.0834373  623074.8542557 2396685.1355207   623008.218839
#Sta/Elev= 30
       0   49.73   50.84   47.44   72.68   45.61  112.66   43.95  128.71   42.74
  160.92   42.44  204.62   42.95  218.83   42.25  228.43   36.89  229.78   36.61
   236.3   36.33  243.31   36.85  251.45   36.22  255.55   33.88  257.15    33.9
  257.94   34.58  258.31   35.51  260.64   36.17  263.57   41.07     270    47.3
  290.62   48.14  311.94    48.2  357.15   50.37  423.61   51.85  470.32   53.74
  497.34   55.47  532.53   64.68  546.09   66.03  588.06   63.24  590.96   62.64
#Mann= 5 ,-1 , 0
       0     .03       0  160.92     .05       0  218.83     .08       0
  251.45    .045       0  260.64     .04       0
#XS Ineff= 2 , 0
       0   239.5   44.95   272.5       0   47.38
Permanent Ineff=
       F       F
#Block Obstruct= 1 ,-1
     360     393      65
Bank Sta=251.45,260.64
XS Rating Curve= 0 ,0
Exp/Cntr=0.5,0.3

Type RM Length L Ch R = 1 ,862     ,149.54,226.87,202.96
XS GIS Cut Line= 5
 2396252.2917707   623311.843839 2396403.2917707   623242.531339
  2396549.343854  623183.1146723 2396655.7917707  623117.5209223
  2396761.000104   623040.781339
#Sta/Elev= 30
       0   45.11   45.59   43.38   69.15   40.48   89.24   40.22   101.3   39.99
   130.4   40.96  136.01   39.87  153.68   39.57  162.72   38.63  190.94   35.73
  205.28   35.82  207.95   35.22  209.99   33.56  213.68   33.19  217.96   33.38
  218.53   34.25  218.77   35.24  220.05   37.93  222.02   39.06  236.28   45.07
  256.65   49.06  266.66   48.78  277.33   50.38  361.67   51.42  430.51   53.76
  443.04   56.28  448.85   58.71  462.63   61.27  488.39   63.93  579.08   67.48
#Mann= 6 ,-1 , 0
       0     .03       0   89.24     .05       0  162.72     .08       0
  207.95     .04       0  207.95    .045       0  218.77     .04       0
#XS Ineff= 2 , 0
       0                     290       0      65
Permanent Ineff=
       F       F
#Block Obstruct= 1 ,-1
     290     325      65
Bank Sta=207.95,218.77
XS Rating Curve= 0 ,0
Exp/Cntr=0.3,0.1

Type RM Length L Ch R = 1 ,635     ,179.66,248.83,284.47
XS GIS Cut Line= 6
 2396279.5209373  623356.3959223 2396471.3646873  623345.2605057
  2396590.187604   623330.406339 2396718.9167707   623301.937589
  2396832.781354  623266.0417557  2397150.875104  623227.6771723
#Sta/Elev= 30
       0   44.63   86.72   39.31   160.1   37.67  169.83    38.3  181.08   36.96
  255.89   37.25  293.81   36.46  323.27   34.04  323.63   33.13  325.82   32.09
  330.57   32.11  332.48   34.25  344.46   34.59  365.44   39.15  381.77   41.48
  425.57    45.2  464.33   46.76  504.52   47.19     528   47.73  589.39   47.19
   639.8   45.82  709.26   45.34  751.56   45.19  763.79   46.16  781.24   45.21
   831.6   45.42     850   43.18   858.3   43.27  873.61   45.09  884.03   43.74
#Mann= 6 ,-1 , 0
       0     .03       0   86.72     .05       0  323.27    .045       0
  332.48     .04       0  504.52     .03       0  709.26     .04       0
#XS Ineff= 2 , 0
       0  254.99      39               0
Permanent Ineff=
       F       F
Bank Sta=323.27,332.48
XS Rating Curve= 0 ,0
Exp/Cntr=0.5,0.3

Type RM Length L Ch R = 1 ,387     ,82.34,72.29,72.85
XS GIS Cut Line= 6
 2396301.8959373   623377.625089 2396387.8334373   623424.500089
 2396454.2396873  623485.6980057  2396531.062604  623559.9167557
 2396610.4896873  623609.3959223 2396721.1667707  623696.6355057
#Sta/Elev= 30
       0   43.19    9.93   42.93   35.29   40.56   45.57   39.94   87.16    38.6
  113.08   37.46  184.75   36.37     217   34.59   242.8   33.66  244.97   33.59
  248.81   34.11   272.1   33.18  276.04   32.51  279.49   32.98   287.1   32.14
  288.45   31.82  291.03    29.8  293.61   28.62  296.09   28.65  296.58    29.9
  297.09   32.29  300.08   33.01  313.83   33.62   319.7   34.48  338.75   35.76
   401.8   36.17  425.61   37.09  444.64   36.91  503.45   36.57  529.52   36.98
#Mann= 6 ,-1 , 0
       0     .03       0   87.16     .05       0  184.75     .09       0
   287.1     .06       0  297.09     .09       0  444.64     .04       0
#XS Ineff= 2 , 0
       0   282.1   34.71  305.08       0   34.71
Permanent Ineff=
       T       T
Bank Sta=287.1,297.09
XS Rating Curve= 0 ,0
Exp/Cntr=0.5,0.3

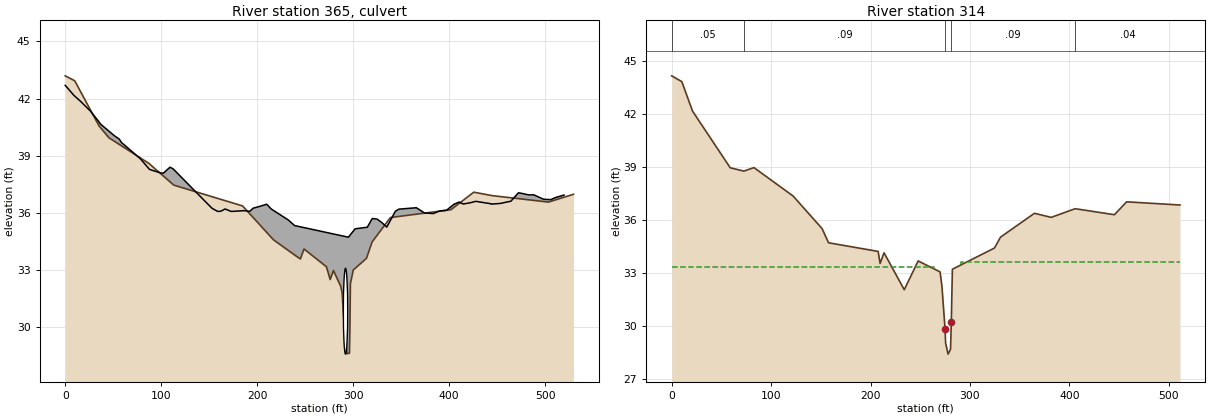
Type RM Length L Ch R = 2 ,365     ,,,
BEGIN DESCRIPTION:
Mill Street Boat Rmp
END DESCRIPTION:
Bridge Culvert--1,0,-1,-1, 0
Deck Dist Width WeirC Skew NumUp NumDn MinLoCord MaxHiCord MaxSubmerge Is_Ogee
15,11,2.6,0, 77, 77, , , 0.95, 0, 1,1,,
       0     .37    9.17   15.84   22.85   25.95   34.25   37.04    49.3   51.48
   56.38   57.99   59.14   61.53   78.33    87.2   87.97   88.63   96.16   98.86
  102.12  109.15  112.48  147.91  153.08  158.91  162.06  166.55  172.91     186
  192.37  195.74  203.57  209.92  214.57  232.22  238.96  294.97  302.02  312.68
  314.64  319.89  324.84   329.8  334.94  343.95  347.47  362.11  364.87  365.18
  365.57  374.37  383.57  390.18  397.15  405.04  405.08  410.29  414.76  422.33
  427.74  442.66  444.54  445.12  453.48  462.37  463.18  464.35  472.18  477.32
  482.47  488.21  498.24  505.99  508.43  511.36   519.7
   42.69   42.67   42.16   41.86   41.51   41.36   40.84   40.65   40.13   40.04
   39.87   39.74   39.67   39.57   38.84   38.32   38.28   38.27   38.15   38.11
   38.08    38.4   38.31    36.5   36.24   36.08   36.09   36.21   36.08   36.12
   36.09   36.25   36.36   36.46   36.21   35.64   35.34   34.73   35.17   35.24
   35.25   35.71   35.68    35.5   35.26   36.09    36.2   36.26   36.27   36.28
   36.28      36   35.97   36.11   36.14   36.46   36.46   36.57   36.47   36.54
   36.61   36.49   36.46   36.47    36.5    36.6    36.6   36.62   37.06   37.01
   36.95   36.95   36.72    36.7   36.76   36.82   36.94
                                                                                
                                                                                
                                                                                
                                                                                
                                                                                
                                                                                
                                                                                
                                                        
       0     .37    9.17   15.84   22.85   25.95   34.25   37.04    49.3   51.48
   56.38   57.99   59.14   61.53   78.33    87.2   87.97   88.63   96.16   98.86
  102.12  109.15  112.48  147.91  153.08  158.91  162.06  166.55  172.91     186
  192.37  195.74  203.57  209.92  214.57  232.22  238.96  294.97  302.02  312.68
  314.64  319.89  324.84   329.8  334.94  343.95  347.47  362.11  364.87  365.18
  365.57  374.37  383.57  390.18  397.15  405.04  405.08  410.29  414.76  422.33
  427.74  442.66  444.54  445.12  453.48  462.37  463.18  464.35  472.18  477.32
  482.47  488.21  498.24  505.99  508.43  511.36   519.7
   42.69   42.67   42.16   41.86   41.51   41.36   40.84   40.65   40.13   40.04
   39.87   39.74   39.67   39.57   38.84   38.32   38.28   38.27   38.15   38.11
   38.08    38.4   38.31    36.5   36.24   36.08   36.09   36.21   36.08   36.12
   36.09   36.25   36.36   36.46   36.21   35.64   35.34   34.73   35.17   35.24
   35.25   35.71   35.68    35.5   35.26   36.09    36.2   36.26   36.27   36.28
   36.28      36   35.97   36.11   36.14   36.46   36.46   36.57   36.47   36.54
   36.61   36.49   36.46   36.47    36.5    36.6    36.6   36.62   37.06   37.01
   36.95   36.95   36.72    36.7   36.76   36.82   36.94
                                                                                
                                                                                
                                                                                
                                                                                
                                                                                
                                                                                
                                                                                
                                                        
BR Coef=-1 , 1 , 0 ,1.25, 0 ,,,0.8,0,2,0,
WSPro=,,,, 1 ,,,, 0 ,,,, 0 ,,,,-1 ,-1 ,-1 , 0 , 0 , 0 , 0 , 0
Culvert=1,4.5,,28,0.024,0.9,1,2,3,28.6,292,28.5,277,Culvert #1  , 0 ,6
Culvert Bottom n=0.024
BC Design=,, 0 ,, 0 ,,,,,,
BC Use User HTab Curves=0
BC User HTab FreeFlow(D)= 0

Type RM Length L Ch R = 1 ,314     ,455.73,314.24,365.51
XS GIS Cut Line= 3
 2396270.6459373  623457.0521723 2396486.7917707  623613.3021723
 2396682.1042707   623760.437589
#Sta/Elev= 30
       0   44.16   10.21   43.83      21   42.16   58.88   38.95    72.6   38.76
   82.75   38.96   122.1   37.35  151.31    35.5  157.78    34.7  207.64   34.21
  209.64   33.53  213.58   34.13  233.93   32.04  247.89   33.67  269.94   33.05
  271.83   32.23  274.94   29.83  275.51   29.02  277.99   28.39  280.47   28.67
  281.24   30.21  282.32    33.2  324.61    34.4  330.78   35.02  364.83   36.37
  381.72   36.14  405.82   36.63  445.32   36.29  457.54   37.02  511.24   36.84
#Mann= 5 ,-1 , 0
       0     .05       0    72.6     .09       0  274.94    .045       0
  281.24     .09       0  405.82     .04       0
#XS Ineff= 2 , 0
       0  263.83    33.3  291.02       0    33.6
Permanent Ineff=
       F       F
Bank Sta=274.94,281.24
XS Rating Curve= 0 ,0
Exp/Cntr=0.5,0.3

Chan Stop Cuts=-1
Use User Specified Reach Order=0
User Specified Reach Order=Contentnea Trib8,Main