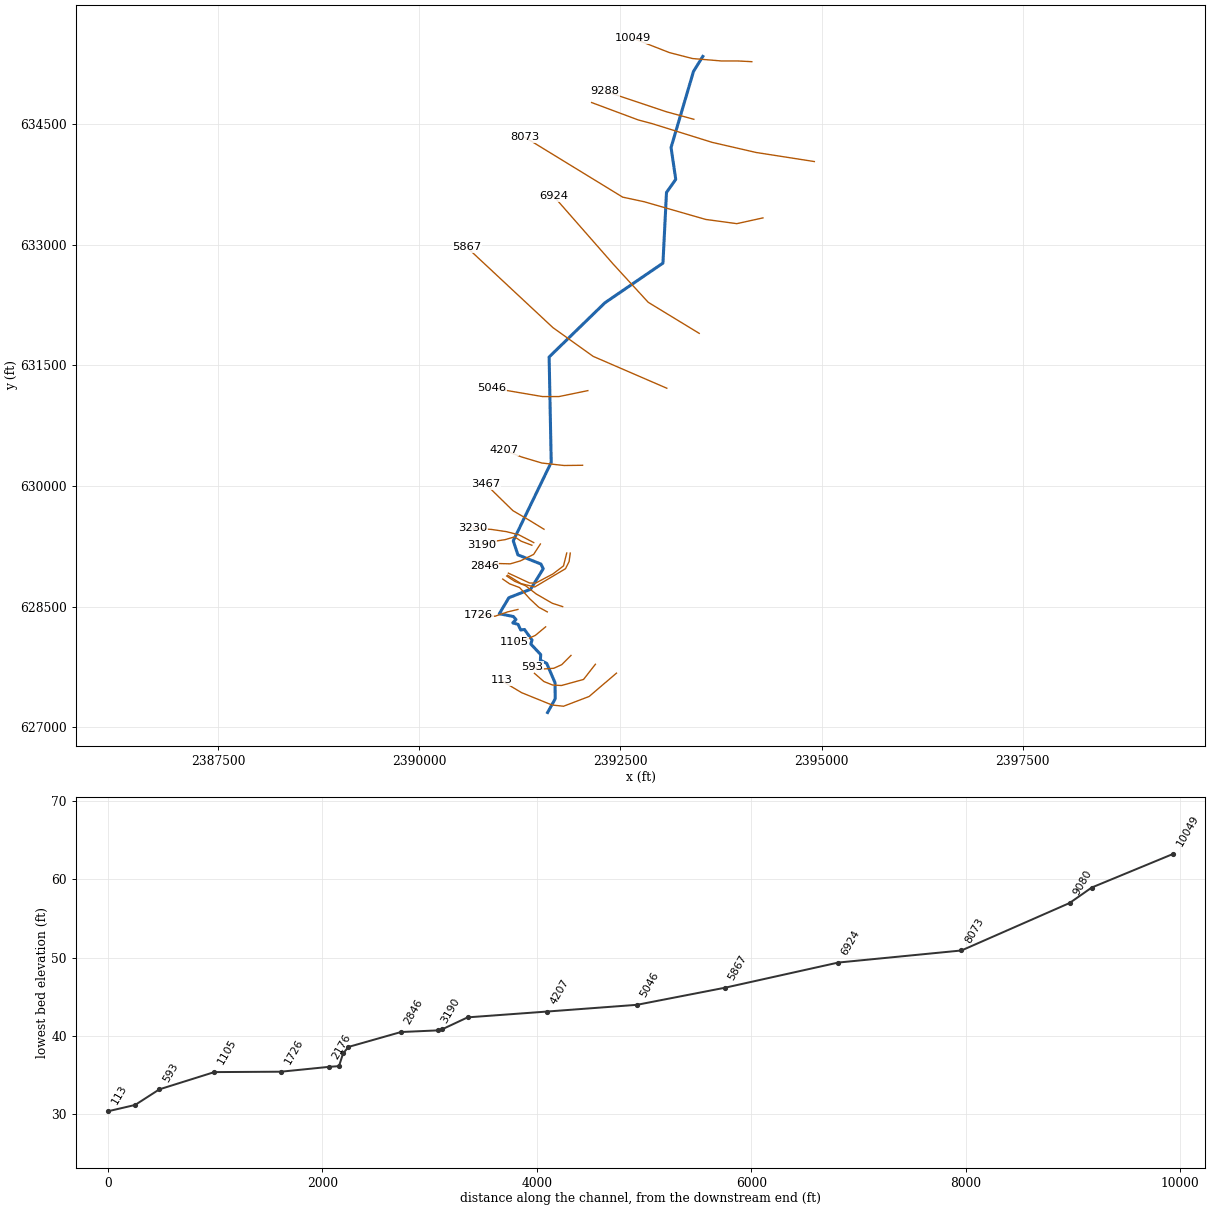
--- LDS_Contentnea_Trib9.prj (project) ---

Proj Title=LDS_Contentnea_Crk_Trib9
Current Plan=p01
Default Exp/Contr=0.3,0.1
English Units
Geom File=g01
Flow File=f01
Flow File=f02
Plan File=p01
Plan File=p02
Y Axis Title=Elevation
X Axis Title(PF)=Main Channel Distance
X Axis Title(XS)=Station
BEGIN DESCRIPTION:
END DESCRIPTION:
DSS Export Rating Curves= 0
DSS Export Rating Curve Sorted= 0
DSS Export Volume Flow Curves= 0
DXF OffsetX= 0
DXF OffsetY= 0
DXF ScaleX= 1
DXF ScaleY= 10

--- LDS_Contentnea_Trib9.p01 (plan) ---

Plan Title=LDS_Contentnea_Crk_Trib9
Program Version=4.00
Short Identifier=Fway
Geom File=g01
Flow File=f01
Subcritical Flow
K Sum by GR= 0
Std Step Tol= 0.01
Critical Tol= 0.01
Num of Std Step Trials= 20
Max Error Tol= 0.3
Flow Tol Ratio= 0.001
Split Flow NTrial= 30
Split Flow Tol= 0.02
Split Flow Ratio= 0.02
Log Output Level= 0
Friction Slope Method= 1
Unsteady Friction Slope Method= 2
Unsteady Bridges Friction Slope Method= 1
Parabolic Critical Depth
Global Vel Dist= 0 , 0 , 0
Global Log Level= 0
CheckData=True
Encroach Param=-1 ,10,10, 2
Encroach River=Contentnea
Encroach Reach=Trib9
Encroach Node=10049
       1     600  677.41
Encroach Node=9288
       4      .7
Encroach Node=9080
       1    1700 1820.68
Encroach Node=8073
       4      .7
Encroach Node=6924
       4      .7
Encroach Node=5867
       1    1394    1463
Encroach Node=5046
       4      .7
Encroach Node=4207
       4      .7
Encroach Node=3467
       4      .7
Encroach Node=3230
       4      .7
Encroach Node=3190
       1   209.5     291
Encroach Node=2846
       4      .7
Encroach Node=2356
       1     550     677
Encroach Node=2306
       1     630     820
Encroach Node=2268
       1     370     515
Encroach Node=2176
       1     340   415.1
Encroach Node=1726
       1   210.2  253.83
Encroach Node=1105
       1     197  250.45
Encroach Node=593
       1     266     344
Encroach Node=367
       4      .7
Encroach Node=113
       4      .7
Computation Interval=1HOUR
Output Interval=1HOUR
Run HTab= 0
Run UNet= 0
Run PostProcess= 0
Run WQNet= 0
UNET Theta= 1
UNET Theta Warmup= 1
UNET ZTol= 0.02
UNET ZSATol= 0.05
UNET MxIter= 20
UNET MaxInSteps= 0
UNET DtIC= 0
UNET DtMin= 0
UNET MaxCRTS= 20
UNET WFStab= 2
UNET SFStab= 1
UNET WFX= 1
UNET SFX= 1
UNET DSS MLevel= 4
UNET DZMax Abort= 100
UNET Convert EG Bridges=-1
UNET Use Existing IB Tables=-1
UNET Froude Reduction=False
UNET Froude Limit= 1
UNET Froude Power= 10
UNET Time Slicing=0,0, 5
Instantaneous Interval=1HOUR
Write IC File= 0
Echo Input=False
Echo Output=False
Write Detailed= 0
Detailed Automatic Start=False, 10
WQ ULTIMATE=-1
WQ Max Comp Step=1HOUR
WQ Output Interval=15MIN
WQ Output Selected Increments= 0
WQ Output face flow=0
WQ Output face velocity=0
WQ Output face area=0
WQ Output face dispersion=0
WQ Output cell volume=0
WQ Output cell surface area=0
WQ Output cell continuity=0
WQ Output face conc=0
WQ Output face dconc_dx=0
WQ Output face courant=0
WQ Output face peclet=0
WQ Output face adv mass=0
WQ Output face disp mass=0
WQ Output cell mass=0
WQ Output cell source sink temp=0
WQ Output cell source sink nsm=0
WQ Output MaxMinRange=-1
WQ Daily Max Min Mean=-1
WQ Daily Range=0
WQ Daily Time=0
WQ Create Restart=0
WQ Fixed Restart=0
WQ System Summary=False
Sorting and Armoring Iterations= 10
XS Update Threshold= 0.02
Hydraulics Update Threshold= 0.02
Energy Slope Method= 1
Volume Change Method= 0
XS Weighting Method= 0
Number of US Weighted Cross Sections= 1
Number of DS Weighted Cross Sections= 1
Upstream XS Weight=0.25
Main XS Weight=0.5
Downstream XS Weight=0.25
Number of DS XS's Weighted with US Boundary= 1
Upstream Boundary Weight= 1
Weight of XSs Associated with US Boundary= 0
Number of US XS's Weighted with DS Boundary= 1
Downstream Boundary Weight= 0.5
Weight of XSs Associated with DS Boundary= 0.5
Sediment Output Level= 4
Mass or Volume Output= 0
Output Increment Type= 1
Profile and TS Output Increment= 10
XS Output Flag= 0
XS Output Increment= 10
Disregard all LS=0
Disregard all Conn=0
Disregard all Breaches=0
Disregard all Pumps=0

--- LDS_Contentnea_Trib9.p02 (plan) ---

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Plan Title=Multi_Profile
Short Identifier=Multi_Prof
Geom File=g01
Flow File=f02

--- LDS_Contentnea_Trib9.f01 (steady flow) ---

Flow Title=LDS_Contentnea_Crk_Trib9
Program Version=4.00
Number of Profiles= 2
Profile Names=WSEL100,WSFWAY
River Rch & RM=Contentnea,Trib9           ,10049
     620     620
Boundary for River Rch & Prof#=Contentnea,Trib9           , 1
Up Type= 0
Dn Type= 3
Dn Slope=0.003
Boundary for River Rch & Prof#=Contentnea,Trib9           , 2
Up Type= 0
Dn Type= 3
Dn Slope=0.003
DSS Import GetInterval= 0
DSS Import GetPeak= 0
DSS Import FillOption= 0

--- LDS_Contentnea_Trib9.f02 (steady flow) ---

Flow Title=Multi_Profile
Program Version=4.00
Number of Profiles= 8
Profile Names=10-yr,25-yr,50-yr,500-yr,100-yr-10%,100-yr-20%,100-yr-35%,100-yr
River Rch & RM=Contentnea,Trib9           ,10049
     260     380     490    1010    1090    1390    1700     620
Boundary for River Rch & Prof#=Contentnea,Trib9           , 1
Up Type= 0
Dn Type= 3
Dn Slope=0.003
Boundary for River Rch & Prof#=Contentnea,Trib9           , 2
Up Type= 0
Dn Type= 3
Dn Slope=0.003
DSS Import GetInterval= 0
DSS Import GetPeak= 0
DSS Import FillOption= 0

--- LDS_Contentnea_Trib9.g01 (geometry) ---

Geom Title=LDS_Contentnea_Crk_Trib9
Program Version=4.00

River Reach=Contentnea      ,Trib9
Reach XY= 30
2393523.65610157 635341.646433072393407.73162931635154.803460091
2393128.94155423634209.6845656482393187.00000001633813.000000015
2393072.00000003         633650.2393028.00000001         632772.
2392306.73318316632279.0222206122391612.94803485631604.786973491
2391638.86056392630295.5223453192391166.97977088629320.392960757
2391224.26009832629145.8243436962391510.58794965629031.052729607
2391539.30189954 628972.619543942391382.46290764628717.585704893
2391112.42707807 628612.571771192390993.60726069 628413.31881237
2391167.98112369628379.0507167432391200.75000003     628341.4375
      2391160.75628299.5000000152391226.50000003628281.250000015
2391259.25000001     628211.93752391306.50000003     628217.4375
 2391400.4397334628085.9811496142391385.00000001      628036.875
2391508.00000003627906.3352300522391504.50000001      627835.375
2391582.72011288627796.2838186032391686.04496771 627556.14304623
2391688.84311594627356.2383298722391594.01971814627185.500919774

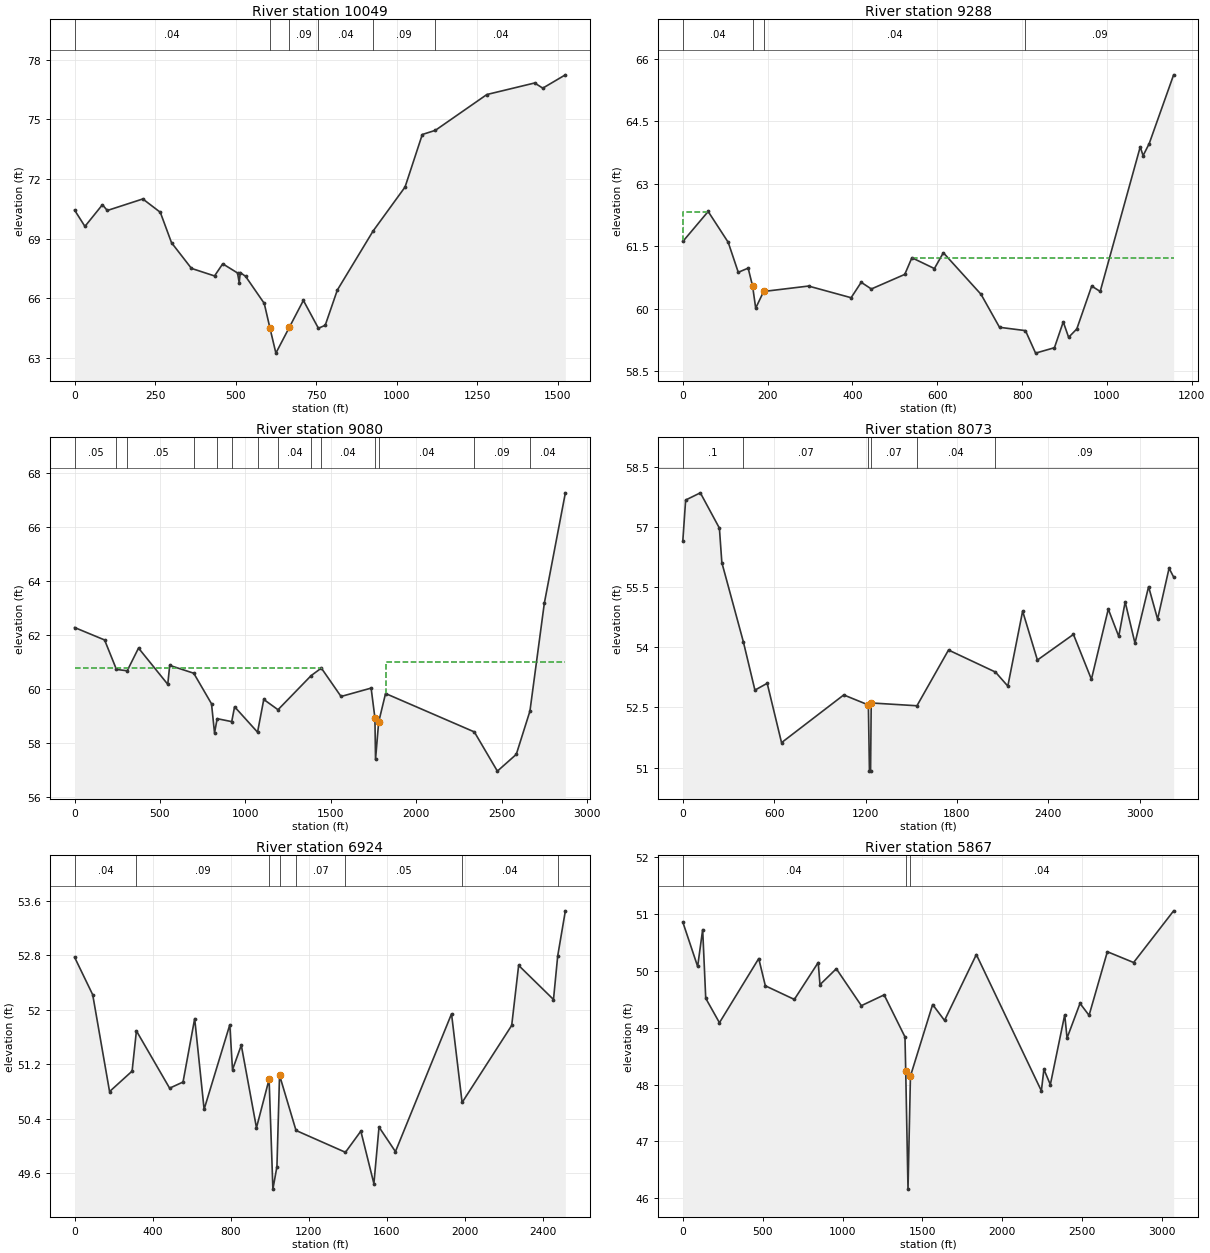
Type RM Length L Ch R = 1 ,10049   ,771.66,761.41,724.22
XS GIS Cut Line= 6
 2394133.3406573  635275.8959911 2393968.4101018  635284.5765466
 2393760.0767684  635284.5765466 2393395.4934351  635314.9584911
 2393109.0351018  635388.7432133 2392653.3059351  635566.6946022
#Sta/Elev= 30
       0   70.43   32.15   69.61   86.48    70.7  101.59   70.41  211.94   70.99
  266.24   70.32  301.14   68.79  362.97    67.5  434.71   67.12  460.13   67.73
  506.13   67.27  511.29   66.78  514.58   67.29  531.14    67.1  589.11   65.74
  606.65   64.51  625.27   63.24  667.41   64.55  710.65   65.89  757.32   64.49
   778.5   64.64  816.11   66.41  926.84   69.37 1026.45   71.59    1080   74.23
 1120.59   74.44  1280.6   76.24 1429.01   76.82 1454.25   76.56  1524.4   77.23
#Mann= 6 ,-1 , 0
       0     .04       0  606.65    .045       0  667.41     .09       0
  757.32     .04       0  926.84     .09       0 1120.59     .04       0
Bank Sta=606.65,667.41
XS Rating Curve= 0 ,0
Exp/Cntr=0.3,0.1

Type RM Length L Ch R = 1 ,9288    ,209.85,207.54,206
XS GIS Cut Line= 3
 2393412.2737057  634559.7527326 2393070.2557329  634653.6400193
 2392309.0980877  634908.4769402
#Sta/Elev= 30
       0   61.62   59.71   62.34  106.97    61.6  130.69   60.88  154.01   60.98
  164.46   60.55  171.79   60.02  190.54   60.42  296.34   60.55  396.79   60.27
  420.58   60.64  444.55   60.48  523.35   60.83  540.14   61.23  593.21   60.97
   614.3   61.35  703.28   60.35  746.76   59.56  807.95   59.48  831.82   58.94
  876.28   59.07  897.08   59.69   909.7   59.32  928.99   59.52  964.14   60.55
  984.17   60.42 1078.59   63.89 1085.35   63.68 1099.77   63.97 1157.36   65.62
#Mann= 4 ,-1 , 0
       0     .04       0  164.46    .045       0  190.54     .04       0
  807.95     .09       0
#XS Ineff= 2 , 0
           59.87   62.33  540.13           61.23
Permanent Ineff=
       F       F
#Block Obstruct= 2 , 0
       0                  540.13       0   61.23
Bank Sta=164.46,190.54
XS Rating Curve= 0 ,0
Exp/Cntr=0.3,0.1

Type RM Length L Ch R = 1 ,9080    ,973.05,1007.81,963.52
XS GIS Cut Line= 6
 2394910.2503795  634034.5765466 2394185.4239907  634147.4237689
 2393638.5489906  634273.2918244 2392887.6809351  634507.6668244
 2392722.7503795  634551.0696022 2392141.1531573  634768.0834911
#Sta/Elev= 30
       0   62.27  175.67   61.81   245.1   60.72  308.03   60.67  374.36   61.51
  545.53   60.17  556.94   60.87  697.66   60.58   801.7   59.45  819.39   58.37
  834.73    58.9  920.07   58.79  936.74   59.34 1071.21    58.4 1107.62   59.61
 1191.03   59.23  1384.7   60.49 1444.75   60.77 1560.07   59.72 1736.17   60.03
 1758.37   58.93 1761.95   57.39 1780.23   58.77 1820.68   59.83  2340.4   58.41
 2475.35   56.96 2586.04   57.58 2665.95   59.18 2750.26   63.17 2873.41   67.25
#Mann= 14 ,-1 , 0
       0     .05       0   245.1     .03       0  308.03     .05       0
  697.66     .04       0  834.73     .08       0  920.07     .04       0
 1071.21     .08       0 1191.03     .04       0  1384.7     .08       0
 1444.75     .04       0 1758.37    .045       0 1780.23     .04       0
  2340.4     .09       0 2665.95     .04       0
#XS Ineff= 2 , 0
       0 1447.14   60.78 1820.68       0      61
Permanent Ineff=
       F       F
Bank Sta=1758.37,1780.23
XS Rating Curve= 0 ,0
Exp/Cntr=0.3,0.1

Type RM Length L Ch R = 1 ,8073    ,1192.75,1148.73,989.79
XS GIS Cut Line= 6
 2394271.3301844  633334.1713292 2393946.3979281  633262.4950961
 2393559.3462698   633315.057667 2392794.7997842  633534.8647816
 2392527.2085143  633592.2057681  2391307.819824  634338.3959911
#Sta/Elev= 30
       0   56.66   18.35   57.67  114.86   57.85     240   56.97   256.1   56.11
  397.66   54.13  473.25   52.93  553.87    53.1  648.02   51.62 1056.49   52.81
 1218.17   52.56 1225.19   50.91 1232.61   50.91 1236.86   52.61 1537.14   52.54
 1744.37   53.93 2052.74   53.38 2133.75   53.03 2231.03    54.9    2328   53.68
 2564.68   54.32 2682.62    53.2 2793.44   54.95 2862.03   54.27  2904.3   55.13
 2968.65    54.1 3058.02   55.51 3117.26    54.7 3192.62   55.97 3222.51   55.75
#Mann= 6 ,-1 , 0
       0      .1       0  397.66     .07       0 1218.17     .05       0
 1236.86     .07       0 1537.14     .04       0 2052.74     .09       0
Bank Sta=1218.17,1236.86
XS Rating Curve= 0 ,0
Exp/Cntr=0.3,0.1

Type RM Length L Ch R = 1 ,6924    ,988.91,1056.74,1089.79
XS GIS Cut Line= 4
2393478.99671477631898.5603342352392844.44379559632285.044350967
  2392407.247982632762.4547673172391666.76703931 633606.86285983
#Sta/Elev= 30
       0   52.77   92.84   52.22  179.16    50.8   294.6    51.1  316.69   51.69
  486.67   50.85  555.38   50.94  615.09   51.87  663.36   50.54  794.95   51.78
  808.75   51.12  853.75   51.48  931.49   50.27  996.16   50.98 1015.65   49.37
 1036.28    49.7 1049.64   51.04 1134.06   50.23 1387.16   49.91 1466.02   50.22
 1532.87   49.45 1559.11   50.28 1643.22   49.92 1930.47   51.94  1984.6   50.64
 2238.58   51.77 2274.13   52.65 2452.58   52.15 2474.22   52.79 2513.43   53.45
#Mann= 8 ,-1 , 0
       0     .04       0  316.69     .09       0  996.16     .05       0
 1049.64     .08       0 1134.06     .07       0 1387.16     .05       0
  1984.6     .04       0 2474.22     .09       0
Bank Sta=996.16,1049.64
XS Rating Curve= 0 ,0
Exp/Cntr=0.3,0.1

Type RM Length L Ch R = 1 ,5867    ,583.72,820.57,884.75
XS GIS Cut Line= 4
 2393076.2790091631216.5384133612392160.42100108631612.760672152
2391660.27159245631970.0102497492390591.67399062632966.868213296
#Sta/Elev= 30
       0   50.86   92.74   50.08  124.17   50.73  143.37   49.52  229.19   49.09
  475.35   50.22  516.66   49.74  698.29    49.5  847.84   50.15  858.85   49.76
  961.25   50.04 1118.06   49.39 1260.75   49.58 1391.25   48.84 1395.94   48.24
 1410.24   46.16 1425.51   48.15 1564.46   49.41 1638.98   49.13 1838.25   50.29
 2245.58   47.89 2261.28   48.27 2301.67      48 2391.81   49.23 2406.34   48.82
  2487.5   49.43 2544.26   49.22 2658.78   50.34 2823.24   50.15 3073.91   51.06
#Mann= 3 , 0 , 0
       0     .04       0 1395.94    .045       0 1425.51     .04       0
Bank Sta=1395.94,1425.51
XS Rating Curve= 0 ,0
Exp/Cntr=0.3,0.1

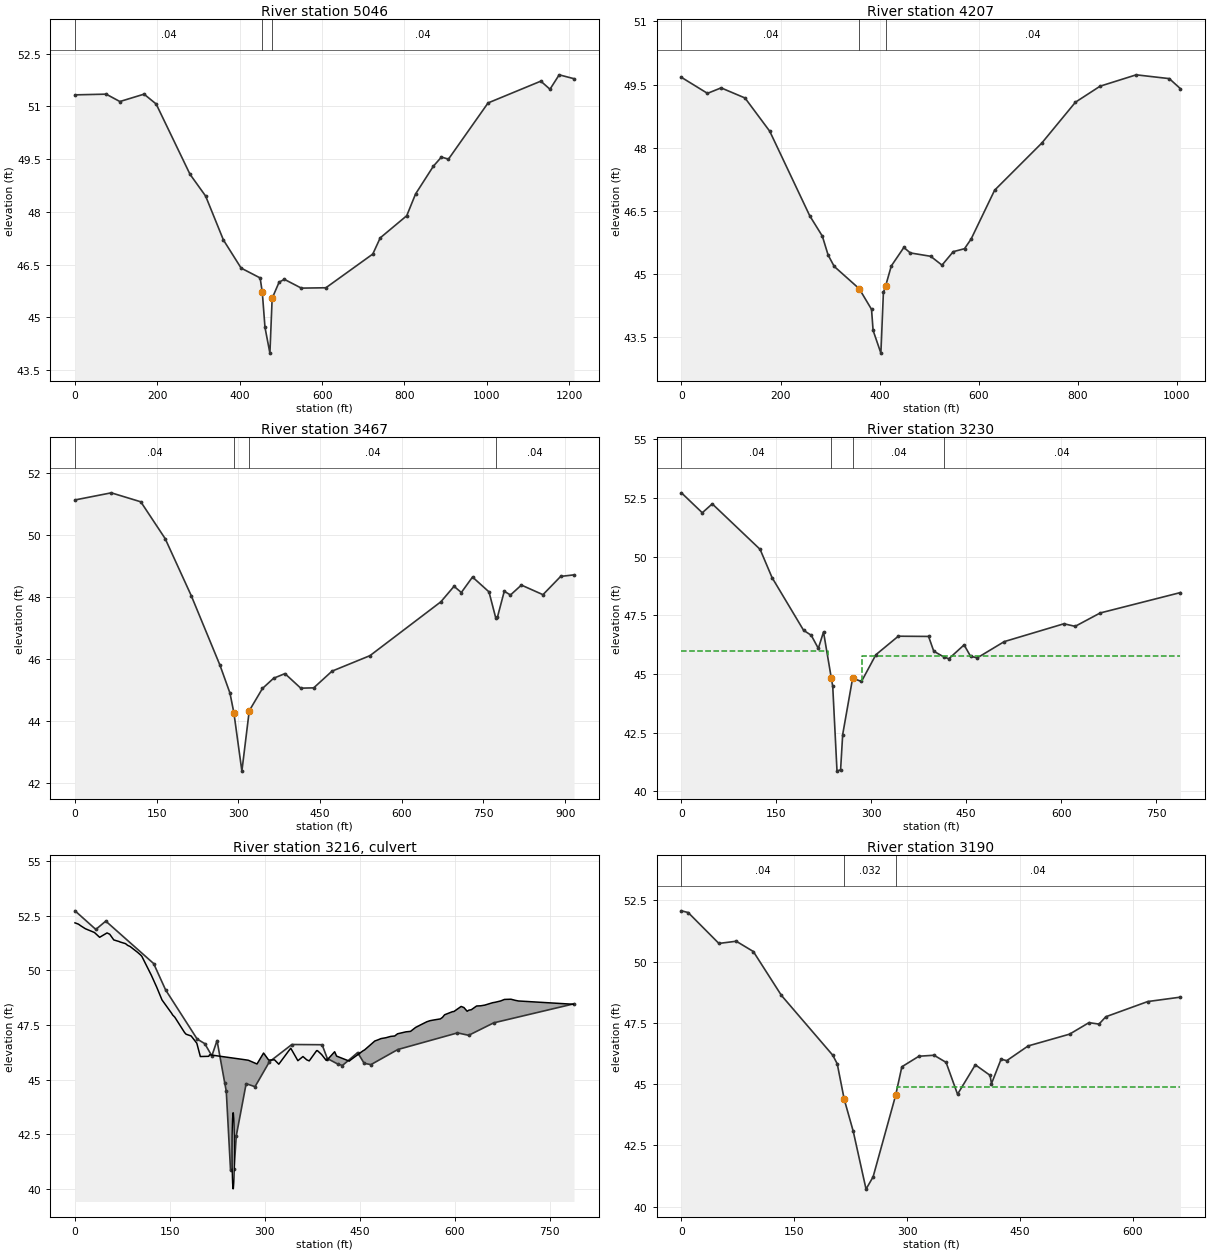
Type RM Length L Ch R = 1 ,5046    ,886.53,839.52,806.17
XS GIS Cut Line= 4
 2392094.1959051  631186.8401469 2391735.7761871   631113.077887
 2391529.9840566   631113.077887 2390899.2286792  631220.3830866
#Sta/Elev= 30
       0   51.33   75.68   51.35  108.99   51.14  167.67   51.35  197.07   51.07
  279.24   49.07  317.16   48.45  360.37    47.2  403.36    46.4  449.49   46.12
  454.77   45.71  461.31   44.71  473.24   43.98  478.68   45.54  495.59      46
  508.37   46.08  549.55   45.83  609.16   45.84  723.04    46.8  741.05   47.26
  805.43   47.89   826.9   48.51  870.12    49.3  889.68   49.56  906.74    49.5
 1002.88    51.1    1131   51.72  1153.2   51.49 1175.55    51.9 1211.54   51.79
#Mann= 3 , 0 , 0
       0     .04       0  454.77    .045       0  478.68     .04       0
Bank Sta=454.77,478.68
XS Rating Curve= 0 ,0
Exp/Cntr=0.3,0.1

Type RM Length L Ch R = 1 ,4207    ,825.46,739.7,635.61
XS GIS Cut Line= 5
 2392028.9594963  630258.8995919 2391797.7957333  630256.0805216
 2391521.5268457  630287.0902947 2391267.8105204  630363.2051923
 2391050.7421088  630447.7773007
#Sta/Elev= 30
       0   49.67   52.49   49.29   80.03   49.42  128.23   49.18  178.17   48.39
  258.97   46.38  284.28    45.9  295.96   45.45  308.23   45.18  358.74   44.65
  383.58   44.16  386.74   43.66  402.46   43.12  407.53   44.56  411.88   44.71
  423.45   45.19  448.82   45.63  461.82    45.5  502.96   45.42  525.77   45.21
   548.5   45.53  571.21    45.6  584.54   45.83  632.01   46.99  727.23   48.11
  795.11   49.08  844.83   49.46  917.74   49.73  984.47   49.64 1007.03    49.4
#Mann= 3 , 0 , 0
       0     .04       0  358.74    .045       0  411.88     .04       0
Bank Sta=358.74,411.88
XS Rating Curve= 0 ,0
Exp/Cntr=0.3,0.1

Type RM Length L Ch R = 1 ,3467    ,224.25,237.01,333.98
XS GIS Cut Line= 5
 2391549.1231354  629463.5716212 2391364.6369672  629576.7790426
 2391163.3793292  629694.1793314 2390999.8574983  629853.5082949
 2390829.8795127  630020.8462272
#Sta/Elev= 30
       0   51.14    66.6   51.37  120.83   51.08   165.6   49.89  213.43   48.05
  266.24    45.8  284.57    44.9  291.81   44.26  306.45   42.38  319.97   44.33
  344.22   45.05  364.69   45.38   385.5   45.53  414.54   45.06  438.35   45.07
     472   45.61  541.62   46.11  671.83   47.85  696.01   48.35  709.39   48.15
  729.93   48.65   760.2   48.17  772.43   47.34  775.65   47.35  788.24   48.19
  799.63   48.07  819.67   48.39  859.27   48.08  891.82   48.67  916.28   48.72
#Mann= 4 ,-1 , 0
       0     .04       0  291.81    .045       0  319.97     .04       0
  772.43     .04       0
Bank Sta=291.81,319.97
XS Rating Curve= 0 ,0
Exp/Cntr=0.5,0.3

Type RM Length L Ch R = 1 ,3230    ,52.46,40.66,115.1
XS GIS Cut Line= 6
 2391422.0157394  629297.4447224 2391235.9363892  629394.8118243
 2391166.6975613  629412.1215313 2391082.3127397   629433.758665
 2390891.9059628  629461.8869389 2390664.7160585  629477.0329325
#Sta/Elev= 30
       0   52.72   32.91   51.87   48.66   52.25  124.32   50.31  143.15   49.11
  193.06   46.86  205.09   46.65  216.32   46.09  224.52   46.79  236.81   44.83
   239.1   44.47  245.84   40.86  251.52   40.92  254.82   42.42  270.52   44.82
  284.54   44.68  307.27   45.82  342.72   46.61  390.57    46.6  398.77   45.97
  415.07   45.72  422.67   45.65   446.7   46.24  457.01   45.75  467.72   45.69
  510.19   46.38  604.52   47.14  622.21   47.03  661.82    47.6  788.67   48.47
#Mann= 4 ,-1 , 0
       0     .04       0  236.81    .032       0  270.52     .04       0
  415.07     .04       0
#XS Ineff= 2 , 0
       0  231.08      46     285       0   45.77
Permanent Ineff=
       F       F
Bank Sta=236.81,270.52
XS Rating Curve= 0 ,0
Exp/Cntr=0.5,0.3

Type RM Length L Ch R = 2 ,3216    ,,,
BEGIN DESCRIPTION:
Private Drive off SR 1247
END DESCRIPTION:
Bridge Culvert--1,0,-1,-1, 0
Deck Dist Width WeirC Skew NumUp NumDn MinLoCord MaxHiCord MaxSubmerge Is_Ogee
10,17,2.6,0, 94, 93, , , 0.95, 0, 0,0,,
       0     5.5    9.41    16.5    30.7   30.73   38.94   50.63   54.89   61.31
   70.45   70.76   79.86    83.3    87.1   99.04  103.75  105.64   120.6  129.16
  137.46  152.89   154.3  157.72  173.12  175.61  183.61  192.52  198.11  211.42
  212.75  267.22  274.07  287.67  298.04   306.1  315.36   322.1  337.26  341.01
  352.27  360.31  366.27  370.18  381.92  383.17  389.85   396.9  398.15  410.38
  413.45  433.62  434.03  434.65  435.83  455.56  457.57   469.1   473.8  477.68
   480.3  483.58  491.38  498.85  505.31  509.79  523.15  530.29  538.28  549.12
  556.07  561.26   568.8  577.47   580.8  584.19  596.49  598.97  610.29  614.67
  619.79  622.54  626.38  634.69  641.35  647.54  659.99  663.93  672.66   678.7
  689.03  695.72  700.84  787.49
   52.17   52.11   52.03    51.9   51.73   51.73   51.51   51.71   51.65   51.39
   51.31    51.3   51.22   51.14   51.09   50.82    50.7   50.64   49.78   49.23
   48.65   48.03   47.96   47.86   47.16   47.08      47   46.67   46.06   46.07
   46.14   45.92   45.89   45.72   46.22    45.9   45.91   45.71    46.3   46.44
   45.87   46.06   45.91   45.86   46.33   46.33   46.15   45.89   45.89   46.28
   46.08   45.85   45.87   45.88   45.91   46.33   46.36   46.65   46.77   46.81
   46.84   46.88   46.92   46.98      47    47.1   47.19   47.21   47.39   47.55
   47.65    47.7   47.74   47.78   47.85   47.97   48.11   48.12   48.35    48.3
   48.13   48.18    48.2   48.37   48.38   48.41   48.52   48.54    48.6   48.67
   48.68   48.63    48.6   48.45
                                                                                
                                                                                
                                                                                
                                                                                
                                                                                
                                                                                
                                                                                
                                                                                
                                                                                
                                
       0     5.5    9.41    16.5    30.7   30.73   38.94   50.63   54.89   61.31
   70.45   70.76   79.86    83.3    87.1   99.04  103.75  105.64   120.6  129.16
  137.46  152.89   154.3  157.72  173.12  175.61  183.61  192.52  198.11  211.42
  212.75  267.22  274.07  287.67  298.04   306.1  315.36   322.1  337.26  341.01
  352.27  360.31  366.27  370.18  381.92  383.17  389.85   396.9  398.15  410.38
  413.45  433.62  434.03  434.65  435.83  455.56  457.57   469.1   473.8  477.68
   480.3  483.58  491.38  498.85  505.31  509.79  523.15  530.29  538.28  549.12
  556.07  561.26   568.8  577.47   580.8  584.19  596.49  598.97  610.29  614.67
  619.79  622.54  626.38  634.69  641.35  647.54  659.99  663.93  672.66   678.7
  689.03  695.72  700.84
   52.17   52.11   52.03    51.9   51.73   51.73   51.51   51.71   51.65   51.39
   51.31    51.3   51.22   51.14   51.09   50.82    50.7   50.64   49.78   49.23
   48.65   48.03   47.96   47.86   47.16   47.08      47   46.67   46.06   46.07
   46.14   45.92   45.89   45.72   46.22    45.9   45.91   45.71    46.3   46.44
   45.87   46.06   45.91   45.86   46.33   46.33   46.15   45.89   45.89   46.28
   46.08   45.85   45.87   45.88   45.91   46.33   46.36   46.65   46.77   46.81
   46.84   46.88   46.92   46.98      47    47.1   47.19   47.21   47.39   47.55
   47.65    47.7   47.74   47.78   47.85   47.97   48.11   48.12   48.35    48.3
   48.13   48.18    48.2   48.37   48.38   48.41   48.52   48.54    48.6   48.67
   48.68   48.63    48.6
                                                                                
                                                                                
                                                                                
                                                                                
                                                                                
                                                                                
                                                                                
                                                                                
                                                                                
                        
BR Coef=-1 , 1 , 0 ,1.25, 0 ,,,0.8,0,2,0,
WSPro=,,,, 1 ,,,, 0 ,,,, 0 ,,,,-1 ,-1 ,-1 , 0 , 0 , 0 , 0 , 0
Culvert=1,3.5,,25,0.024,0.5,1,2,1,40,250,39.9,250,Culvert #1  , 0 ,6
Culvert Bottom n=0.024
BC Design=,, 0 ,, 0 ,,,,,,
BC Use User HTab Curves=0
BC User HTab FreeFlow(D)= 0

Type RM Length L Ch R = 1 ,3190    ,173.63,343.68,313.72
XS GIS Cut Line= 6
 2391398.2148923  629264.9890218 2391266.2283765  629314.7544294
 2391184.0072683  629368.8472638 2391065.0030327  629334.2278498
 2390965.4722175  629319.0818562 2390772.9017271  629269.3164486
#Sta/Elev= 30
       0   52.07    8.94      52   49.78   50.74   72.86   50.83   95.61   50.41
  132.96   48.62  201.26   46.18  207.18   45.83  216.49   44.38  228.45   43.08
  245.49   40.72  254.87   41.22  284.81   44.54  293.12   45.71  315.83   46.14
  335.93   46.18  351.93   45.89  367.18   44.59  390.84   45.79  410.45   45.36
  412.31   45.02  425.09   46.02  432.63   45.96  461.09   46.56  516.16   47.04
  542.01   47.51   555.3   47.45  564.39   47.75  620.13   48.37  663.66   48.55
#Mann= 3 , 0 , 0
       0     .04       0  216.49    .032       0  284.81     .04       0
#XS Ineff= 2 , 0
       0  213.39   44.71  286.75       0   44.87
Permanent Ineff=
       F       F
Bank Sta=216.49,284.81
XS Rating Curve= 0 ,0
Exp/Cntr=0.5,0.3

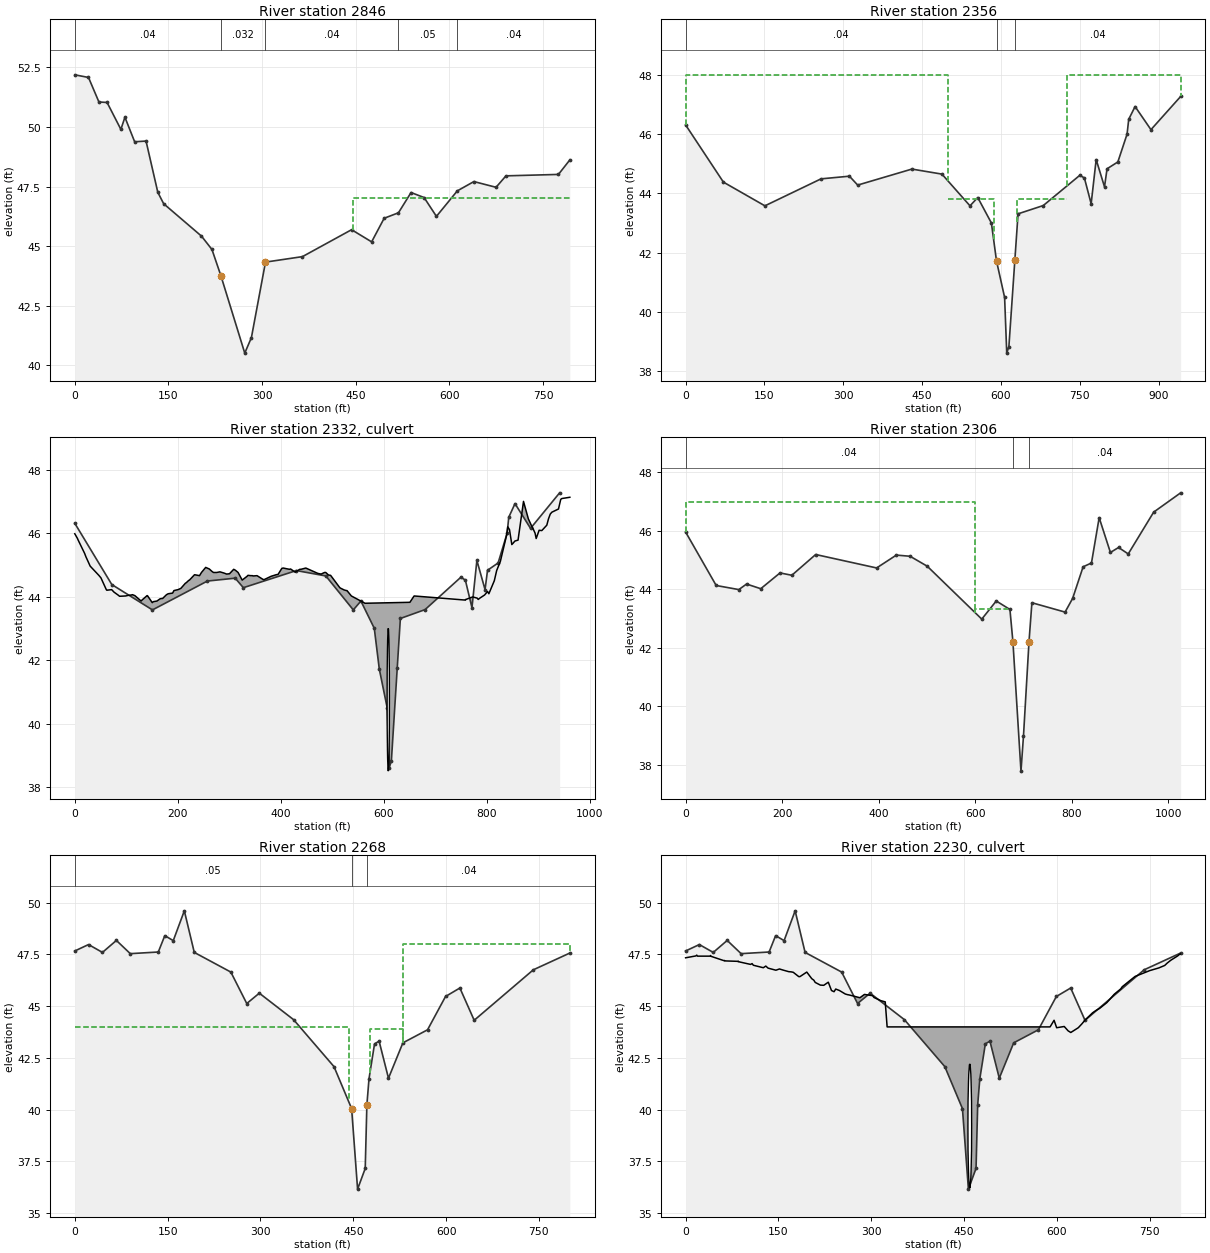
Type RM Length L Ch R = 1 ,2846    ,412.7,489.61,186.75
XS GIS Cut Line= 6
 2391504.2368477  629280.1350154 2391419.8520261   629150.312213
 2391255.4098096  629070.2548181 2391129.9144339  629033.4716907
 2390971.9633576  629037.7991175 2390807.5211412   629011.834557
#Sta/Elev= 30
       0   52.19   21.94   52.08   38.65   51.05   51.73   51.03   73.81    49.9
   80.29   50.41   95.88   49.38  114.13   49.41  132.97   47.26  142.35   46.78
  202.96   45.42  219.71   44.86  234.01   43.76  272.27   40.51   282.9   41.16
  305.46   44.33  364.67   44.56  443.38   45.69   475.5   45.18  495.55   46.17
  518.46    46.4  538.63   47.25  559.53   47.04  579.28   46.25  612.75   47.32
   639.3   47.71  674.79   47.47  690.66   47.95  774.72   48.01     793   48.62
#Mann= 5 ,-1 , 0
       0     .04       0  234.01    .032       0  305.46     .04       0
  518.46     .05       0  612.75     .04       0
#XS Ineff= 2 , 0
       0                     445       0      47
Permanent Ineff=
       F       F
Bank Sta=234.01,305.46
XS Rating Curve= 0 ,0
Exp/Cntr=0.5,0.3

Type RM Length L Ch R = 1 ,2356    ,60.73,50.29,43.38
XS GIS Cut Line= 6
 2391831.8667687  629168.4106269 2391791.4303117  629007.7880338
 2391661.1350614  628908.9433611 2391445.4739574  628794.3733996
  2391370.217218  628795.4966346 2391106.2570126  628917.9292405
#Sta/Elev= 30
       0   46.31    71.9   44.38  150.87   43.58  257.67   44.49  311.63   44.58
  327.42   44.28   430.5   44.82   487.7   44.65  541.07   43.58  555.83   43.86
  581.81      43  591.51   41.72  606.93   40.49  610.99   38.61  615.07   38.83
  626.39   41.74   632.5   43.31  680.52   43.59  750.02   44.61  758.74   44.52
  771.58   43.65  781.14   45.14     797   44.22  801.83   44.83  822.38   45.06
  839.93      46  843.07    46.5  855.18   46.93  885.36   46.15  941.89   47.27
#Mann= 3 , 0 , 0
       0     .04       0  591.51     .05       0  626.39     .04       0
#XS Ineff= 4 ,-1
       0     500      48     500  586.51   43.82  631.39     726   43.82
     726  941.89      48
Permanent Ineff=
       F       F       F       F
Bank Sta=591.51,626.39
XS Rating Curve= 0 ,0
Exp/Cntr=0.5,0.3

Type RM Length L Ch R = 2 ,2332    ,,,
BEGIN DESCRIPTION:
Dirt Road off (SR 1247)
END DESCRIPTION:
Bridge Culvert--1,0,-1,-1, 0
Deck Dist Width WeirC Skew NumUp NumDn MinLoCord MaxHiCord MaxSubmerge Is_Ogee
22,12,2.6,0, 145, 145, , , 0.95, 0, 0,0,,
       0    5.26    6.26   18.48   19.12   21.46   29.88   46.69   49.13    50.8
    61.2   62.14   71.53   76.25   83.98   86.99   98.83  104.17  109.68  112.08
  116.78  128.86  129.12  140.33  140.84     141  141.16  150.45  152.52  159.56
  165.68  168.14  170.54  178.12  181.48  189.95  192.64  200.62  206.11  214.78
  216.77   219.9  221.27   222.7  232.62  242.27  246.06  254.29  261.33  266.75
  269.46  275.64  281.99  290.22  294.98  300.52  308.71  312.07  317.23  325.19
  334.72  336.41  341.88  345.18   346.2  354.01  364.86  367.32  368.46  381.45
  391.43  394.89  402.28   404.9  416.94  419.22     428  437.12  439.41  448.25
   448.5  448.56   448.8  466.78  472.29  478.51  485.16  487.55  492.84  496.95
  512.47  514.86  516.96  523.17  527.44  528.76  537.21  537.25  537.25  537.29
  554.31  563.75  650.99  659.18  758.86  759.27  759.76  773.04  781.37  781.93
  783.71  786.74  796.08  801.86  804.41     815  819.55  821.58  826.76   839.2
  841.12  844.49  849.01  851.35  854.97  861.11  871.16  871.54   871.7  881.12
  887.95  889.47  894.16  896.33  902.04  907.26  916.94  920.26  923.66  926.82
  939.63  944.01  945.12  946.21  961.74
   45.98   45.83   45.79   45.38   45.36   45.26   44.96   44.67   44.62   44.59
   44.22    44.2   44.22   44.14   44.05   44.01   44.02   44.04   44.05   44.06
   44.03   43.86   43.87   44.03   44.03   44.03   44.03   43.81   43.84   43.86
   43.93   43.94   43.94   44.06   44.09   44.11   44.19   44.22   44.26   44.42
   44.44   44.49   44.51   44.52   44.69   44.66   44.76   44.92   44.87   44.79
   44.76   44.76   44.78   44.74   44.71   44.72   44.86   44.83   44.76   44.52
   44.64   44.67   44.66   44.66   44.65   44.66   44.55   44.53   44.54   44.64
   44.69    44.7   44.89    44.9   44.86   44.87   44.77   44.86   44.86    44.9
    44.9    44.9    44.9   44.77   44.73   44.71   44.76   44.76   44.68   44.67
   44.33   44.28   44.26   44.21   44.19   44.19   44.02   44.02   44.02   44.02
   43.87   43.79   43.82   44.02   43.89   43.91   43.91   43.99   43.95   43.95
   43.91   43.95   44.05   44.16   44.09    44.5   44.82    44.9   45.11   45.96
    46.2   46.11   45.64   45.68   45.75   45.78   46.96   46.98      47   46.45
   46.21   46.17      46   45.83   46.09   46.08   46.25   46.45    46.6   46.66
   46.76   47.06   47.08   47.09   47.13
                                                                                
                                                                                
                                                                                
                                                                                
                                                                                
                                                                                
                                                                                
                                                                                
                                                                                
                                                                                
                                                                                
                                                                                
                                                                                
                                                                                
                                        
       0    5.26    6.26   18.48   19.12   21.46   29.88   46.69   49.13    50.8
    61.2   62.14   71.53   76.25   83.98   86.99   98.83  104.17  109.68  112.08
  116.78  128.86  129.12  140.33  140.84     141  141.16  150.45  152.52  159.56
  165.68  168.14  170.54  178.12  181.48  189.95  192.64  200.62  206.11  214.78
  216.77   219.9  221.27   222.7  232.62  242.27  246.06  254.29  261.33  266.75
  269.46  275.64  281.99  290.22  294.98  300.52  308.71  312.07  317.23  325.19
  334.72  336.41  341.88  345.18   346.2  354.01  364.86  367.32  368.46  381.45
  391.43  394.89  402.28   404.9  416.94  419.22     428  437.12  439.41  448.25
   448.5  448.56   448.8  466.78  472.29  478.51  485.16  487.55  492.84  496.95
  512.47  514.86  516.96  523.17  527.44  528.76  537.21  537.25  537.25  537.29
  554.31  563.75  650.99  659.18  758.86  759.27  759.76  773.04  781.37  781.93
  783.71  786.74  796.08  801.86  804.41     815  819.55  821.58  826.76   839.2
  841.12  844.49  849.01  851.35  854.97  861.11  871.16  871.54   871.7  881.12
  887.95  889.47  894.16  896.33  902.04  907.26  916.94  920.26  923.66  926.82
  939.63  944.01  945.12  946.21  961.74
   45.98   45.83   45.79   45.38   45.36   45.26   44.96   44.67   44.62   44.59
   44.22    44.2   44.22   44.14   44.05   44.01   44.02   44.04   44.05   44.06
   44.03   43.86   43.87   44.03   44.03   44.03   44.03   43.81   43.84   43.86
   43.93   43.94   43.94   44.06   44.09   44.11   44.19   44.22   44.26   44.42
   44.44   44.49   44.51   44.52   44.69   44.66   44.76   44.92   44.87   44.79
   44.76   44.76   44.78   44.74   44.71   44.72   44.86   44.83   44.76   44.52
   44.64   44.67   44.66   44.66   44.65   44.66   44.55   44.53   44.54   44.64
   44.69    44.7   44.89    44.9   44.86   44.87   44.77   44.86   44.86    44.9
    44.9    44.9    44.9   44.77   44.73   44.71   44.76   44.76   44.68   44.67
   44.33   44.28   44.26   44.21   44.19   44.19   44.02   44.02   44.02   44.02
   43.87   43.79   43.82   44.02   43.89   43.91   43.91   43.99   43.95   43.95
   43.91   43.95   44.05   44.16   44.09    44.5   44.82    44.9   45.11   45.96
    46.2   46.11   45.64   45.68   45.75   45.78   46.96   46.98      47   46.45
   46.21   46.17      46   45.83   46.09   46.08   46.25   46.45    46.6   46.66
   46.76   47.06   47.08   47.09   47.13
                                                                                
                                                                                
                                                                                
                                                                                
                                                                                
                                                                                
                                                                                
                                                                                
                                                                                
                                                                                
                                                                                
                                                                                
                                                                                
                                                                                
                                        
BR Coef=-1 , 1 , 0 ,1.25, 0 ,,,0.8,0,2,0,
WSPro=,,,, 1 ,,,, 0 ,,,, 0 ,,,,-1 ,-1 ,-1 , 0 , 0 , 0 , 0 , 0
Culvert=1,4.5,,25,0.024,0.9,1,2,3,38.5,609,38.4,694,Culvert #1  , 0 ,14
Culvert Bottom n=0.024
BC Design=,, 0 ,, 0 ,,,,,,
BC Use User HTab Curves=0
BC User HTab FreeFlow(D)= 0

Type RM Length L Ch R = 1 ,2306    ,197.99,38.15,13.11
XS GIS Cut Line= 6
 2391875.6729305  629167.1491335 2391861.0708765  629061.5650514
 2391816.1414799  628972.8294929 2391434.2416082  628745.9360398
 2391264.6331358  628787.4957317 2391096.4042951  628891.7038656
#Sta/Elev= 30
       0   45.96    63.4   44.13  110.34   43.99  126.33   44.18  155.76   44.02
  195.67   44.56  220.15   44.48   269.6   45.19  395.91   44.73   436.8   45.17
   465.3   45.13  500.79   44.79  613.83   42.98  643.84    43.6   672.2   43.31
  678.44    42.2   695.1   37.78  700.29   38.98  711.75   42.21  717.75   43.54
   786.5   43.22  802.22   43.69  823.89   44.77   841.2    44.9  857.16   46.45
  880.44   45.26  897.38   45.43   917.4   45.21  970.14   46.64 1026.07    47.3
#Mann= 3 , 0 , 0
       0     .04       0  678.44     .05       0  711.75     .04       0
#XS Ineff= 3 ,-1
       0     600      47     600  668.44   43.33  721.75     800    43.4
Permanent Ineff=
       F       F       F
Bank Sta=678.44,711.75
XS Rating Curve= 0 ,0
Exp/Cntr=0.5,0.3

Type RM Length L Ch R = 1 ,2268    ,111.77,91.83,53.85
XS GIS Cut Line= 6
 2391781.4678817  628501.9198194 2391652.2958663  628543.4795113
 2391452.3600512  628659.1727077  2391319.371249  628761.8012177
 2391187.2472077  628815.1875377 2391084.6006577  628882.4780538
#Sta/Elev= 30
       0   47.67   22.21   47.98    44.7    47.6   67.21   48.18   89.68   47.54
  134.94   47.62  145.45   48.41  159.14   48.17     177   49.61  193.08    47.6
  252.17   46.65  277.89   45.13  298.18   45.63  353.57   44.35  418.86   42.08
  447.35   40.05  456.98   36.16  469.33   37.16  471.99   40.23  475.42   41.49
  484.37   43.18  491.77   43.31  506.89   41.52  530.19   43.23  570.03   43.86
   599.1   45.47  622.28   45.88   645.4   44.32  740.97   46.76  799.98   47.57
#Mann= 3 ,-1 , 0
       0     .05       0  447.35     .04       0  471.99     .04       0
#XS Ineff= 3 ,-1
       0  442.35   43.98  476.99  530.19    43.9  530.19  799.98      48
Permanent Ineff=
       F       F       F
Bank Sta=447.35,471.99
XS Rating Curve= 0 ,0
Exp/Cntr=0.5,0.3

Type RM Length L Ch R = 2 ,2230    ,,,
BEGIN DESCRIPTION:
Beaman Old Creek Rd (SR 1247)
END DESCRIPTION:
Bridge Culvert--1,0,-1,-1, 0
Deck Dist Width WeirC Skew NumUp NumDn MinLoCord MaxHiCord MaxSubmerge Is_Ogee
30,22,2.6,0, 83, 89, , , 0.95, 0, 0,0,,
       0   16.51   18.04   19.08   39.25   40.39   41.18   62.14   62.89   63.43
   83.11   84.64   85.18   85.65  105.08   107.4  109.49  125.56   129.6  133.29
   145.9  151.61  157.08  166.58  170.48  173.92  182.85  184.74   195.8  203.87
  207.13  209.43  217.77   223.2  230.58  235.71  239.87  242.58  248.52  258.03
  261.42  264.82  281.64  289.01  302.08  304.51  315.28  322.58  325.65  577.19
  577.38  588.96  595.42  599.59   611.7  611.86  618.11  622.43  634.53  640.45
  645.82  657.58  662.89  669.23  680.54  685.37  692.42  692.73  703.26  705.55
  717.99  726.34  744.92  749.87  752.12  762.37  764.63   774.2  778.47  783.94
  795.05  798.34  799.45
   47.34   47.43   47.47   47.42   47.42   47.45   47.41    47.2   47.21   47.19
   47.17   47.16   47.18   47.15   47.02   47.06   46.98   46.86   46.94   46.84
   46.74    46.8   46.75   46.67   46.66   46.64   46.43   46.43   46.65   46.33
   46.26   46.15   46.02   46.01   46.16   45.76    45.7   45.83   45.76   45.59
   45.56   45.54   45.41   45.57   45.51   45.42   45.27   45.21      44      44
      44      44   44.32   43.96   44.02   44.02   43.81   43.73   43.96   44.15
   44.34   44.68   44.79    44.9   45.17   45.33   45.57   45.58   45.84   45.94
   46.24   46.44   46.66   46.72   46.74   46.83   46.85   46.97   47.09   47.22
   47.43   47.51   47.52
                                                                                
                                                                                
                                                                                
                                                                                
                                                                                
                                                                                
                                                                                
                                                                                
                        
    -100  -83.49  -81.96  -80.92  -60.75  -59.61  -58.82  -37.86  -37.11  -36.57
  -16.89  -15.36  -14.82  -14.35    5.08     7.4    9.49   25.56    29.6   33.29
    45.9   51.61   57.08   66.58   70.48   73.92   82.85   84.74    95.8  103.87
  107.13  109.43  117.77   123.2  130.58  135.71  139.87  142.58  148.52  158.03
  161.42  164.82  181.64  189.01  202.08  204.51  215.28  222.58  225.65   239.8
  242.96  247.36  259.86  268.67   276.1  477.19  477.38  488.96  495.42  499.59
   511.7  511.86  518.11  522.43  534.53  540.45  545.82  557.58  562.89  569.23
  580.54  585.37  592.42  592.73  603.26  605.55  617.99  626.34  644.92  649.87
  652.12  662.37  664.63   674.2  678.47  683.94  695.05  698.34  699.45
   47.34   47.43   47.47   47.42   47.42   47.45   47.41    47.2   47.21   47.19
   47.17   47.16   47.18   47.15   47.02   47.06   46.98   46.86   46.94   46.84
   46.74    46.8   46.75   46.67   46.66   46.64   46.43   46.43   46.65   46.33
   46.26   46.15   46.02   46.01   46.16   45.76    45.7   45.83   45.76   45.59
   45.56   45.54   45.41   45.57   45.51   45.42   45.27   45.21   45.52    45.3
   45.25   45.27   45.08   45.07      44      44      44      44   44.32   43.96
   44.02   44.02   43.81   43.73   43.96   44.15   44.34   44.68   44.79    44.9
   45.17   45.33   45.57   45.58   45.84   45.94   46.24   46.44   46.66   46.72
   46.74   46.83   46.85   46.97   47.09   47.22   47.43   47.51   47.52
                                                                                
                                                                                
                                                                                
                                                                                
                                                                                
                                                                                
                                                                                
                                                                                
                                                                        
BR Coef=-1 , 1 , 0 ,1.25, 0 ,,,0.8,0,2,0,
WSPro=,,,, 1 ,,,, 0 ,,,, 0 ,,,,-1 ,-1 ,-1 , 0 , 0 , 0 , 0 , 0
Culvert=1,6,,70,0.024,0.9,1,2,3,36.21,459.22,36.11,393.73,Culvert #1  , 0 ,8
Culvert Bottom n=0.024
BC Design=,, 0 ,, 0 ,,,,,,
BC Use User HTab Curves=0
BC User HTab FreeFlow(D)= 0

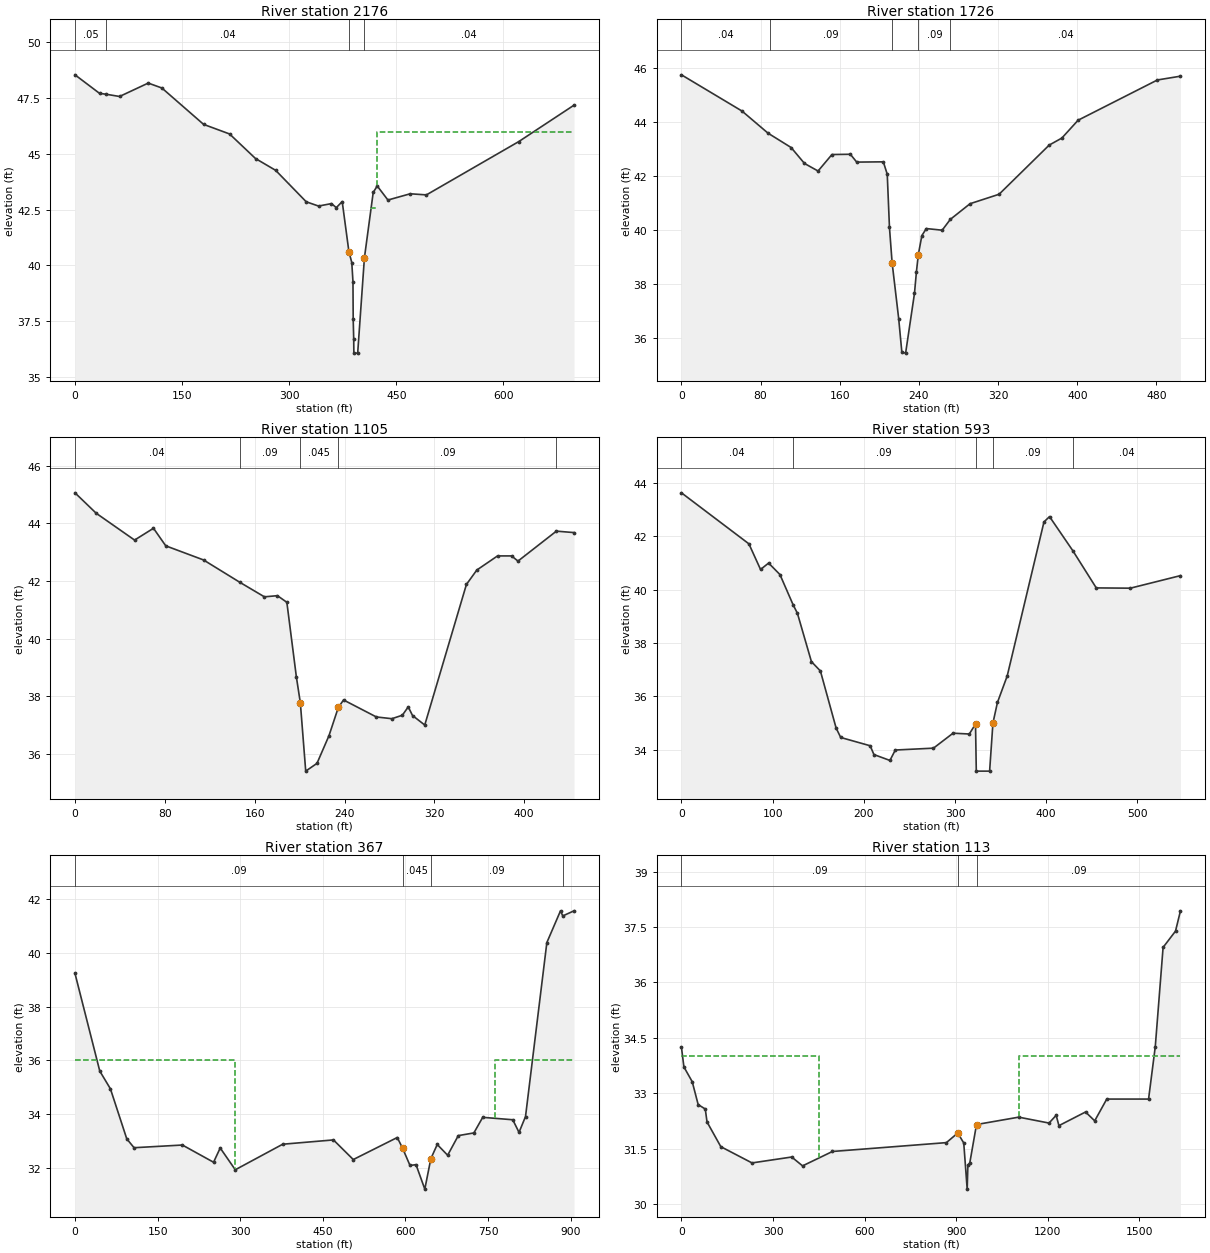
Type RM Length L Ch R = 1 ,2176    ,276.19,449.72,485.63
XS GIS Cut Line= 6
 2391589.9016591  628436.3503527 2391483.1943419  628494.7585684
 2391373.1173201  628598.0961807 2391246.1917746  628738.5005453
 2391122.6359337  628784.5531769 2391036.1468452  628844.0846274
#Sta/Elev= 30
       0   48.54   34.36   47.71    43.6   47.67   62.42   47.57  102.56   48.17
  121.65   47.95  180.08   46.32  216.48   45.89  252.78   44.79     281   44.26
  323.83   42.85  341.06   42.66  359.12   42.77  365.93   42.59  374.19   42.86
  383.55   40.62  387.59   40.13  389.25   39.27  389.58   37.58  390.28   36.71
  390.51   36.07  395.85   36.07  405.28   40.34   417.6   43.27  423.23   43.56
   438.2   42.93  469.39   43.21  492.09   43.16  621.48   45.55  698.76   47.18
#Mann= 4 ,-1 , 0
       0     .05       0    43.6     .04       0  383.55    .045       0
  405.28     .04       0
#XS Ineff= 3 ,-1
       0  374.03   42.57  414.55  423.23   42.57  423.23  698.76      46
Permanent Ineff=
       F       F       F
Bank Sta=383.55,405.28
XS Rating Curve= 0 ,0
Exp/Cntr=0.5,0.3

Type RM Length L Ch R = 1 ,1726    ,414.68,621.02,461.18
XS GIS Cut Line= 4
 2391225.1178224  628466.5787867 2391097.4587333  628436.2867994
  2390939.507657  628382.1939651 2390733.9548864  628397.3399587
#Sta/Elev= 30
       0   45.75   61.16   44.41   87.51   43.59   110.8   43.06  124.33   42.47
  138.04   42.19  152.07    42.8  170.67   42.81  177.11   42.52     204   42.53
  207.96   42.07   210.2    40.1  212.86    38.8  219.51   36.73   222.7   35.49
  226.52   35.45  235.48   37.66  237.47   38.47  239.38    39.1  242.94    39.8
  247.45   40.06  263.47      40   271.7    40.4  291.66   40.98  320.99   41.33
  371.62   43.15  384.42   43.41  400.83   44.07     481   45.56  504.27    45.7
#Mann= 5 ,-1 , 0
       0     .04       0   89.76     .09       0  212.86    .045       0
  239.38     .09       0   271.7     .04       0
Bank Sta=212.86,239.38
XS Rating Curve= 0 ,0
Exp/Cntr=0.3,0.1

Type RM Length L Ch R = 1 ,1105    ,489.33,512.47,425.49
XS GIS Cut Line= 4
 2391569.1482489  628250.2074492 2391441.4891598  628144.1854939
 2391335.4672045  628096.5837997 2391177.5161281  628059.8006723
#Sta/Elev= 30
       0   45.06   18.92   44.35   53.06   43.42    69.9   43.83   80.82   43.22
  114.46   42.73  146.54   41.96  168.65   41.45  180.28   41.49  188.65   41.26
  197.13   38.67  200.67   37.77  205.45    35.4  215.49   35.67  226.16   36.63
  234.48   37.61  239.14   37.87  268.37   37.28  282.16   37.22  291.48   37.34
  296.75   37.63  300.56   37.33  311.44      37  348.55   41.88  357.81   42.38
  376.25   42.87  388.78   42.87  394.45   42.69  428.65   43.73  444.34   43.68
#Mann= 5 ,-1 , 0
       0     .04       0  146.54     .09       0  200.67    .045       0
  234.48     .09       0  428.65     .04       0
Bank Sta=200.67,234.48
XS Rating Curve= 0 ,0
Exp/Cntr=0.3,0.1

Type RM Length L Ch R = 1 ,593     ,256.24,226.14,156.63
XS GIS Cut Line= 6
 2391885.0504015  627895.3584559 2391770.3735927   627780.681647
 2391670.8427775  627735.2436662 2391541.0199751  627726.5888127
 2391493.4182808  627724.4250993 2391400.3786057  627754.7170865
#Sta/Elev= 30
       0   43.62   73.96   41.71   86.73   40.75   95.58   40.99     108   40.56
  122.41   39.43  127.15   39.11  142.51    37.3  152.36   36.95  169.62   34.81
  174.65   34.46  206.93   34.15  211.06   33.82   228.6    33.6   234.5   33.99
  276.35   34.06  297.81   34.62  315.65   34.59  322.46  34.963  323.31    33.2
  337.92    33.2  341.56      35  346.49   35.77  357.18   36.76  397.52   42.53
  403.61   42.73  429.22   41.45  454.87   40.06  492.26   40.05   547.2   40.52
#Mann= 5 ,-1 , 0
       0     .04       0  122.41     .09       0  322.46    .045       0
  341.56     .09       0  429.22     .04       0
Bank Sta=322.46,341.56
XS Rating Curve= 0 ,0
Exp/Cntr=0.3,0.1

Type RM Length L Ch R = 1 ,367     ,250.77,253.96,250.3
XS GIS Cut Line= 6
 2392187.9702739  627785.0090738 2392040.8377645  627596.7660102
 2391766.0461659  627521.0360421 2391655.6967838  627527.5271822
 2391547.5111151  627570.8014497  2391430.670593  627672.4959783
#Sta/Elev= 30
       0   39.23   45.02    35.6   64.34   34.94   94.02   33.08  107.28   32.75
  195.02   32.85  251.64   32.21  263.71   32.74  291.09   31.93  377.17   32.88
  469.34   33.04  505.35   32.31  585.24   33.13  594.89  32.731  608.36   32.09
  619.26   32.12  635.24   31.21  646.18   32.34  657.82   32.87  676.71   32.47
  696.04    33.2  724.35    33.3   740.4   33.88  794.97   33.79  806.34   33.32
  818.13   33.91  856.87   40.38  881.66   41.56  885.77   41.37  906.16   41.56
#Mann= 4 ,-1 , 0
       0     .09       0  594.89    .045       0  646.18     .09       0
  885.77     .04       0
#XS Ineff= 2 , 0
       0     290      36     762       0      36
Permanent Ineff=
       F       F
Bank Sta=594.89,646.18
XS Rating Curve= 0 ,0
Exp/Cntr=0.3,0.1

Type RM Length L Ch R = 1 ,113     ,52.37,112.74,106.89
XS GIS Cut Line= 6
 2392449.7795923  627674.6596917 2392110.0765925  627384.7220995
 2391792.0107265  627263.5541506 2391649.2056437  627278.7001442
 2391270.5558033  627432.3237938 2391017.4013384    627583.78373
#Sta/Elev= 30
       0   34.24    8.06   33.71   35.28   33.31   54.74   32.69   78.03   32.57
   83.71   32.22  128.89   31.55  231.06   31.11  361.02   31.27  396.64   31.03
  494.43   31.42  867.68   31.66  904.85   31.92  924.48   31.65  935.72    30.4
  938.06   31.05  944.28   31.11  966.25   32.15 1104.67   32.35 1203.77   32.19
 1227.14    32.4 1236.16   32.12 1323.34   32.49 1353.34   32.25 1392.82   32.84
 1529.77   32.84 1551.72   34.26 1577.32   36.95 1617.96   37.39 1634.21   37.94
#Mann= 3 , 0 , 0
       0     .09       0  904.85    .045       0  966.25     .09       0
#XS Ineff= 2 , 0
       0     450      34    1105       0      34
Permanent Ineff=
       F       F
Bank Sta=904.85,966.25
XS Rating Curve= 0 ,0
Exp/Cntr=0.3,0.1
Stream Node=Contentnea      ,Trib9           , 0 , 0 ,Upstream end
Stream Node=Contentnea      ,Trib9           , 0 , 1 ,Downstream end

Chan Stop Cuts=-1
Use User Specified Reach Order=0
User Specified Reach Order=Contentnea      ,Trib9