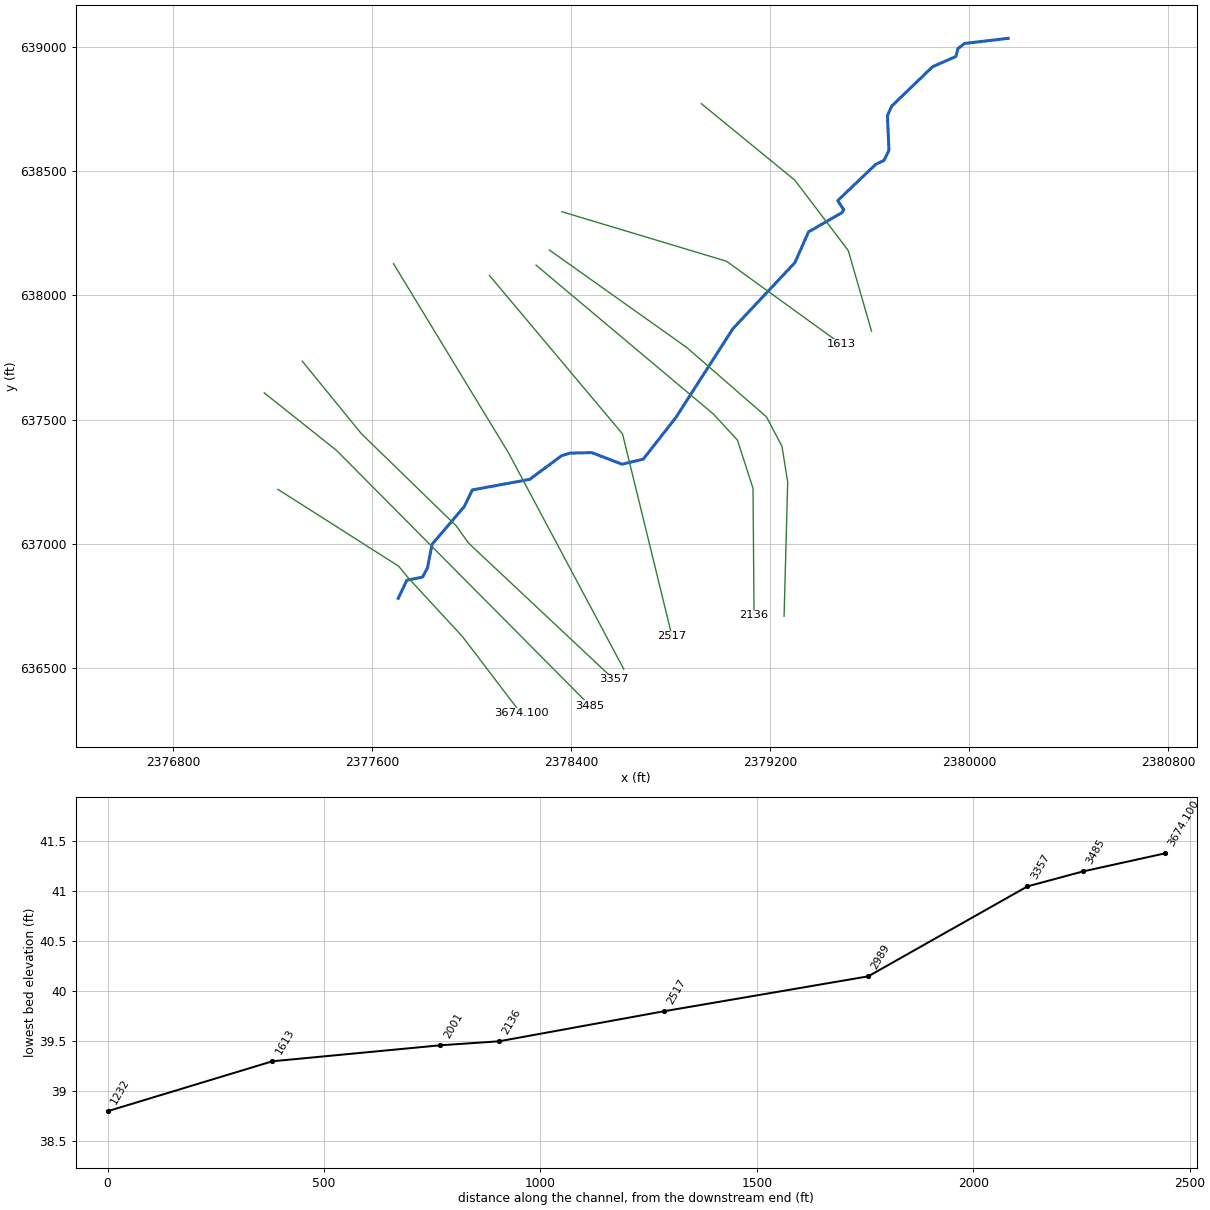
--- lds_fort_run_lower.prj (project) ---

Proj Title=Fort Run (Lower)
Current Plan=p01
Default Exp/Contr=0.3,0.1
English Units
Geom File=g01
Flow File=f01
Flow File=f02
Plan File=p01
Plan File=p02
Y Axis Title=Elevation
X Axis Title(PF)=Main Channel Distance
X Axis Title(XS)=Station
BEGIN DESCRIPTION:
END DESCRIPTION:
DSS Export Rating Curves= 0
DSS Export Rating Curve Sorted= 0
DSS Export Volume Flow Curves= 0
DXF OffsetX= 0
DXF OffsetY= 0
DXF ScaleX= 1
DXF ScaleY= 10

--- lds_fort_run_lower.p01 (plan) ---

Plan Title=100 Year Single
Program Version=4.00
Short Identifier=Plan01
Geom File=g01
Flow File=f01
Subcritical Flow
K Sum by GR= 0
Std Step Tol= 0.01
Critical Tol= 0.01
Num of Std Step Trials= 20
Max Error Tol= 0.3
Flow Tol Ratio= 0.001
Split Flow NTrial= 30
Split Flow Tol= 0.02
Split Flow Ratio= 0.02
Log Output Level= 0
Friction Slope Method= 1
Unsteady Friction Slope Method= 2
Unsteady Bridges Friction Slope Method= 1
Parabolic Critical Depth
Global Vel Dist= 0 , 0 , 0
Global Log Level= 0
CheckData=True
Encroach Param=-1 ,10,10, 2
Encroach River=Fort Run
Encroach Reach=Reach - 1
Encroach Node=3674.100
       1    4790    5105
Encroach Node=3485
       1  4819.5  5021.5
Encroach Node=3357
       1  4819.5  5021.5
Encroach Node=2989
       4      .7
Encroach Node=2517
       1    4805    5040
Encroach Node=2136
       1    4600    4900
Encroach Node=2001
       4      .7
Encroach Node=1613
       4      .7
Encroach Node=1232
       4      .7
Computation Interval=1HOUR
Output Interval=1HOUR
Run HTab= 0
Run UNet= 0
Run PostProcess= 0
Run WQNet= 0
UNET Theta= 1
UNET Theta Warmup= 1
UNET ZTol= 0.02
UNET ZSATol= 0.05
UNET MxIter= 20
UNET MaxInSteps= 0
UNET DtIC= 0
UNET DtMin= 0
UNET MaxCRTS= 20
UNET WFStab= 2
UNET SFStab= 1
UNET WFX= 1
UNET SFX= 1
UNET DSS MLevel= 4
UNET DZMax Abort= 100
UNET Convert EG Bridges= 0
UNET Use Existing IB Tables=-1
UNET Froude Reduction=False
UNET Froude Limit= 1
UNET Froude Power= 10
UNET Time Slicing=0,0, 5
Instantaneous Interval=1HOUR
Write IC File= 0
Echo Input=False
Echo Output=False
Write Detailed= 0
Detailed Automatic Start=False, 10
WQ ULTIMATE=-1
WQ Max Comp Step=1HOUR
WQ Output Interval=15MIN
WQ Output Selected Increments= 0
WQ Output face flow=0
WQ Output face velocity=0
WQ Output face area=0
WQ Output face dispersion=0
WQ Output cell volume=0
WQ Output cell surface area=0
WQ Output cell continuity=0
WQ Output face conc=0
WQ Output face dconc_dx=0
WQ Output face courant=0
WQ Output face peclet=0
WQ Output face adv mass=0
WQ Output face disp mass=0
WQ Output cell mass=0
WQ Output cell source sink temp=0
WQ Output cell source sink nsm=0
WQ Output MaxMinRange=-1
WQ Daily Max Min Mean=-1
WQ Daily Range=0
WQ Daily Time=0
WQ Create Restart=0
WQ Fixed Restart=0
WQ System Summary=False
Sorting and Armoring Iterations= 10
XS Update Threshold= 0.02
Hydraulics Update Threshold= 0.02
Energy Slope Method= 1
Volume Change Method= 0
XS Weighting Method= 0
Number of US Weighted Cross Sections= 1
Number of DS Weighted Cross Sections= 1
Upstream XS Weight=0.25
Main XS Weight=0.5
Downstream XS Weight=0.25
Number of DS XS's Weighted with US Boundary= 1
Upstream Boundary Weight= 1
Weight of XSs Associated with US Boundary= 0
Number of US XS's Weighted with DS Boundary= 1
Downstream Boundary Weight= 0.5
Weight of XSs Associated with DS Boundary= 0.5
Sediment Output Level= 4
Mass or Volume Output= 0
Output Increment Type= 1
Profile and TS Output Increment= 10
XS Output Flag= 0
XS Output Increment= 10
Disregard all LS=0
Disregard all Conn=0
Disregard all Breaches=0
Disregard all Pumps=0

--- lds_fort_run_lower.p02 (plan) ---

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Plan Title=Multi-Profile
Short Identifier=Multi
Geom File=g01
Flow File=f01

--- lds_fort_run_lower.f01 (steady flow) ---

Flow Title=100 Year Single
Program Version=4.00
Number of Profiles= 7
Profile Names=10 YR,25 YR,50 YR,500 YR,100 YR - 10%,100 YR - 20%,100 YR - 35%
River Rch & RM=Fort Run,Reach - 1       ,3674.100
     812    1152    1455    2787    3041    3898    4763
Boundary for River Rch & Prof#=Fort Run,Reach - 1       , 1
Up Type= 0
Dn Type= 3
Dn Slope=0.003
Boundary for River Rch & Prof#=Fort Run,Reach - 1       , 2
Up Type= 0
Dn Type= 3
Dn Slope=0.003
DSS Import GetInterval= 0
DSS Import GetPeak= 0
DSS Import FillOption= 0

--- lds_fort_run_lower.f02 (steady flow) ---

Flow Title=Muilti-Profile
Program Version=4.00
Number of Profiles= 7
Profile Names=10 YR,25 YR,50 YR,500 YR,100 YR - 10%,100 YR - 20%,100 YR - 35%
River Rch & RM=Fort Run,Reach - 1       ,3674.100
     812    1152    1455    2787    3041    3898    4763
Boundary for River Rch & Prof#=Fort Run,Reach - 1       , 1
Up Type= 0
Dn Type= 3
Dn Slope=0.003
Boundary for River Rch & Prof#=Fort Run,Reach - 1       , 2
Up Type= 0
Dn Type= 3
Dn Slope=0.003
Boundary for River Rch & Prof#=Fort Run,Reach - 1       , 3
Up Type= 0
Dn Type= 3
Dn Slope=0.003
Boundary for River Rch & Prof#=Fort Run,Reach - 1       , 4
Up Type= 0
Dn Type= 3
Dn Slope=0.003
Boundary for River Rch & Prof#=Fort Run,Reach - 1       , 5
Up Type= 0
Dn Type= 3
Dn Slope=0.003
Boundary for River Rch & Prof#=Fort Run,Reach - 1       , 6
Up Type= 0
Dn Type= 3
Dn Slope=0.003
Boundary for River Rch & Prof#=Fort Run,Reach - 1       , 7
Up Type= 0
Dn Type= 3
Dn Slope=0.003
DSS Import GetInterval= 0
DSS Import GetPeak= 0
DSS Import FillOption= 0

--- lds_fort_run_lower.g01 (geometry) ---

Geom Title=Fort Run (Lower) Geometry
Program Version=4.00

River Reach=Fort Run        ,Reach - 1
Reach XY= 30
2377704.25012207 636781.625122072377738.75012207 636854.62512207
2377801.50012207 636866.750122072377821.75012207 636903.25012207
2377840.00012207636998.5631103522377969.75012207637150.563110352
2378002.25012207637217.4381103522378233.25012207 637260.00012207
2378361.00012207 637355.250122072378395.50012207637365.438110352
2378482.75012207637367.4381103522378604.25012207637320.813110352
2378689.50012207637341.0631103522378821.25012207637509.313110352
2379050.25012207637866.0631103522379299.50012207 638131.62512207
2379354.25012207 638255.250122072379488.00012207 638332.25012207
2379496.25012207638344.4381103522379471.75012207638380.938110352
2379625.00012207638527.4381103522379657.25012207 638542.12512207
2379677.75012207638583.0631103522379671.75012207 638723.50012207
2379689.25012207638761.5631103522379853.25012207638919.563110352
2379946.75012207638960.5631103522379955.50012207 638992.75012207
2379982.00012207639013.1881103522380157.00012207 639033.75012207

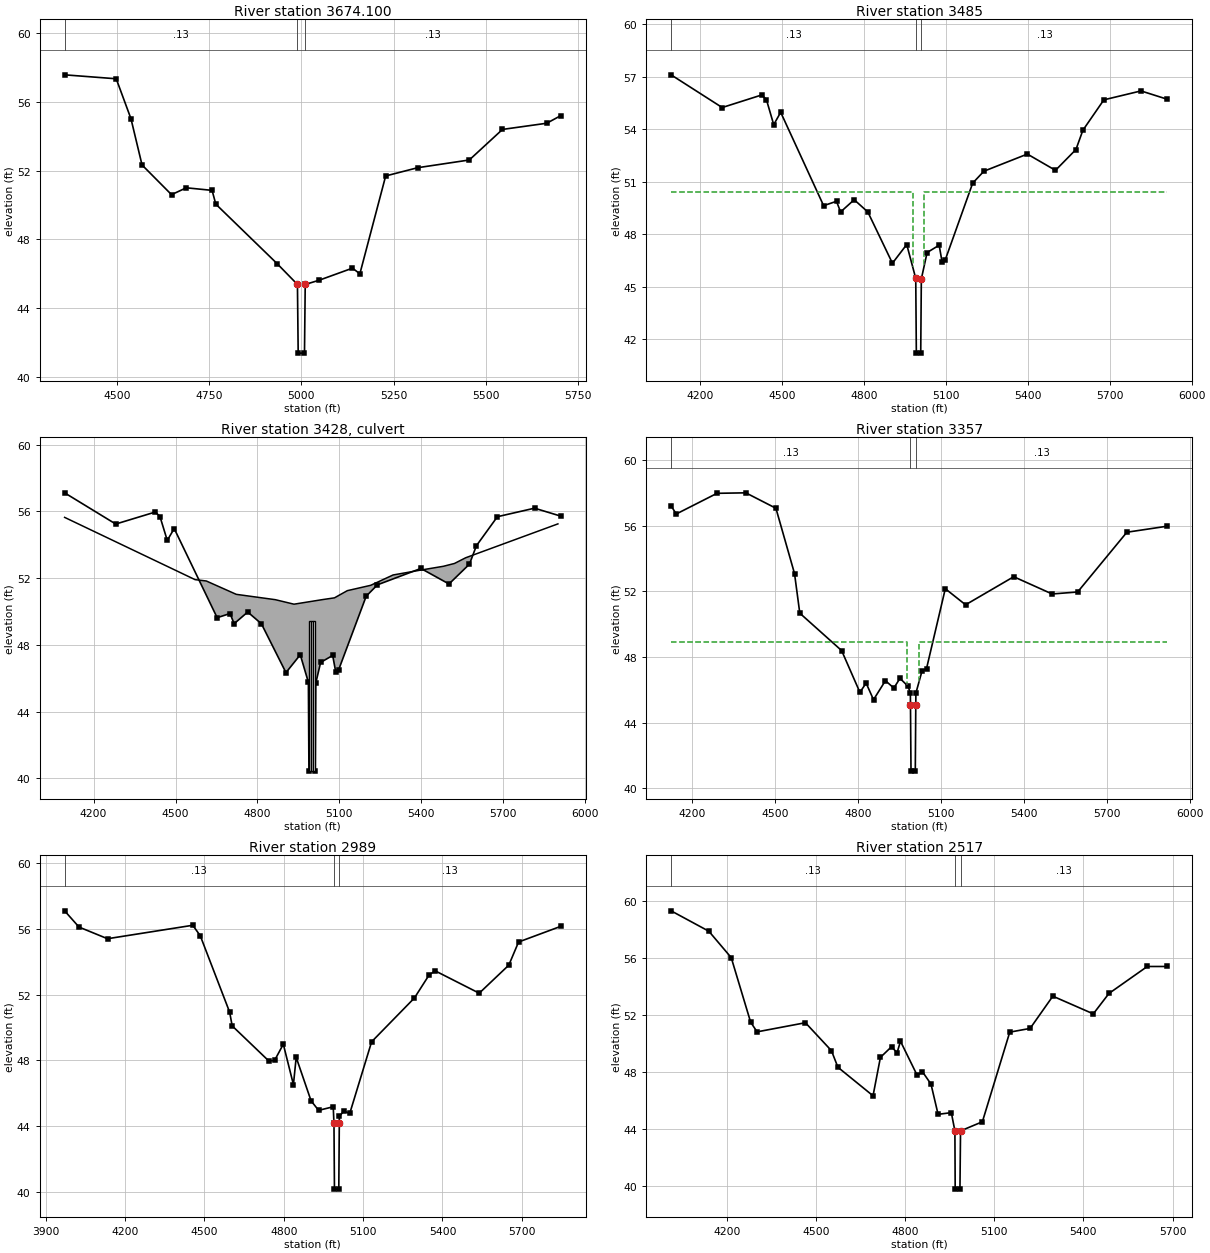
Type RM Length L Ch R = 1 ,3674.100,162.63,188.66,166.56
XS GIS Cut Line= 5
  2377220.046875637219.8803100592377705.96368408636910.661499023
2377747.19268799636860.598876953  2377962.171875636627.947875977
2378197.77087402636318.729309082
#Sta/Elev= 22
  4357.9   57.59  4497.9   57.36  4537.9   55.03  4567.9   52.34  4647.9   50.61
  4687.9   51.01  4757.9   50.86  4767.9   50.06  4933.9    46.6  4989.4   45.38
  4991.4   41.38  5008.5   41.38  5010.5   45.38  5048.7   45.63  5138.7   46.33
  5158.7      46  5228.7    51.7  5315.5   52.18  5455.5   52.63  5545.5   54.41
  5665.5   54.77  5704.2   55.22
#Mann= 3 ,-1 , 0
  4357.9     .13       0  4989.4    .044       0  5010.5     .13       0
Bank Sta=4989.4,5010.5
XS Rating Curve= 0 ,0
Exp/Cntr=0.5,0.3

Type RM Length L Ch R = 1 ,3485    ,126.27,128.62,134.07
XS GIS Cut Line= 3
2377165.12030029637607.7315063482377454.72167969637377.489318848
2378474.62207031636350.393920898
#Sta/Elev= 30
 4093.95   57.11 4281.12   55.24 4426.05   55.96 4443.07   55.69 4469.77   54.26
 4495.23   54.97 4652.46   49.63 4699.64   49.88  4714.6   49.27 4764.35   49.97
 4814.34   49.27  4904.4   46.34 4956.78   47.41 4989.78   45.47 4991.94    41.2
    5008    41.2 5010.23   45.44 5031.33   46.95 5075.43   47.37 5086.49   46.39
 5097.09    46.5 5198.25   50.92 5239.32    51.6 5398.38   52.58 5501.33   51.65
 5576.32   52.84 5601.64   53.94 5678.52   55.68 5814.52   56.19 5911.38   55.71
#Mann= 3 ,-1 , 0
 4093.95     .13       0 4989.78    .044       0 5010.23     .13       0
#XS Ineff= 2 , 0
       0  4978.5   50.44  5021.5       0   50.44
Permanent Ineff=
       F       F
Bank Sta=4989.78,5010.23
XS Rating Curve= 0 ,0
Exp/Cntr=0.5,0.3

Type RM Length L Ch R = 2 ,3428    ,,,
Bridge Culvert--1,0,-1,-1, 0
Deck Dist Width WeirC Skew NumUp NumDn MinLoCord MaxHiCord MaxSubmerge Is_Ogee
38,32,2.6,0, 16, 16, , , 0.98, 0, 0,0,,
 4093.95  4571.6 4612.67 4722.44 4865.41  4933.8 5036.46 5081.97 5129.01 5214.53
 5296.59 5404.14 5480.78  5521.5 5562.29 5900.12
   55.64   51.91   51.83   51.03   50.71   50.44   50.71   50.82   51.25   51.57
   52.19    52.5   52.71   52.88   53.22   55.25
                                                                                
                                                
 4093.95  4571.6 4612.67 4722.44 4865.41  4933.8 5036.46 5081.97 5129.01 5214.53
 5296.59 5404.14 5480.78  5521.5 5562.29 5900.12
   55.64   51.91   51.83   51.03   50.71   50.44   50.71   50.82   51.25   51.57
   52.19    52.5   52.71   52.88   53.22   55.25
                                                                                
                                                
BR Coef=-1 , 0 , 0 ,, 0 ,,,0.8,-1,,0,
WSPro=,,,, 1 ,,,, 0 ,,,, 0 ,,,,-1 ,-1 ,-1 , 0 , 0 , 0 , 0 , 0
Multiple Barrel Culv=2,9,7,49,0.012,0.4,1,8,1,40.44,39.94, 3,Culvert #1  , 0 ,29
    4992    4992    5000    5000    5008    5008
Culvert Bottom n=0.012
BR U #Sta/Elev= 30
 4093.95   57.11 4281.12   55.24 4426.05   55.96 4443.07   55.69 4469.77   54.26
 4495.23   54.97 4652.46   49.63 4699.64   49.88  4714.6   49.27 4764.35   49.97
 4814.34   49.27  4904.4   46.34 4956.78   47.41  4986.5   45.76  4988.5   40.44
  5011.5   40.44  5013.5   45.71 5031.33   46.95 5075.43   47.37 5086.49   46.39
 5097.09    46.5 5198.25   50.92 5239.32    51.6 5398.38   52.58 5501.33   51.65
 5576.32   52.84 5601.64   53.94 5678.52   55.68 5814.52   56.19 5911.38   55.71
BR U #Mann= 3
 4093.95     .13  4986.5    .044  5013.5     .13
BR U Banks=4986.5,5013.5
BR D #Sta/Elev= 30
 4125.61   57.21 4144.28   56.71 4291.52   57.97 4395.61      58 4504.34   57.06
 4522.85   56.44 4571.57   53.08 4590.58   50.67 4741.78   48.39 4807.68   45.85
 4830.22   46.41 4856.89    45.4 4899.95   46.56 4930.32   46.11 4952.44    46.7
  4986.5   45.95  4988.5   39.94  5011.5   39.94  5013.5   46.04 5031.78   47.13
 5048.31   47.29 5116.23   52.16 5143.25   51.36 5189.43   51.18 5302.37   51.84
 5363.36   52.89 5502.09   51.84 5594.24   51.96 5772.12    55.6 5918.74   55.97
BR D #Mann= 3
 4125.61     .13  4986.5    .044  5013.5     .13
BR D Banks=4986.5,5013.5
BC Design=,, 0 ,, 0 ,,,,,,
BC Use User HTab Curves=0
BC User HTab FreeFlow(D)= 0

Type RM Length L Ch R = 1 ,3357    ,367.69,367.7,326.93
XS GIS Cut Line= 5
2377318.01550293637735.4439086912377555.45269775637444.043701172
2377936.79107666637073.4979248052377987.15649414 637003.34588623
2378569.95672607636456.521118164
#Sta/Elev= 30
 4125.61   57.21 4144.28   56.71 4291.52   57.97 4395.61      58 4504.34   57.06
 4571.57   53.08 4590.58   50.67 4741.78   48.39 4807.68   45.85 4830.22   46.41
 4856.89    45.4 4899.95   46.56 4930.32   46.11 4952.44    46.7 4981.59   46.22
 4990.06    45.8 4990.41   45.05 4992.32   41.05 5007.79   41.05 5009.59   45.05
 5009.93    45.8 5031.78   47.13 5048.31   47.29 5116.23   52.16 5189.43   51.18
 5363.36   52.89 5502.09   51.84 5594.24   51.96 5772.12    55.6 5918.74   55.97
#Mann= 3 ,-1 , 0
 4125.61     .13       0 4990.41    .044       0 5009.59     .13       0
#XS Ineff= 2 , 0
       0  4978.5   48.94  5021.5       0   48.94
Permanent Ineff=
       F       F
Bank Sta=4990.41,5009.59
XS Rating Curve= 0 ,0
Exp/Cntr=0.5,0.3

Type RM Length L Ch R = 1 ,2989    ,433.86,472.44,421.63
XS GIS Cut Line= 3
2377685.16192627638127.3233032232378148.18347168637365.577880859
2378611.20532227636496.789916992
#Sta/Elev= 30
 3971.98   57.11 4026.43   56.12 4134.09   55.41 4456.41   56.23 4484.66   55.59
 4595.78   50.93 4605.16    50.1 4743.69   47.96  4765.3   47.99 4798.52   48.98
  4836.7   46.52 4847.16   48.18 4903.42   45.53 4931.91   44.95 4987.13   45.17
 4989.93   44.15 4991.74   40.15 5008.14   40.15 5010.08   44.15 5010.32   44.59
 5027.54   44.91 5049.51   44.76 5132.21   49.13 5293.99    51.8 5350.27   53.22
 5372.65   53.45 5538.82   52.09 5650.67    53.8 5687.54   55.21 5847.88   56.17
#Mann= 3 ,-1 , 0
 3971.98     .13       0 4989.93    .044       0 5010.08     .13       0
Bank Sta=4989.93,5010.08
XS Rating Curve= 0 ,0
Exp/Cntr=0.3,0.1

Type RM Length L Ch R = 1 ,2517    ,292.63,380.25,444.5
XS GIS Cut Line= 3
2378071.01330566 638080.025329592378606.22650146637442.748291016
2378805.37567139636628.726074219
#Sta/Elev= 30
 4012.72    59.3 4139.85   57.87 4215.14   56.02  4280.4    51.5 4302.15   50.82
 4464.81   51.46 4552.37    49.5 4574.04   48.34 4692.27   46.34 4717.09   49.03
 4754.54   49.78 4773.11   49.35 4784.63   50.16 4840.91   47.77 4858.05   48.04
 4887.26   47.16 4911.17   45.04 4955.69   45.16 4967.72   43.88  4968.7    39.8
  4984.7    39.8  4986.7   43.88 5060.19   44.52 5152.31    50.8  5220.8   51.06
 5297.26   53.32 5433.38   52.08 5486.08   53.51 5615.03    55.4 5682.96    55.4
#Mann= 3 ,-1 , 0
 4012.72     .13       0 4967.72    .044       0  4986.7     .13       0
Bank Sta=4967.72,4986.7
XS Rating Curve= 0 ,0
Exp/Cntr=0.5,0.3

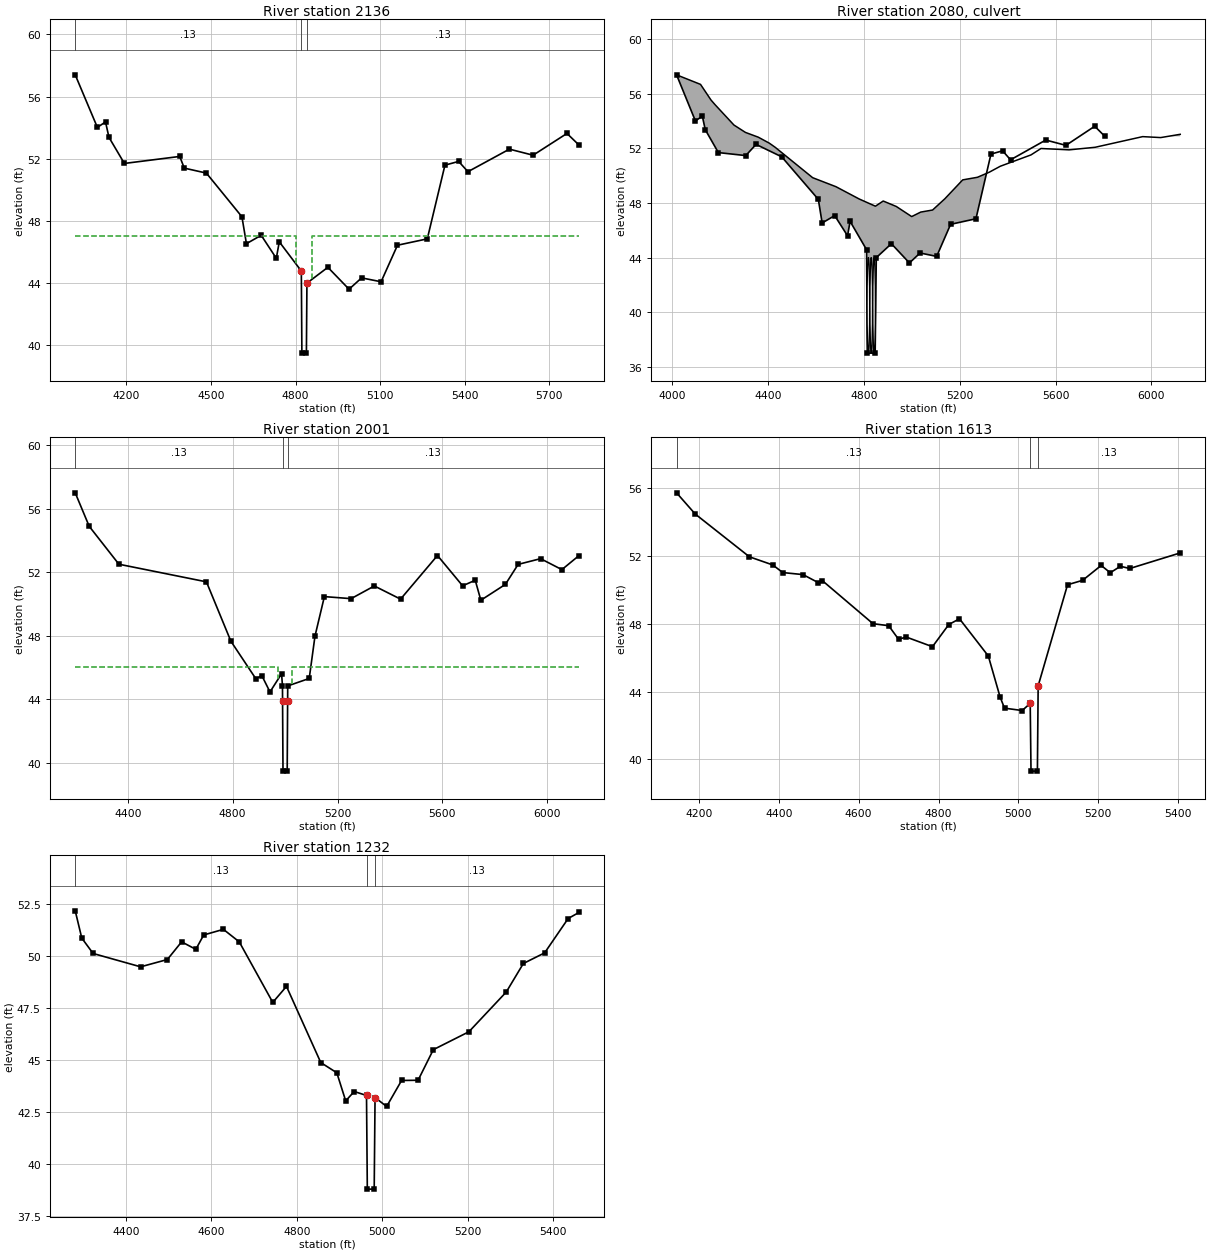
Type RM Length L Ch R = 1 ,2136    ,136.01,135.47,143.11
XS GIS Cut Line= 5
2378258.47570801638121.4719238282378972.77331543637521.711914063
2379068.56848145637417.5869140632379131.04327393637223.914306641
2379135.20831299636713.701721191
#Sta/Elev= 30
 4017.99    57.4 4096.57   54.02 4125.53   54.37 4137.74   53.38 4192.44    51.7
 4388.99   52.15 4405.08    51.4 4483.56   51.08 4609.76   48.27 4625.73   46.54
 4678.13   47.08 4731.79    45.6 4742.36   46.66 4820.63   44.78  4822.6    39.5
  4838.6    39.5  4840.5      44 4914.79   45.02    4990   43.61 5034.59   44.34
 5103.74   44.09 5161.93   46.44 5267.78   46.85 5330.42   51.59 5378.97   51.83
 5412.16   51.17 5559.23   52.62 5643.36   52.23 5763.56   53.63 5805.91   52.89
#Mann= 3 ,-1 , 0
 4017.99     .13       0 4820.63    .044       0  4840.5     .13       0
#XS Ineff= 2 , 0
       0    4803   47.01    4858       0   47.01
Permanent Ineff=
       F       F
Bank Sta=4820.63,4840.5
XS Rating Curve= 0 ,0
Exp/Cntr=0.5,0.3

Type RM Length L Ch R = 2 ,2080    ,,,
Bridge Culvert--1,0,-1,-1, 0
Deck Dist Width WeirC Skew NumUp NumDn MinLoCord MaxHiCord MaxSubmerge Is_Ogee
50,27,2.6,0, 30, 30, , , 0.98, 0, 0,0,,
 4017.99 4117.99 4161.92 4178.74 4257.52 4305.39 4359.06 4405.28 4430.27 4586.13
  4683.4 4780.26 4848.05 4880.59 4935.26 4999.47 5037.31 5086.72 5137.65 5212.46
 5274.05 5323.09 5369.54 5497.51 5539.34 5656.64  5765.6 5963.73 6038.99 6120.53
    57.4    56.7   55.55   55.21   53.72   53.18   52.83   52.39   52.08   49.86
    49.2    48.3   47.77   48.15   47.75   47.01   47.34   47.49   48.31    49.7
   49.89   50.26    50.7   51.53      52    51.9   52.09   52.87    52.8   53.04
                                                                                
                                                                                
                                                                                
 4017.99 4117.99 4161.92 4178.74 4257.52 4305.39 4359.06 4405.28 4430.27 4586.13
  4683.4 4780.26 4848.05 4880.59 4935.26 4999.47 5037.31 5086.72 5137.65 5212.46
 5274.05 5323.09 5369.54 5497.51 5539.34 5656.64  5765.6 5963.73 6038.99 6120.53
    57.4    56.7   55.55   55.21   53.72   53.18   52.83   52.39   52.08   49.86
    49.2    48.3   47.77   48.15   47.75   47.01   47.34   47.49   48.31    49.7
   49.89   50.26    50.7   51.53      52    51.9   52.09   52.87    52.8   53.04
                                                                                
                                                                                
                                                                                
BR Coef=-1 , 0 , 0 ,, 0 ,,,0.8,-1,,0,
WSPro=,,,, 1 ,,,, 0 ,,,, 0 ,,,,-1 ,-1 ,-1 , 0 , 0 , 0 , 0 , 0
Multiple Barrel Culv=3,7,10.79,59.5,0.024,0.9,1,34,1,37.01,36.5, 3,Culvert #1  , 0 ,36
  4818.6    4988  4830.6    5000  4842.6    5012
Culvert Bottom n=0.024
BR U #Sta/Elev= 30
 4017.99    57.4 4096.57   54.02 4125.53   54.37 4137.74   53.38 4192.44    51.7
 4306.83   51.48 4349.87    52.3 4456.92   51.39 4609.76   48.27 4625.73   46.54
 4678.13   47.08 4731.79    45.6 4742.36   46.66 4811.15   44.58    4814      37
    4847      37 4851.73      44 4914.79   45.02    4990   43.61 5034.59   44.34
 5103.74   44.09 5161.93   46.44 5267.78   46.85 5330.42   51.59 5378.97   51.83
 5412.16   51.17 5559.23   52.62 5643.36   52.23 5763.56   53.63 5805.91   52.89
BR U #Mann= 3
 4017.99     .13 4811.15    .044 4851.73     .13
BR U Banks=4811.15,4851.73
BR D #Sta/Elev= 30
 4199.57      57 4252.87   54.89 4346.45   52.74 4699.99   51.39 4793.19   47.65
 4888.52   45.28 4911.29   45.48 4942.38   44.45 4978.65   45.42    4983    36.5
    5017    36.5 5021.34   44.84 5092.01    45.3    5114   47.97 5149.84   50.46
 5251.69   50.33 5340.37   51.13 5440.38    50.3 5486.19   50.76 5537.99   52.26
 5550.79   51.97 5581.15   53.05 5677.07   51.14 5725.21   51.49 5746.59   50.23
 5840.23   51.23 5888.75   52.49 5974.43   52.85 6055.68   52.16 6120.53   53.04
BR D #Mann= 3
 4199.57     .13 4978.65    .044 5021.34     .13
BR D Banks=4978.65,5021.34
BC Design=,, 0 ,, 0 ,,,,,,
BC Use User HTab Curves=0
BC User HTab FreeFlow(D)= 0

Type RM Length L Ch R = 1 ,2001    ,381.17,388.15,397.48
XS GIS Cut Line= 6
2378312.62072754638181.8645019532378864.48327637637790.354492188
2379185.18847656637511.2993164062379247.66333008637392.596923828
2379270.57092285637248.9042968752379255.99328613636709.536682129
#Sta/Elev= 30
 4199.57      57 4252.87   54.89 4366.14    52.5 4699.99   51.39 4793.19   47.65
 4888.52   45.28 4911.29   45.48 4942.38   44.45 4986.61    45.6 4990.02   44.82
 4990.36   43.86 4992.01   39.46 5008.03   39.46 5009.64   43.86 5010.02   44.83
 5092.01    45.3    5114   47.97 5149.84   50.46 5251.69   50.33 5340.37   51.13
 5440.38    50.3 5581.15   53.05 5677.07   51.14 5725.21   51.49 5746.59   50.23
 5840.23   51.23 5888.75   52.49 5974.43   52.85 6055.68   52.16 6120.53   53.04
#Mann= 3 ,-1 , 0
 4199.57     .13       0 4990.36    .044       0 5009.64     .13       0
#XS Ineff= 2 , 0
       0 4972.61      46 5027.39       0      46
Permanent Ineff=
       F       F
Bank Sta=4990.36,5009.64
XS Rating Curve= 0 ,0
Exp/Cntr=0.5,0.3

Type RM Length L Ch R = 1 ,1613    ,421,380.88,343.97
XS GIS Cut Line= 3
 2378362.2689209638336.4298706052379024.43969727638137.280700684
 2379486.2166748637803.394897461
#Sta/Elev= 30
 4143.98   55.74 4190.58   54.49 4326.44   51.96 4384.85   51.48 4409.88   51.03
 4460.59   50.91 4498.42   50.44  4508.7   50.56 4635.82   48.01 4675.19   47.89
 4699.88   47.09  4719.2   47.22 4784.82   46.65 4825.72   47.96 4852.46    48.3
  4924.7    46.1 4954.14   43.68 4965.25   43.02  5009.5   42.88 5029.58    43.3
  5031.6    39.3  5047.6    39.3  5049.5   44.34 5123.08   50.31 5160.83   50.57
 5207.33   51.45  5230.1   51.02 5255.44    51.4 5278.98   51.27 5405.29   52.19
#Mann= 3 ,-1 , 0
 4143.98     .13       0 5029.58    .044       0  5049.5     .13       0
Bank Sta=5029.58,5049.5
XS Rating Curve= 0 ,0
Exp/Cntr=0.3,0.1

Type RM Length L Ch R = 1 ,1232    ,1326.97,1231.89,998.23
XS GIS Cut Line= 4
2378922.99810791638771.1350708012379299.51452637638463.076293945
2379514.22210693638179.9110717772379607.57330322637856.293884277
#Sta/Elev= 30
 4281.25   52.17 4296.58   50.86 4323.14   50.12 4434.29   49.48 4496.76   49.83
 4530.24   50.68 4563.47   50.32 4581.93   51.01 4627.98   51.28 4665.09   50.68
 4743.56   47.77 4775.61   48.54 4855.88   44.88 4893.42   44.39 4914.19   43.04
 4934.15   43.49  4962.9    43.3  4964.8    38.8  4980.9    38.8  4982.9    43.2
 5009.99   42.77 5044.99   44.02 5083.56   44.03 5119.25    45.5 5202.51   46.36
 5289.94   48.27 5329.94   49.64 5379.74   50.15 5434.78    51.8 5459.91   52.09
#Mann= 3 ,-1 , 0
 4281.25     .13       0  4962.9    .044       0  4982.9     .13       0
Bank Sta=4962.9,4982.9
XS Rating Curve= 0 ,0
Exp/Cntr=0.3,0.1

Chan Stop Cuts=-1
Use User Specified Reach Order=0