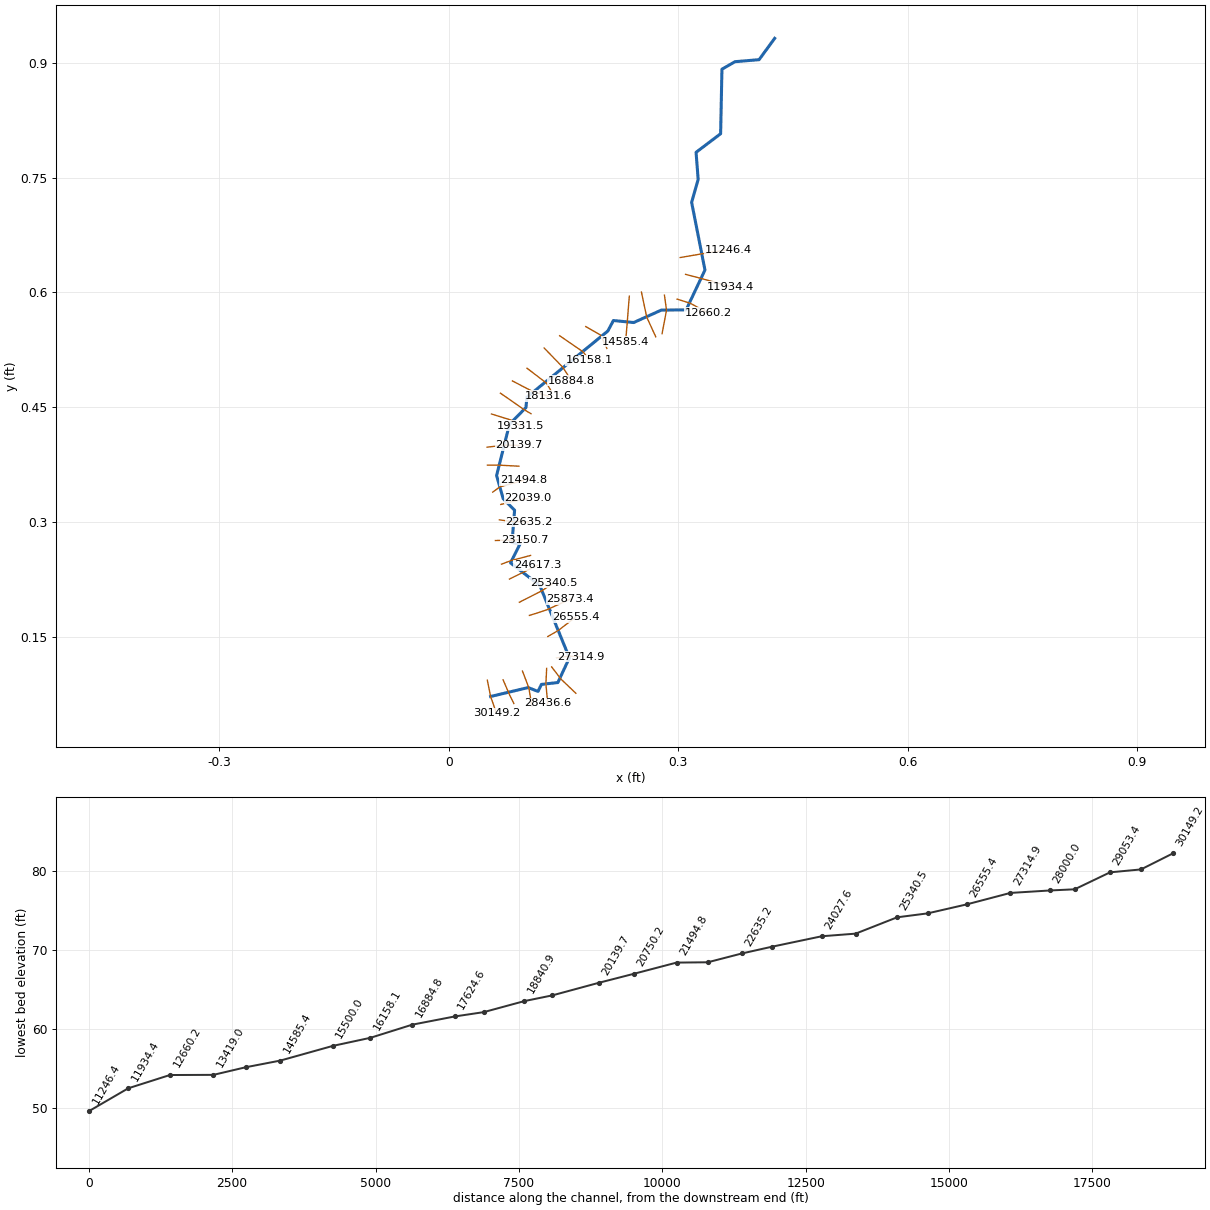
--- lds_fort_run_upper.prj (project) ---

Proj Title=Fort Run
Current Plan=p01
Default Exp/Contr=0.3,0.1
English Units
Geom File=g01
Flow File=f01
Flow File=f02
Plan File=p01
Plan File=p02
Y Axis Title=Elevation
X Axis Title(PF)=Main Channel Distance
X Axis Title(XS)=Station
BEGIN DESCRIPTION:
####(Watershed Name)####
FORT RUN
HCFCD Unit X###-##-##
(Flood Hazard, Floodway) Model
10, 2, 1, 0.2% Event
Filename:  N:\NC_flood\60138\Approximates\Eng\Toisnot_Nahunta\ENG\Fort Run\Fort Run.prj
Prepared by:  ________     Date: ________
Reviewed by:  ________     Date: ________
STATUS (Draft RAS, SVSQ, FINAL)
END DESCRIPTION:
DSS Export Rating Curves= 0
DSS Export Rating Curve Sorted= 0
DSS Export Volume Flow Curves= 0
DXF OffsetX= 0
DXF OffsetY= 0
DXF ScaleX= 1
DXF ScaleY= 10

--- lds_fort_run_upper.p01 (plan) ---

Plan Title=100 Year Single
Program Version=4.00
Short Identifier=Plan01
Geom File=g01
Flow File=f01
Subcritical Flow
K Sum by GR= 0
Std Step Tol= 0.01
Critical Tol= 0.01
Num of Std Step Trials= 20
Max Error Tol= 0.3
Flow Tol Ratio= 0.001
Split Flow NTrial= 30
Split Flow Tol= 0.02
Split Flow Ratio= 0.02
Log Output Level= 0
Friction Slope Method= 1
Unsteady Friction Slope Method= 2
Unsteady Bridges Friction Slope Method= 1
Parabolic Critical Depth
Global Vel Dist= 0 , 0 , 0
Global Log Level= 0
CheckData=True
Encroach Param=-1 ,10,10, 2
Encroach River=Fort Run
Encroach Reach=Reach - 1
Encroach Node=30149.2
       4      .7
Encroach Node=29592.7
       1    4835    5035
Encroach Node=29053.4
       1    4900    5120
Encroach Node=28436.6
       1    4880    5145
Encroach Node=28000.0
       1    4885    5150
Encroach Node=27314.9
       1    4885    5110
Encroach Node=26555.4
       1    4900    5215
Encroach Node=25873.4
       1    4855    5160
Encroach Node=25340.5
       4      .7
Encroach Node=24617.3
       4      .7
Encroach Node=24027.6
       4      .7
Encroach Node=23150.7
       4      .7
Encroach Node=22635.2
       4      .7
Encroach Node=22039.0
       4      .7
Encroach Node=21494.8
       4      .7
Encroach Node=20750.2
       4      .7
Encroach Node=20139.7
       4      .7
Encroach Node=19331.5
       4      .7
Encroach Node=18840.9
       4      .7
Encroach Node=18131.6
       4      .7
Encroach Node=17624.6
       4      .7
Encroach Node=16884.8
       4      .7
Encroach Node=16158.1
       4      .7
Encroach Node=15500.0
       4      .7
Encroach Node=14585.4
       4      .7
Encroach Node=13979.3
       4      .7
Encroach Node=13419.0
       4      .7
Encroach Node=12660.2
       1    4885    5175
Encroach Node=11934.4
       1    4900    5095
Encroach Node=11246.4
       1    4968    5030
Encroach Node=11150.4
       1    4970    5028
Encroach Node=10277.5
       1    4920    5125
Encroach Node=9568.9
       1    4850    5130
Encroach Node=8815.2
       1    4775    5028
Encroach Node=8161.1
       1    4850    5165
Encroach Node=7540.3
       4      .7
Encroach Node=6733.9
       4      .7
Encroach Node=5999.7
       4      .7
Encroach Node=5407.9
       4      .7
Encroach Node=4527.9
       4      .7
Encroach Node=4275.8
       4      .7
Encroach Node=3674.1
       1    4790    5105
Computation Interval=1HOUR
Output Interval=1HOUR
Run HTab= 0
Run UNet= 0
Run PostProcess= 0
Run WQNet= 0
UNET Theta= 1
UNET Theta Warmup= 1
UNET ZTol= 0.02
UNET ZSATol= 0.1
UNET MxIter= 20
UNET MaxInSteps= 20
UNET DtIC= 0
UNET DtMin= 0
UNET MaxCRTS= 20
UNET WFStab= 2
UNET SFStab= 1
UNET WFX= 1
UNET SFX= 1
UNET DSS MLevel= 4
UNET DZMax Abort= 100
UNET Convert EG Bridges=-1
UNET Use Existing IB Tables=-1
UNET Froude Reduction=False
UNET Froude Limit= 1
UNET Froude Power= 10
UNET Time Slicing=0,0, 5
Instantaneous Interval=1HOUR
Write IC File= 0
Echo Input=False
Echo Output=False
Write Detailed= 0
Detailed Automatic Start=False, 10
WQ ULTIMATE=-1
WQ Max Comp Step=1HOUR
WQ Output Interval=15MIN
WQ Output Selected Increments= 0
WQ Output face flow=0
WQ Output face velocity=0
WQ Output face area=0
WQ Output face dispersion=0
WQ Output cell volume=0
WQ Output cell surface area=0
WQ Output cell continuity=0
WQ Output face conc=0
WQ Output face dconc_dx=0
WQ Output face courant=0
WQ Output face peclet=0
WQ Output face adv mass=0
WQ Output face disp mass=0
WQ Output cell mass=0
WQ Output cell source sink temp=0
WQ Output cell source sink nsm=0
WQ Output MaxMinRange=-1
WQ Daily Max Min Mean=-1
WQ Daily Range=0
WQ Daily Time=0
WQ Create Restart=0
WQ Fixed Restart=0
WQ System Summary=False
Sorting and Armoring Iterations= 10
XS Update Threshold= 0.02
Hydraulics Update Threshold= 0.02
Energy Slope Method= 1
Volume Change Method= 0
XS Weighting Method= 0
Number of US Weighted Cross Sections= 1
Number of DS Weighted Cross Sections= 1
Upstream XS Weight=0.25
Main XS Weight=0.5
Downstream XS Weight=0.25
Number of DS XS's Weighted with US Boundary= 1
Upstream Boundary Weight= 1
Weight of XSs Associated with US Boundary= 0
Number of US XS's Weighted with DS Boundary= 1
Downstream Boundary Weight= 0.5
Weight of XSs Associated with DS Boundary= 0.5
Sediment Output Level= 4
Mass or Volume Output= 0
Output Increment Type= 1
Profile and TS Output Increment= 10
XS Output Flag= 0
XS Output Increment= 10
Disregard all LS=0
Disregard all Conn=0
Disregard all Breaches=0
Disregard all Pumps=0

--- lds_fort_run_upper.p02 (plan) ---

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Plan Title=Multi-Profile
Short Identifier=Multi
Geom File=g01
Flow File=f02

--- lds_fort_run_upper.f01 (steady flow) ---

Flow Title= 100 Year Single
Program Version=4.00
Number of Profiles= 2
Profile Names=100-Year,AFW
River Rch & RM=Fort Run,Reach - 1       ,30149.2
     733     733
River Rch & RM=Fort Run,Reach - 1       ,25873.4
     904     904
River Rch & RM=Fort Run,Reach - 1       ,24027.6
     960     960
River Rch & RM=Fort Run,Reach - 1       ,20750.2
    1174    1174
River Rch & RM=Fort Run,Reach - 1       ,18131.6
    1223    1223
River Rch & RM=Fort Run,Reach - 1       ,14585.4
    1488    1488
River Rch & RM=Fort Run,Reach - 1       ,12660.2
    1539    1539
River Rch & RM=Fort Run,Reach - 1       ,8161.1
    1647    1647
River Rch & RM=Fort Run,Reach - 1       ,5407.9
    1799    1799
Boundary for River Rch & Prof#=Fort Run,Reach - 1       , 1
Up Type= 0
Dn Type= 1
Dn Known WS=51.44
Boundary for River Rch & Prof#=Fort Run,Reach - 1       , 2
Up Type= 0
Dn Type= 1
Dn Known WS=51.99
DSS Import GetInterval= 0
DSS Import GetPeak= 0
DSS Import FillOption= 0

--- lds_fort_run_upper.f02 (steady flow) ---

Flow Title=Multi-Profile
Program Version=4.00
Number of Profiles= 7
Profile Names=10 YR,25 YR,50 YR,500 YR,100 YR - 10%,100 YR - 20%,100 YR - 35%
River Rch & RM=Fort Run,Reach - 1       ,30149.2
     306     450     581    1186    1278    1638    2001
River Rch & RM=Fort Run,Reach - 1       ,25873.4
     385     560     720    1448    1565    2005    2450
River Rch & RM=Fort Run,Reach - 1       ,24027.6
     410     597     765    1532    1658    2125    2596
River Rch & RM=Fort Run,Reach - 1       ,20750.2
     511     737     941    1857    2014    2581    3154
River Rch & RM=Fort Run,Reach - 1       ,18131.6
     534     769     981    1930    2095    2685    3281
River Rch & RM=Fort Run,Reach - 1       ,14585.4
     661     944    1199    2326    2532    3246    3966
River Rch & RM=Fort Run,Reach - 1       ,12660.2
     685     978    1240    2402    2615    3352    4095
River Rch & RM=Fort Run,Reach - 1       ,8161.1
     738    1050    1329    2561    2792    3578    4372
River Rch & RM=Fort Run,Reach - 1       ,5407.9
     812    1152    1455    2787    3041    3898    4763
Boundary for River Rch & Prof#=Fort Run,Reach - 1       , 1
Up Type= 0
Dn Type= 1
Dn Known WS=49.25
Boundary for River Rch & Prof#=Fort Run,Reach - 1       , 2
Up Type= 0
Dn Type= 1
Dn Known WS=50.37
Boundary for River Rch & Prof#=Fort Run,Reach - 1       , 3
Up Type= 0
Dn Type= 1
Dn Known WS=51.01
Boundary for River Rch & Prof#=Fort Run,Reach - 1       , 4
Up Type= 0
Dn Type= 1
Dn Known WS=52.18
Boundary for River Rch & Prof#=Fort Run,Reach - 1       , 5
Up Type= 0
Dn Type= 1
Dn Known WS=52.31
Boundary for River Rch & Prof#=Fort Run,Reach - 1       , 6
Up Type= 0
Dn Type= 1
Dn Known WS=52.97
Boundary for River Rch & Prof#=Fort Run,Reach - 1       , 7
Up Type= 0
Dn Type= 1
Dn Known WS=53.62
DSS Import GetInterval= 0
DSS Import GetPeak= 0
DSS Import FillOption= 0

--- lds_fort_run_upper.g01 (geometry) ---

Geom Title=Geom 01 by CodeH2 for Windows
Program Version=4.00

River Reach=Fort Run        ,Reach - 1
Reach XY= 30
  0.054710047084  0.072058748017  0.103779071671  0.083714168181
  0.116656672584  0.078679158487   0.12110802195  0.087846383102
  0.142611270812   0.09030627341  0.157656180375  0.122591456961
  0.118977286007  0.217022187025  0.080698186438  0.246631550997
  0.093101845144  0.271172839539  0.082698663424  0.273306581458
  0.086033292729  0.315453871061  0.071095095312  0.330525333411
  0.062515037997  0.360850119656  0.079351008222  0.427754627073
  0.100871791944  0.449567992452  0.102189411397  0.463183560457
  0.207889545247  0.549558776007  0.215203084701   0.56327704819
  0.241657175931  0.560636799326  0.277808545532  0.576885101255
  0.310203447205  0.577189706817  0.334828903074  0.629233671195
  0.317413280489  0.717632910542  0.325943238205  0.747692168912
  0.323201788151  0.783031424015  0.355291583266  0.807301673727
   0.35701751445  0.891588236997  0.374077930878  0.901438319145
   0.40555851487  0.904079069006  0.425929039618  0.931954948985

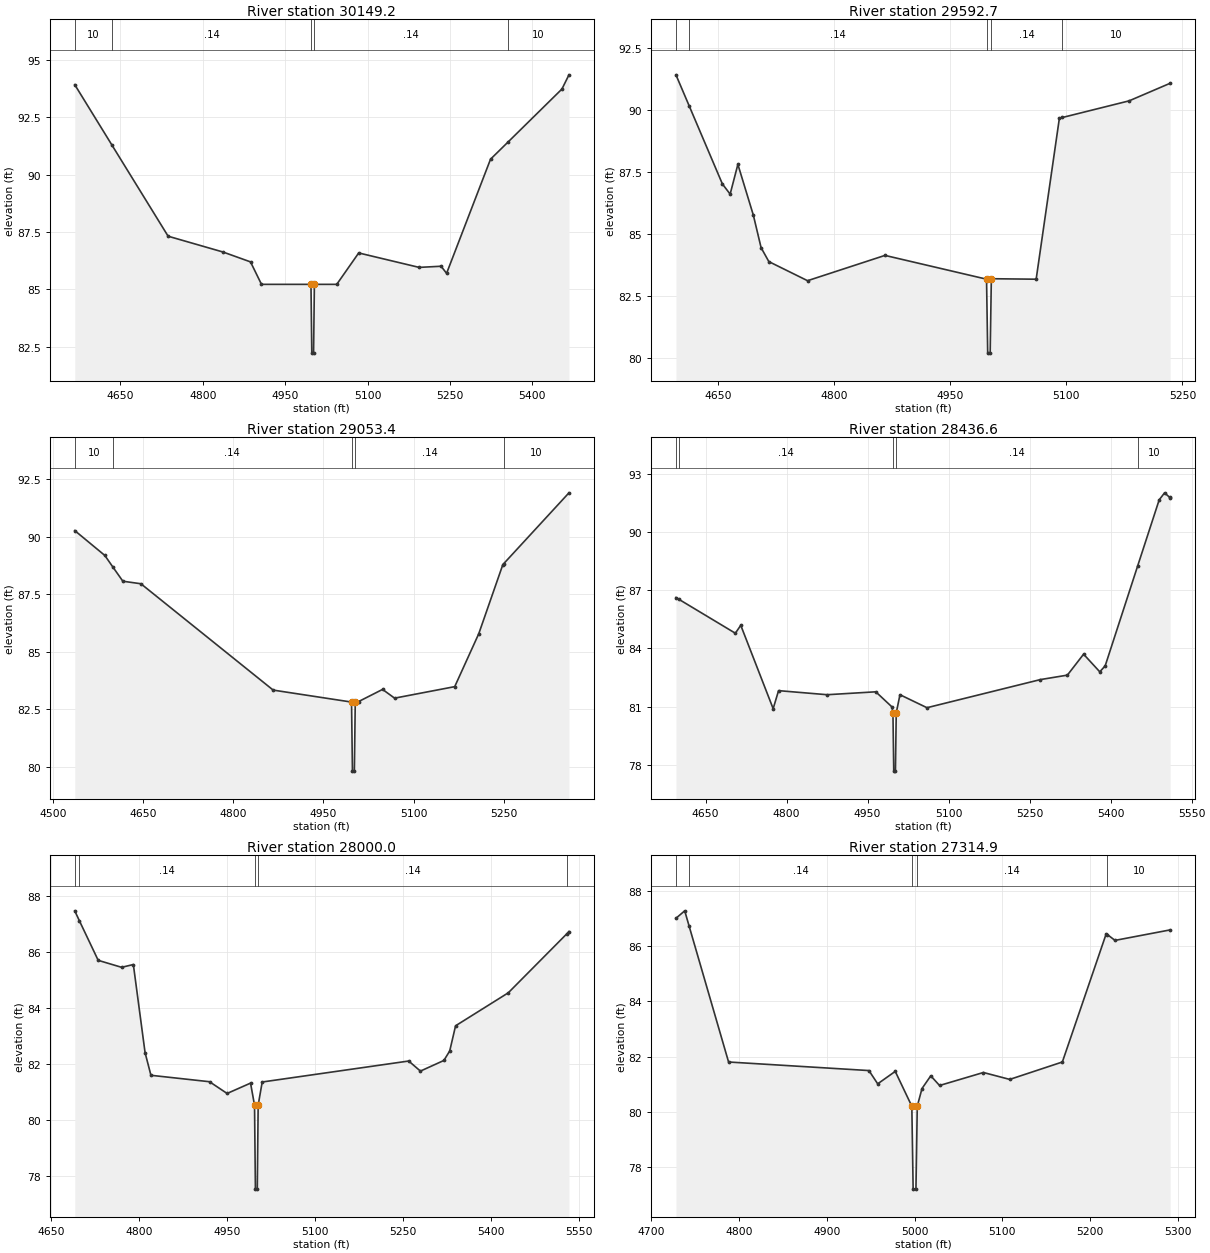
Type RM Length L Ch R = 1 ,30149.2 ,556.5,556.5,556.5
BEGIN DESCRIPTION:
Fort Run 37.0
END DESCRIPTION:
XS GIS Cut Line= 3
  0.050385817487   0.09334229662  0.054773128802  0.071891815304
  0.062405137807            0.05
#Sta/Elev= 21
  4566.8   93.93  4634.9   91.28  4736.8   87.32  4836.8   86.63  4886.8    86.2
  4906.8   85.22  4996.8   85.22  4996.9   85.22  4998.4   82.22  5001.6   82.22
  5003.1   85.22  5003.8   85.22  5043.8   85.22  5083.8   86.59  5193.8   85.96
  5233.8   86.01  5243.8    85.7  5323.8   90.68  5354.9   91.41  5453.8   93.74
  5466.6   94.36
#Mann= 5 , 1 , 0
  4566.8      10       0  4634.9     .14       0  4996.9    .044       0
  5003.1     .14       0  5354.9      10       0
Bank Sta=4996.9,5003.1
XS Rating Curve= 0 ,0
Exp/Cntr=0.3,0.1

Type RM Length L Ch R = 1 ,29592.7 ,539.3,539.3,539.3
BEGIN DESCRIPTION:
Fort Run 36.0
END DESCRIPTION:
XS GIS Cut Line= 3
  0.071041358523  0.093783630608  0.079878421582    0.0732977117
   0.08510032248  0.062853909904
#Sta/Elev= 20
  4595.7   91.41  4612.9   90.15  4655.7   87.01  4665.7    86.6  4675.7    87.8
  4695.7   85.75  4705.7   84.44  4715.7   83.88  4765.7   83.11  4865.7   84.13
  4995.7   83.18  4996.9   83.19  4998.4   80.19  5001.6   80.19  5003.1   83.19
    5061   83.17    5091   89.66  5094.9   89.69    5181   90.36  5234.1   91.07
#Mann= 5 , 1 , 0
  4595.7      10       0  4612.9     .14       0  4996.9    .044       0
  5003.1     .14       0  5094.9      10       0
Bank Sta=4996.9,5003.1
XS Rating Curve= 0 ,0
Exp/Cntr=0.3,0.1

Type RM Length L Ch R = 1 ,29053.4 ,616.8,616.8,616.8
BEGIN DESCRIPTION:
Fort Run 35.0
END DESCRIPTION:
XS GIS Cut Line= 3
  0.096298098485  0.105302638729  0.104593174464  0.083696859436
  0.108644258081  0.059583266475
#Sta/Elev= 18
  4536.6   90.27  4586.6   89.19  4599.9   88.69  4616.6   88.07  4646.6   87.96
  4866.6   83.34  4996.9   82.82  4998.4   79.82  5001.6   79.82  5003.1   82.82
  5008.5   82.84  5048.5   83.37  5068.5   82.99  5168.5   83.49  5208.5   85.79
  5248.5   88.79  5249.9   88.83  5358.5   91.91
#Mann= 5 , 1 , 0
  4536.6      10       0  4599.9     .14       0  4996.9    .044       0
  5003.1     .14       0  5249.9      10       0
Bank Sta=4996.9,5003.1
XS Rating Curve= 0 ,0
Exp/Cntr=0.3,0.1

Type RM Length L Ch R = 1 ,28436.6 ,436.6,436.6,436.6
BEGIN DESCRIPTION:
Fort Run 34.0
END DESCRIPTION:
XS GIS Cut Line= 3
  0.127935132449  0.108774996115  0.126970588731  0.088519578028
  0.129285493655  0.063055623861
#Sta/Elev= 25
  4595.1   86.62  4599.9   86.54  4705.1   84.78  4715.1   85.19  4775.1   80.89
  4785.1   81.82  4875.1   81.61  4965.1   81.76  4995.1   80.98  4996.9   80.67
  4998.4   77.67  5001.5   77.67    5003   80.67  5009.9   81.61  5059.9   80.94
  5269.9   82.39  5319.9   82.62  5349.9    83.7  5379.9   82.79  5389.9    83.1
  5449.9   88.24  5489.9   91.66  5499.9   92.02  5509.9   91.77  5510.2   91.78
#Mann= 5 , 1 , 0
  4595.1      10       0  4599.9     .14       0  4996.9    .044       0
    5003     .14       0  5449.9      10       0
Bank Sta=4996.9,5003
XS Rating Curve= 0 ,0
Exp/Cntr=0.3,0.1

Type RM Length L Ch R = 1 ,28000.0 ,685.1,685.1,685.1
BEGIN DESCRIPTION:
Fort Run 33.0
END DESCRIPTION:
XS GIS Cut Line= 3
   0.13450753867  0.110654387356  0.146699139378  0.094754935722
  0.166039786402  0.076310346833
#Sta/Elev= 23
  4690.1   87.47  4697.9   87.12  4730.1    85.7  4770.1   85.45  4790.1   85.55
  4810.1    82.4  4820.1   81.59  4920.1   81.36  4950.1   80.94  4990.1   81.31
  4996.9   80.52  4998.4   77.52  5001.6   77.52  5003.1   80.52    5010   81.35
    5260    82.1    5280   81.74    5320   82.12    5330   82.46    5340   83.36
    5430   84.54  5529.9   86.65  5533.5   86.73
#Mann= 5 , 1 , 0
  4690.1      10       0  4697.9     .14       0  4996.9    .044       0
  5003.1     .14       0  5529.9      10       0
Bank Sta=4996.9,5003.1
XS Rating Curve= 0 ,0
Exp/Cntr=0.3,0.1

Type RM Length L Ch R = 1 ,27314.9 ,759.5,759.5,759.5
BEGIN DESCRIPTION:
Fort Run 32.0
END DESCRIPTION:
XS GIS Cut Line= 3
   0.14105292702  0.122471516917  0.157450170234  0.124786421841
  0.172111234754   0.12420769561
#Sta/Elev= 21
    4728   87.01    4738   87.28  4742.9   86.74    4788   81.81    4948    81.5
    4958   81.02    4978   81.47  4996.9   80.21  4998.4   77.21  5001.6   77.21
  5003.1   80.21  5008.5   80.85  5018.5   81.31  5028.5   80.96  5078.5   81.43
  5108.5   81.18  5168.5   81.81  5218.5   86.45  5219.9   86.42  5228.5   86.21
  5291.4   86.59
#Mann= 5 , 1 , 0
    4728      10       0  4742.9     .14       0  4996.9    .044       0
  5003.1     .14       0  5219.9      10       0
Bank Sta=4996.9,5003.1
XS Rating Curve= 0 ,0
Exp/Cntr=0.3,0.1

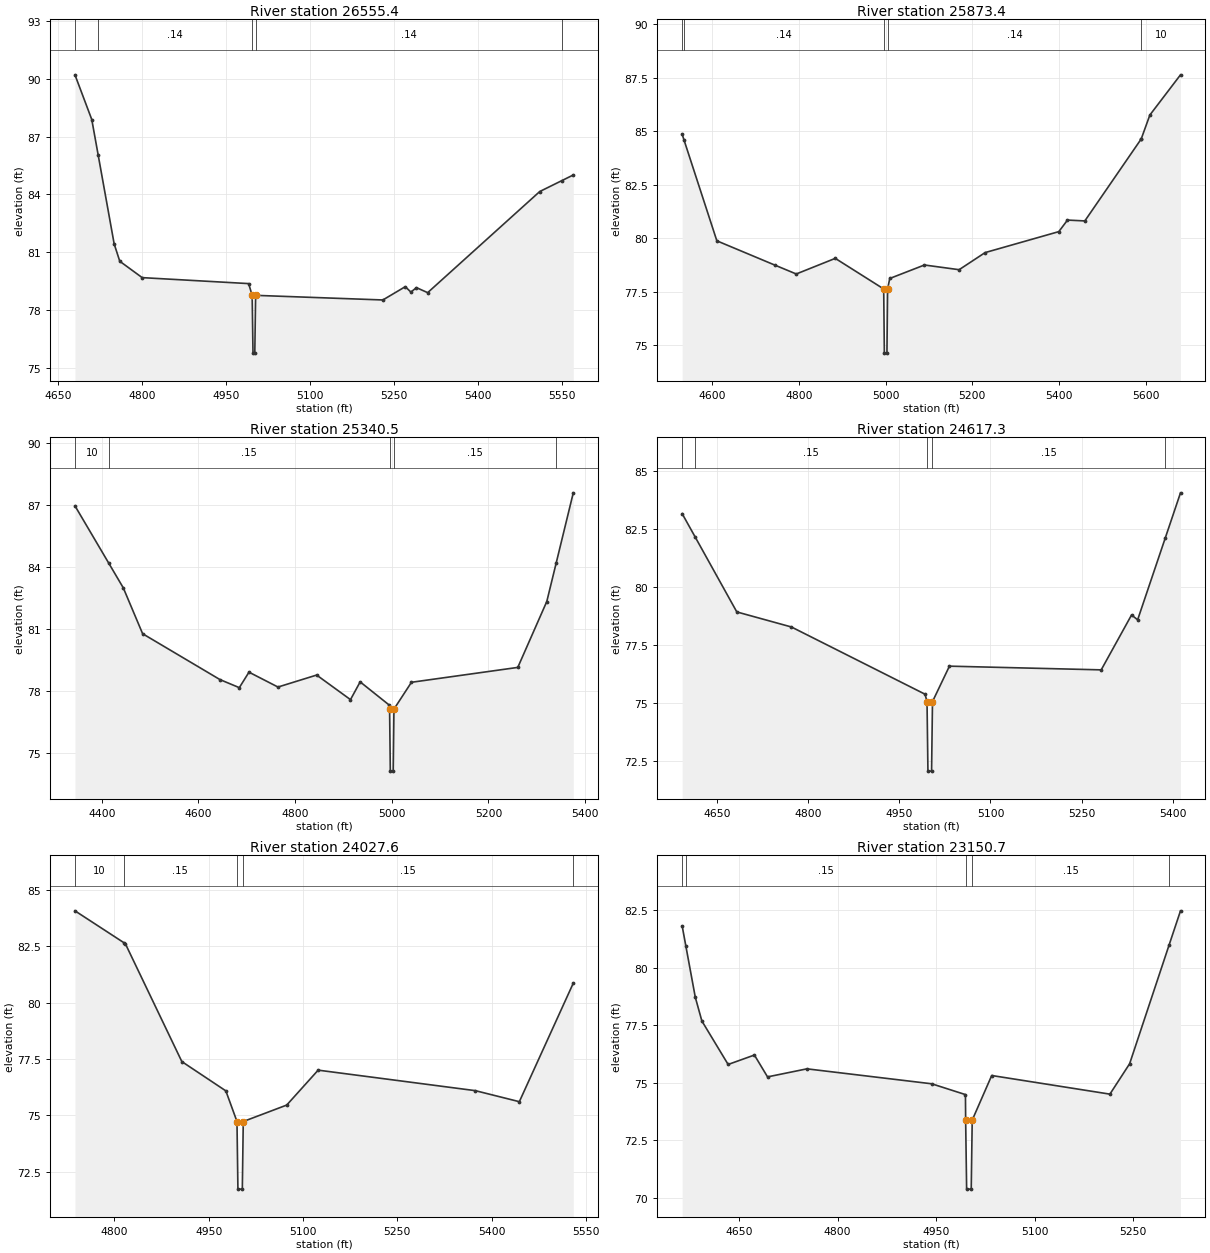
Type RM Length L Ch R = 1 ,26555.4 ,682,682,682
BEGIN DESCRIPTION:
Fort Run 31.0
END DESCRIPTION:
XS GIS Cut Line= 3
  0.129478402399  0.150443284752  0.143344601729  0.158454864809
  0.165938154956  0.175907238918
#Sta/Elev= 19
  4680.6   90.21  4710.6   87.89  4721.9   86.07  4750.6   81.43  4760.6   80.53
  4800.6   79.68  4990.6   79.37  4996.9   78.76  4998.4   75.76  5001.6   75.76
  5003.1   78.76  5230.2   78.52  5270.2   79.21  5280.2   78.93  5290.2   79.16
  5310.2    78.9  5510.2   84.15  5549.9   84.72  5570.1   85.01
#Mann= 5 , 1 , 0
  4680.6      10       0  4721.9     .14       0  4996.9    .044       0
  5003.1     .14       0  5549.9      10       0
Bank Sta=4996.9,5003.1
XS Rating Curve= 0 ,0
Exp/Cntr=0.3,0.1

Type RM Length L Ch R = 1 ,25873.4 ,532.9,532.9,532.9
BEGIN DESCRIPTION:
Fort Run 30.5
END DESCRIPTION:
XS GIS Cut Line= 4
  0.105364809438  0.178029235099  0.115588972854  0.181115774998
  0.127742223706  0.185166858616   0.15880053144  0.199249196904
#Sta/Elev= 21
  4530.6   84.85  4534.9   84.58  4610.6   79.87  4743.8   78.74  4793.8   78.32
  4883.8   79.05  4995.5   77.62    4997   74.62    5003   74.62  5004.5   77.62
  5009.5   78.11  5089.5   78.74  5169.5   78.52  5229.5   79.32  5399.5    80.3
  5419.5   80.84  5459.5    80.8  5589.5   84.63  5589.9   84.65  5609.5   85.75
  5680.2   87.63
#Mann= 5 , 1 , 0
  4530.6      10       0  4534.9     .14       0  4995.5    .044       0
  5004.5     .14       0  5589.9      10       0
Bank Sta=4995.5,5004.5
XS Rating Curve= 0 ,0
Exp/Cntr=0.3,0.1

Type RM Length L Ch R = 1 ,25340.5 ,723.2,723.2,723.2
BEGIN DESCRIPTION:
Fort Run 30.0
END DESCRIPTION:
XS GIS Cut Line= 3
  0.092247014868  0.195198113287  0.121569143908  0.210052086551
  0.137194752147   0.22046915871
#Sta/Elev= 21
  4344.6   86.96  4414.9   84.17  4444.6   82.99  4484.6   80.77  4644.6   78.55
  4684.6   78.16  4704.6   78.91  4764.6   78.19  4844.6   78.77  4914.6   77.58
  4934.6   78.44  4994.6   77.32  4995.5   77.12    4997   74.12    5003   74.12
  5004.5   77.12  5040.7   78.42  5260.7   79.14  5320.7   82.33  5339.9   84.17
  5375.5   87.59
#Mann= 5 , 1 , 0
  4344.6      10       0  4414.9     .15       0  4995.5    .045       0
  5004.5     .15       0  5339.9      10       0
Bank Sta=4995.5,5004.5
XS Rating Curve= 0 ,0
Exp/Cntr=0.3,0.1

Type RM Length L Ch R = 1 ,24617.3 ,589.7,589.7,589.7
BEGIN DESCRIPTION:
Fort Run 29.0
END DESCRIPTION:
XS GIS Cut Line= 3
  0.079322129041  0.225484786046  0.097753390041  0.234574112518
  0.116230885527  0.243612017919
#Sta/Elev= 15
  4592.2   83.16  4613.9   82.14  4682.2   78.92  4772.2   78.27  4992.2   75.37
  4995.5   75.05    4997   72.05    5003   72.05  5004.5   75.05  5032.4   76.58
  5282.4   76.42  5332.4   78.79  5342.4   78.58  5387.9   82.11    5413   84.06
#Mann= 5 , 1 , 0
  4592.2      10       0  4613.9     .15       0  4995.5    .045       0
  5004.5     .15       0  5387.9      10       0
Bank Sta=4995.5,5004.5
XS Rating Curve= 0 ,0
Exp/Cntr=0.3,0.1

Type RM Length L Ch R = 1 ,24027.6 ,876.9,876.9,876.9
BEGIN DESCRIPTION:
Fort Run 28.0
END DESCRIPTION:
XS GIS Cut Line= 3
  0.068905056881  0.244968569158  0.081444125221  0.249598379007
  0.106908079388  0.256350185036
#Sta/Elev= 14
  4737.3   84.07  4814.9   82.66  4817.3   82.62  4907.3   77.38  4977.3   76.08
    4995   74.72  4996.5   71.72  5003.5   71.72    5005   74.72  5074.1   75.45
  5124.1      77  5374.1   76.09  5444.1    75.6  5529.9   80.86
#Mann= 5 , 1 , 0
  4737.3      10       0  4814.9     .15       0    4995    .045       0
    5005     .15       0  5529.9      10       0
Bank Sta=4995,5005
XS Rating Curve= 0 ,0
Exp/Cntr=0.3,0.1

Type RM Length L Ch R = 1 ,23150.7 ,515.5,515.5,515.5
BEGIN DESCRIPTION:
Fort Run 27.0
END DESCRIPTION:
XS GIS Cut Line= 3
   0.06099579839  0.275833968148  0.082601577683   0.27641269438
  0.098998820896  0.276991420611
#Sta/Elev= 19
  4563.3   81.82  4568.9   80.95  4583.3   78.72  4593.3   77.69  4633.3    75.8
  4673.3   76.21  4693.3   75.26  4753.3   75.61  4943.3   74.96  4994.7   74.49
    4995   73.38  4996.5   70.38  5003.5   70.38    5005   73.38  5034.7   75.32
  5214.7   74.51  5244.7   75.83  5304.9      81  5322.2   82.48
#Mann= 5 , 1 , 0
  4563.3      10       0  4568.9     .15       0    4995    .045       0
    5005     .15       0  5304.9      10       0
Bank Sta=4995,5005
XS Rating Curve= 0 ,0
Exp/Cntr=0.3,0.1

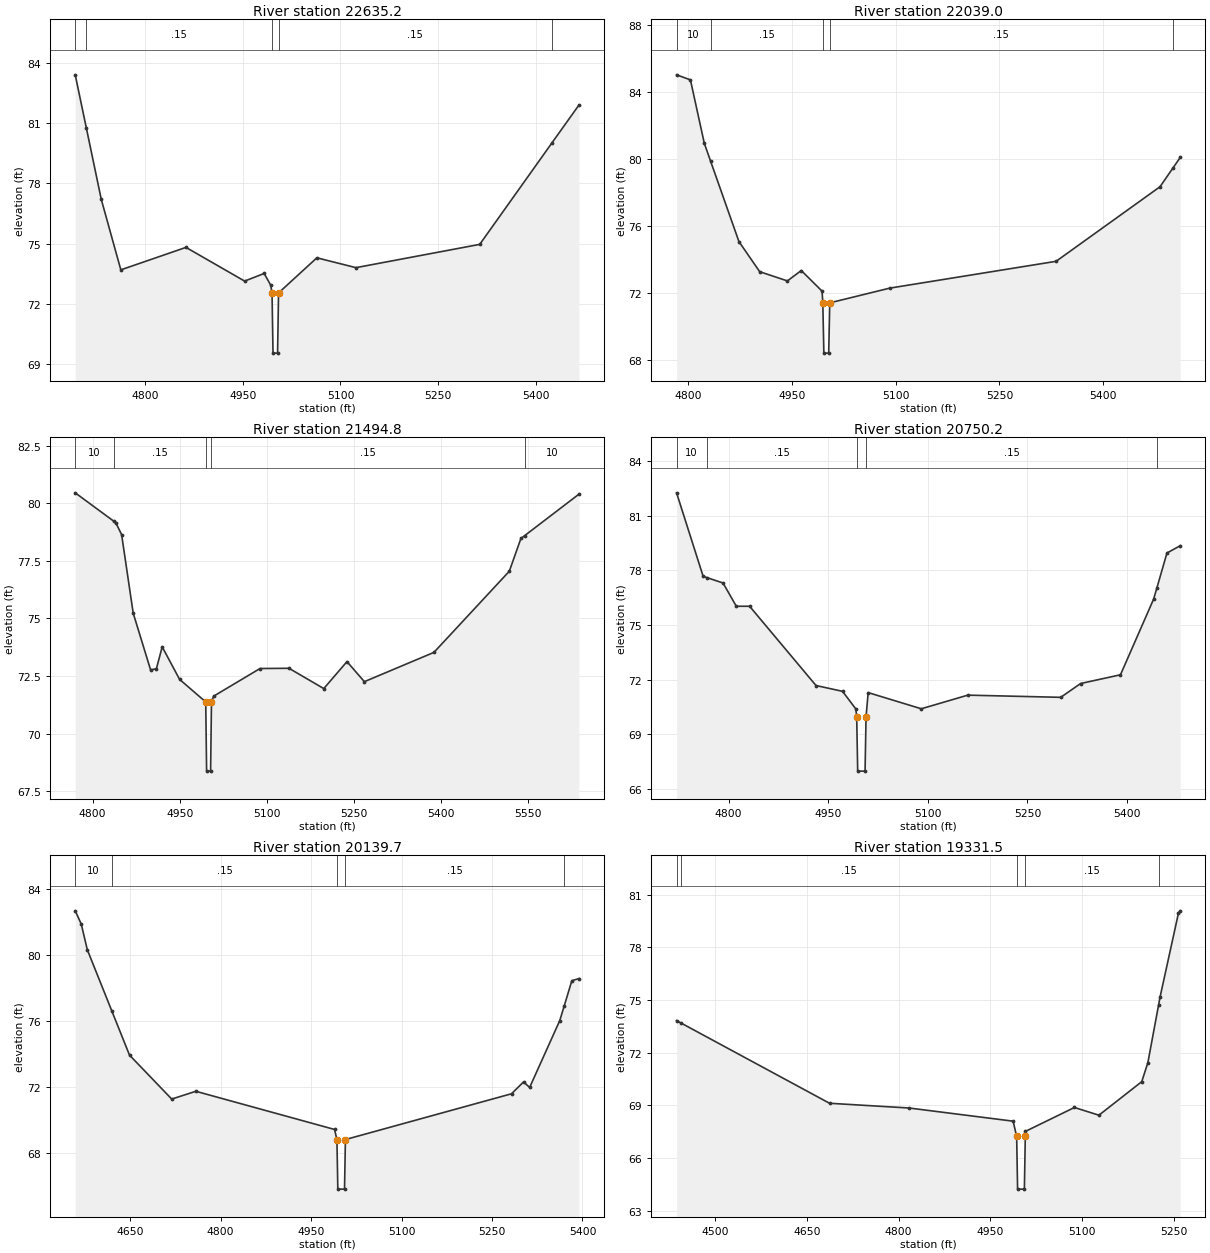
Type RM Length L Ch R = 1 ,22635.2 ,596.2,596.2,596.2
BEGIN DESCRIPTION:
Fort Run 26.0
END DESCRIPTION:
XS GIS Cut Line= 3
   0.06620433447  0.302841192265  0.081637033964  0.300719196084
  0.104786083207  0.300140469853
#Sta/Elev= 17
  4692.9   83.41  4709.9   80.77  4732.9    77.2  4762.9   73.69  4862.9   74.81
  4952.9   73.13  4982.9   73.51  4992.9   72.93    4995   72.54  4996.5   69.54
  5003.5   69.54    5005   72.54  5063.8   74.29  5123.8    73.8  5313.8   74.96
  5424.9   80.03    5466    81.9
#Mann= 5 , 1 , 0
  4692.9      10       0  4709.9     .15       0    4995    .045       0
    5005     .15       0  5424.9      10       0
Bank Sta=4995,5005
XS Rating Curve= 0 ,0
Exp/Cntr=0.3,0.1

Type RM Length L Ch R = 1 ,22039.0 ,544.2,544.2,544.2
BEGIN DESCRIPTION:
Fort Run 25.0
END DESCRIPTION:
XS GIS Cut Line= 3
  0.067940513163  0.322903701608  0.078472525186  0.325756535895
  0.103435722002  0.331005868843
#Sta/Elev= 18
  4783.9   85.03  4803.9   84.73  4823.9   80.95  4832.9   79.89  4873.9   75.08
  4903.9   73.28  4943.9   72.73  4963.9   73.35  4993.9   72.12    4995   71.42
  4996.5   68.42  5003.5   68.42    5005   71.42  5091.7    72.3  5331.7    73.9
  5481.7   78.35  5499.9   79.44  5510.9    80.1
#Mann= 5 , 1 , 0
  4783.9      10       0  4832.9     .15       0    4995    .045       0
    5005     .15       0  5499.9      10       0
Bank Sta=4995,5005
XS Rating Curve= 0 ,0
Exp/Cntr=0.3,0.1

Type RM Length L Ch R = 1 ,21494.8 ,744.6,744.6,744.6
BEGIN DESCRIPTION:
Fort Run 24.0
END DESCRIPTION:
XS GIS Cut Line= 3
  0.057523441004  0.339108036078  0.066783060701  0.345859842107
  0.097648459691  0.354540735573
#Sta/Elev= 24
  4769.9   80.45  4836.9   79.21  4839.9   79.15  4849.9   78.64  4869.9   75.23
  4899.9   72.77  4909.9   72.82  4919.9   73.77  4949.9   72.36    4995   71.38
  4996.5   68.38  5003.4   68.38  5004.9   71.38  5008.6   71.63  5088.6   72.83
  5138.6   72.84  5198.6   71.96  5238.6   73.13  5268.6   72.26  5388.6   73.53
  5518.6   77.05  5538.6   78.47  5544.9   78.59  5638.6   80.39
#Mann= 5 , 1 , 0
  4769.9      10       0  4836.9     .15       0    4995    .045       0
  5004.9     .15       0  5544.9      10       0
Bank Sta=4995,5004.9
XS Rating Curve= 0 ,0
Exp/Cntr=0.3,0.1

Type RM Length L Ch R = 1 ,20750.2 ,610.5,610.5,610.5
BEGIN DESCRIPTION:
Fort Run 23.0
END DESCRIPTION:
XS GIS Cut Line= 3
  0.050555439614  0.374360382717  0.065016088256  0.374360382717
  0.091527277431  0.372954486321
#Sta/Elev= 23
  4721.6   82.27  4761.6   77.68  4766.9   77.61  4791.6   77.31  4811.6   76.03
  4831.6   76.03  4931.6   71.67  4971.6   71.35  4991.6   70.38  4992.9   69.96
  4994.4   66.96  5005.5   66.96    5007   69.96  5010.2   71.28  5090.2   70.39
  5160.2   71.14  5300.2   71.02  5330.2   71.78  5390.2   72.26  5440.2   76.43
  5444.9   77.02  5460.2   78.96  5480.2   79.36
#Mann= 5 , 1 , 0
  4721.6      10       0  4766.9     .15       0  4992.9    .045       0
    5007     .15       0  5444.9      10       0
Bank Sta=4992.9,5007
XS Rating Curve= 0 ,0
Exp/Cntr=0.3,0.1

Type RM Length L Ch R = 1 ,20139.7 ,808.2,808.2,808.2
BEGIN DESCRIPTION:
Fort Run 22.0
END DESCRIPTION:
XS GIS Cut Line= 3
            0.05  0.397752294158  0.072045570234  0.400469887208
  0.091668288637  0.400260107827
#Sta/Elev= 19
    4559   82.66    4569   81.86    4579   80.31  4619.9   76.58    4649   73.93
    4719   71.27    4759   71.74    4989   69.43  4992.9   68.82  4994.4   65.82
  5005.5   65.82    5007   68.82  5282.4   71.59  5302.4   72.31  5312.4   71.97
  5362.4   76.02  5369.9   76.92  5382.4   78.43  5394.1   78.56
#Mann= 5 , 1 , 0
    4559      10       0  4619.9     .15       0  4992.9    .045       0
    5007     .15       0  5369.9      10       0
Bank Sta=4992.9,5007
XS Rating Curve= 0 ,0
Exp/Cntr=0.3,0.1

Type RM Length L Ch R = 1 ,19331.5 ,490.6,490.6,490.6
BEGIN DESCRIPTION:
Fort Run 21.0
END DESCRIPTION:
XS GIS Cut Line= 3
  0.055787262311  0.441156761488  0.082601577683   0.43286168551
  0.093790284817  0.425916970737
#Sta/Elev= 18
  4437.1   73.83  4444.9   73.68  4687.1   69.12  4817.1   68.85  4987.1    68.1
  4992.9   67.23  4994.4   64.23  5005.5   64.23    5007   67.23  5007.3   67.52
  5087.3   68.88  5127.3   68.44  5197.3   70.35  5207.3   71.43  5224.9   74.73
  5227.3   75.18  5257.3   79.95  5260.2   80.08
#Mann= 5 , 1 , 0
  4437.1      10       0  4444.9     .15       0  4992.9    .045       0
    5007     .15       0  5224.9      10       0
Bank Sta=4992.9,5007
XS Rating Curve= 0 ,0
Exp/Cntr=0.3,0.1

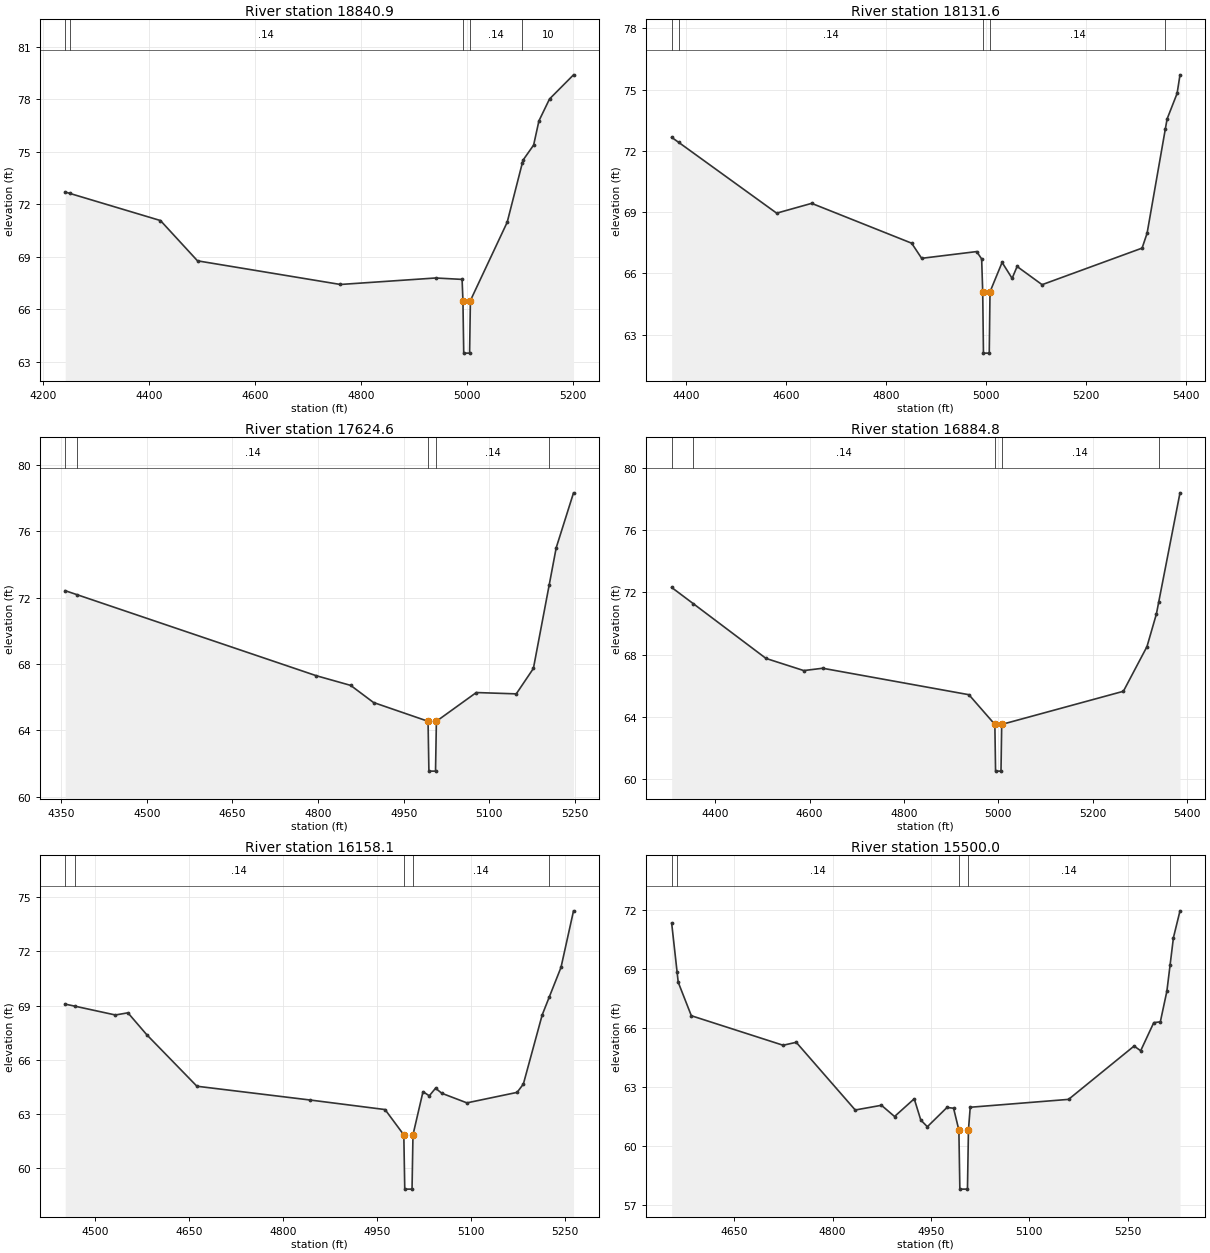
Type RM Length L Ch R = 1 ,18840.9 ,709.3,709.3,709.3
BEGIN DESCRIPTION:
Fort Run 20.0
END DESCRIPTION:
XS GIS Cut Line= 3
  0.067554695676  0.468356894348  0.098613003409  0.446751115055
  0.107486805619  0.441542578976
#Sta/Elev= 18
  4241.3    72.7  4249.9   72.62  4421.3   71.07  4491.3   68.77  4761.3   67.42
  4941.3   67.79  4991.3   67.71  4992.9    66.5  4994.4    63.5  5005.5    63.5
    5007    66.5  5076.5   70.97  5104.9   74.33  5106.5   74.52  5126.5   75.38
  5136.5   76.76  5156.5   78.01  5201.9   79.39
#Mann= 5 , 1 , 0
  4241.3      10       0  4249.9     .14       0  4992.9    .045       0
    5007     .14       0  5104.9      10       0
Bank Sta=4992.9,5007
XS Rating Curve= 0 ,0
Exp/Cntr=0.3,0.1

Type RM Length L Ch R = 1 ,18131.6 ,507,507,507
BEGIN DESCRIPTION:
Fort Run 19.0
END DESCRIPTION:
XS GIS Cut Line= 3
  0.083180303914  0.484368320074  0.111209826971   0.46976049528
  0.129864219886  0.464691628218
#Sta/Elev= 22
  4370.6   72.66  4384.9   72.41  4580.6   68.95  4650.6   69.43  4850.6   67.48
  4870.6   66.74  4980.6   67.07  4990.6   66.71  4992.7    65.1  4994.2    62.1
  5005.8    62.1  5007.3    65.1  5031.5   66.54  5051.5   65.76  5061.5   66.34
  5111.5   65.45  5311.5   67.24  5321.5   67.97  5357.9   73.06  5361.5   73.56
  5381.5   74.81  5387.3   75.72
#Mann= 5 , 1 , 0
  4370.6      10       0  4384.9     .14       0  4992.7    .045       0
  5007.3     .14       0  5357.9      10       0
Bank Sta=4992.7,5007.3
XS Rating Curve= 0 ,0
Exp/Cntr=0.3,0.1

Type RM Length L Ch R = 1 ,17624.6 ,739.8,739.8,739.8
BEGIN DESCRIPTION:
Fort Run 18.0
END DESCRIPTION:
XS GIS Cut Line= 3
  0.102278269539  0.500958472031  0.127742223706  0.481474688919
  0.134108212247  0.470671799273
#Sta/Elev= 15
  4357.2   72.41  4377.9   72.17  4797.2   67.29  4857.2   66.71  4897.2   65.68
  4992.7   64.55  4994.2   61.55  5005.8   61.55  5007.3   64.55  5077.2   66.28
  5147.2    66.2  5177.2   67.73  5204.9   72.76  5217.2      75  5247.5    78.3
#Mann= 5 , 1 , 0
  4357.2      10       0  4377.9     .14       0  4992.7    .045       0
  5007.3     .14       0  5204.9      10       0
Bank Sta=4992.7,5007.3
XS Rating Curve= 0 ,0
Exp/Cntr=0.3,0.1

Type RM Length L Ch R = 1 ,16884.8 ,726.7,726.7,726.7
BEGIN DESCRIPTION:
Fort Run 17.0
END DESCRIPTION:
XS GIS Cut Line= 3
  0.124655683807  0.527386969917  0.148968187312  0.502296954723
  0.160536710133  0.484561228818
#Sta/Elev= 15
  4307.7   72.31  4353.9   71.26  4507.7   67.75  4587.7   66.97  4627.7   67.12
  4937.7   65.42  4992.7   63.51  4994.2   60.51  5005.7   60.51  5007.2   63.51
  5265.1   65.64  5315.1   68.51  5335.1   70.61  5339.9   71.36  5385.1   78.39
#Mann= 5 , 1 , 0
  4307.7      10       0  4353.9     .14       0  4992.7    .045       0
  5007.2     .14       0  5339.9      10       0
Bank Sta=4992.7,5007.2
XS Rating Curve= 0 ,0
Exp/Cntr=0.3,0.1

Type RM Length L Ch R = 1 ,16158.1 ,658.1,658.1,658.1
BEGIN DESCRIPTION:
Fort Run 16.0
END DESCRIPTION:
XS GIS Cut Line= 3
  0.144911101894  0.543398395643  0.175479376487  0.522381188947
  0.184071576863  0.511568452934
#Sta/Elev= 23
  4452.8   69.08  4467.9   68.97  4532.8   68.48  4552.8    68.6  4582.8   67.39
  4662.8   64.54  4842.8   63.78  4962.8   63.25  4992.7   61.85  4994.2   58.85
  5005.8   58.85  5007.3   61.85  5023.3   64.24  5033.3   64.01  5043.3   64.43
  5053.3   64.15  5093.3   63.62  5173.3    64.2  5183.3   64.66  5213.3   68.48
  5224.9    69.5  5243.3   71.11  5263.3   74.24
#Mann= 5 , 1 , 0
  4452.8      10       0  4467.9     .14       0  4992.7    .045       0
  5007.3     .14       0  5224.9      10       0
Bank Sta=4992.7,5007.3
XS Rating Curve= 0 ,0
Exp/Cntr=0.3,0.1

Type RM Length L Ch R = 1 ,15500.0 ,914.6,914.6,914.6
BEGIN DESCRIPTION:
Fort Run 15.0
END DESCRIPTION:
XS GIS Cut Line= 3
  0.179055949527  0.555358737751  0.198428768152  0.544283660222
  0.206641899874  0.526808243685
#Sta/Elev= 28
  4554.6   71.33  4562.9   68.84  4564.6   68.33  4584.6   66.63  4724.6   65.13
  4744.6   65.28  4834.6   61.84  4874.6   62.08  4894.6   61.51  4924.6   62.41
  4934.6   61.33  4944.6   60.99  4974.6   61.97  4984.6   61.93  4992.7   60.82
  4994.2   57.82  5005.8   57.82  5007.3   60.82    5010   61.98    5160   62.38
    5260   65.09    5270   64.85    5290   66.28    5300   66.32    5310   67.88
  5314.9   69.21    5320    70.6    5330   71.96
#Mann= 5 , 1 , 0
  4554.6      10       0  4562.9     .14       0  4992.7    .045       0
  5007.3     .14       0  5314.9      10       0
Bank Sta=4992.7,5007.3
XS Rating Curve= 0 ,0
Exp/Cntr=0.3,0.1

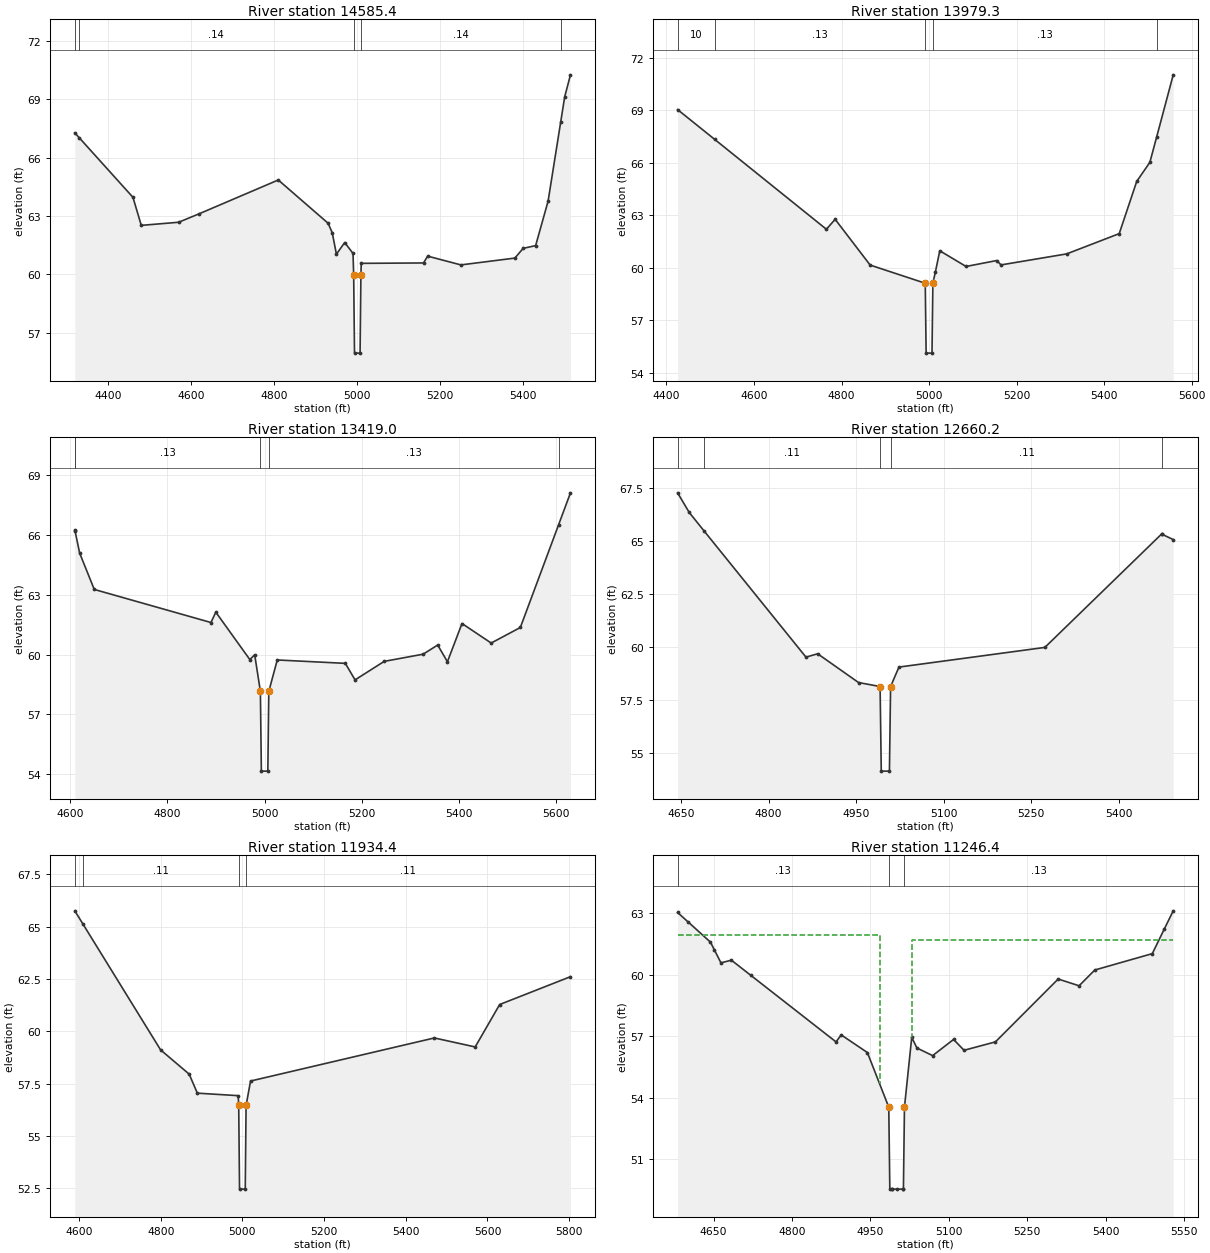
Type RM Length L Ch R = 1 ,14585.4 ,606.1,606.1,606.1
BEGIN DESCRIPTION:
Fort Run 14.0
END DESCRIPTION:
XS GIS Cut Line= 3
  0.235964028915  0.595097938951  0.233263306503  0.561146000062
  0.231141310322  0.535489137151
#Sta/Elev= 27
  4319.7   67.27  4329.9   67.03  4459.7   63.96  4479.7   62.52  4569.7   62.68
  4619.7   63.12  4809.7   64.85  4929.7   62.63  4939.7   62.14  4949.7   61.04
  4969.7   61.64  4989.7   61.08  4991.3   59.96  4993.3   55.96  5006.7   55.96
  5008.7   59.96  5009.5   60.57  5159.5   60.59  5169.5   60.94  5249.5   60.49
  5379.5   60.84  5399.5   61.34  5429.5   61.48  5459.5   63.76  5489.9   67.83
  5499.5   69.12  5513.4   70.25
#Mann= 5 , 1 , 0
  4319.7      10       0  4329.9     .14       0  4991.3    .045       0
  5008.7     .14       0  5489.9      10       0
Bank Sta=4991.3,5008.7
XS Rating Curve= 0 ,0
Exp/Cntr=0.3,0.1

Type RM Length L Ch R = 1 ,13979.3 ,560.3,560.3,560.3
BEGIN DESCRIPTION:
Fort Run 13.0
END DESCRIPTION:
XS GIS Cut Line= 3
  0.251782545897  0.600499383774   0.25872726067  0.567704897347
  0.270494694035  0.542048034437
#Sta/Elev= 20
  4425.4   69.05  4509.9   67.35  4765.4    62.2  4785.4   62.77  4865.4   60.15
  4991.3   59.11  4993.3   55.11  5006.7   55.11  5008.7   59.11  5014.5   59.76
  5024.5   60.97  5084.5   60.07  5154.5   60.41  5164.5   60.16  5314.5   60.79
  5434.5   61.95  5474.5   64.94  5504.5   66.03  5519.9   67.47  5557.9   71.04
#Mann= 5 , 1 , 0
  4425.4      10       0  4509.9     .13       0  4991.3    .042       0
  5008.7     .13       0  5519.9      10       0
Bank Sta=4991.3,5008.7
XS Rating Curve= 0 ,0
Exp/Cntr=0.3,0.1

Type RM Length L Ch R = 1 ,13419.0 ,758.8,758.8,758.8
BEGIN DESCRIPTION:
Fort Run 12.0
END DESCRIPTION:
XS GIS Cut Line= 3
  0.281876309912  0.596448300157  0.284577032324    0.5767716083
  0.278789770013  0.546099118054
#Sta/Elev= 24
  4609.6   66.25  4609.9   66.22  4619.6   65.09  4649.6   63.27  4889.6   61.61
  4899.6   62.13  4969.6   59.75  4979.6   59.99  4991.3   58.15  4993.3   54.15
  5006.6   54.15  5008.6   58.15    5026   59.73    5166   59.56    5186   58.73
    5246   59.66    5326   60.02    5356   60.48    5376   59.64    5406   61.56
    5466   60.58    5526   61.36  5604.9   66.53  5629.1   68.12
#Mann= 5 , 1 , 0
  4609.6      10       0  4609.9     .13       0  4991.3    .042       0
  5008.6     .13       0  5604.9      10       0
Bank Sta=4991.3,5008.6
XS Rating Curve= 0 ,0
Exp/Cntr=0.3,0.1

Type RM Length L Ch R = 1 ,12660.2 ,725.8,725.8,725.8
BEGIN DESCRIPTION:
Fort Run 11.0
END DESCRIPTION:
XS GIS Cut Line= 3
  0.298466461869  0.591239764077  0.315635340058  0.585838319254
  0.338977298044   0.57310634217
#Sta/Elev= 15
    4644   67.29    4664   66.36  4689.9   65.47    4864   59.52    4884   59.68
    4954   58.32    4991   58.13    4993   54.13    5007   54.13    5009   58.13
  5023.3   59.05  5273.3   59.98  5473.3   65.34  5474.9   65.32  5493.3   65.08
#Mann= 5 , 1 , 0
    4644      10       0  4689.9     .11       0    4991    .041       0
    5009     .11       0  5474.9      10       0
Bank Sta=4991,5009
XS Rating Curve= 0 ,0
Exp/Cntr=0.3,0.1

Type RM Length L Ch R = 1 ,11934.4 ,688,688,688
BEGIN DESCRIPTION:
Fort Run 10.0
END DESCRIPTION:
XS GIS Cut Line= 3
  0.309441218761  0.623605729436  0.329324610643  0.618383828537
   0.36810651834  0.607637007291
#Sta/Elev= 15
  4589.7   65.76  4608.9   65.15  4799.7   59.11  4869.7   57.95  4889.7   57.04
  4989.7   56.92    4991   56.45    4993   52.45    5007   52.45    5009   56.45
    5020   57.62    5470   59.68    5570   59.25    5630   61.28  5803.3   62.61
#Mann= 4 , 1 , 0
  4589.7      10       0  4608.9     .11       0    4991    .041       0
    5009     .11       0
Bank Sta=4991,5009
XS Rating Curve= 0 ,0
Exp/Cntr=0.5,0.3

Type RM Length L Ch R = 1 ,11246.4 ,96,96,96
BEGIN DESCRIPTION:
Upstream Section of Bridge/Culvert/Weir
END DESCRIPTION:
XS GIS Cut Line= 3
  0.302564009041   0.64556209721  0.330728685619  0.650384815802
  0.364873533252  0.655786260625
#Sta/Elev= 30
  4581.2   63.05  4601.2   62.59  4644.1    61.6  4651.2   61.24  4664.1   60.59
  4684.1   60.72  4721.2   59.98  4884.1   56.73  4894.1   57.07  4944.1   56.21
    4985   53.54    4987   49.54  4991.2   49.54  4991.3   49.54    5000   49.54
  5011.3   49.54    5013   49.54    5015   53.54  5028.9   56.95  5038.9   56.43
  5068.9   56.06  5108.9   56.85  5128.9   56.32  5188.9   56.73  5308.9    59.8
  5348.9   59.47  5378.9   60.24  5488.9   61.04  5511.6   62.23  5528.9   63.13
#Mann= 3 ,-1 , 0
  4581.2     .13       0    4985    .048       0    5015     .13       0
#XS Ineff= 2 , 0
       0    4968   61.94    5030       0    61.7
Permanent Ineff=
       T       T
Bank Sta=4985,5015
XS Rating Curve= 0 ,0
Exp/Cntr=0.5,0.3