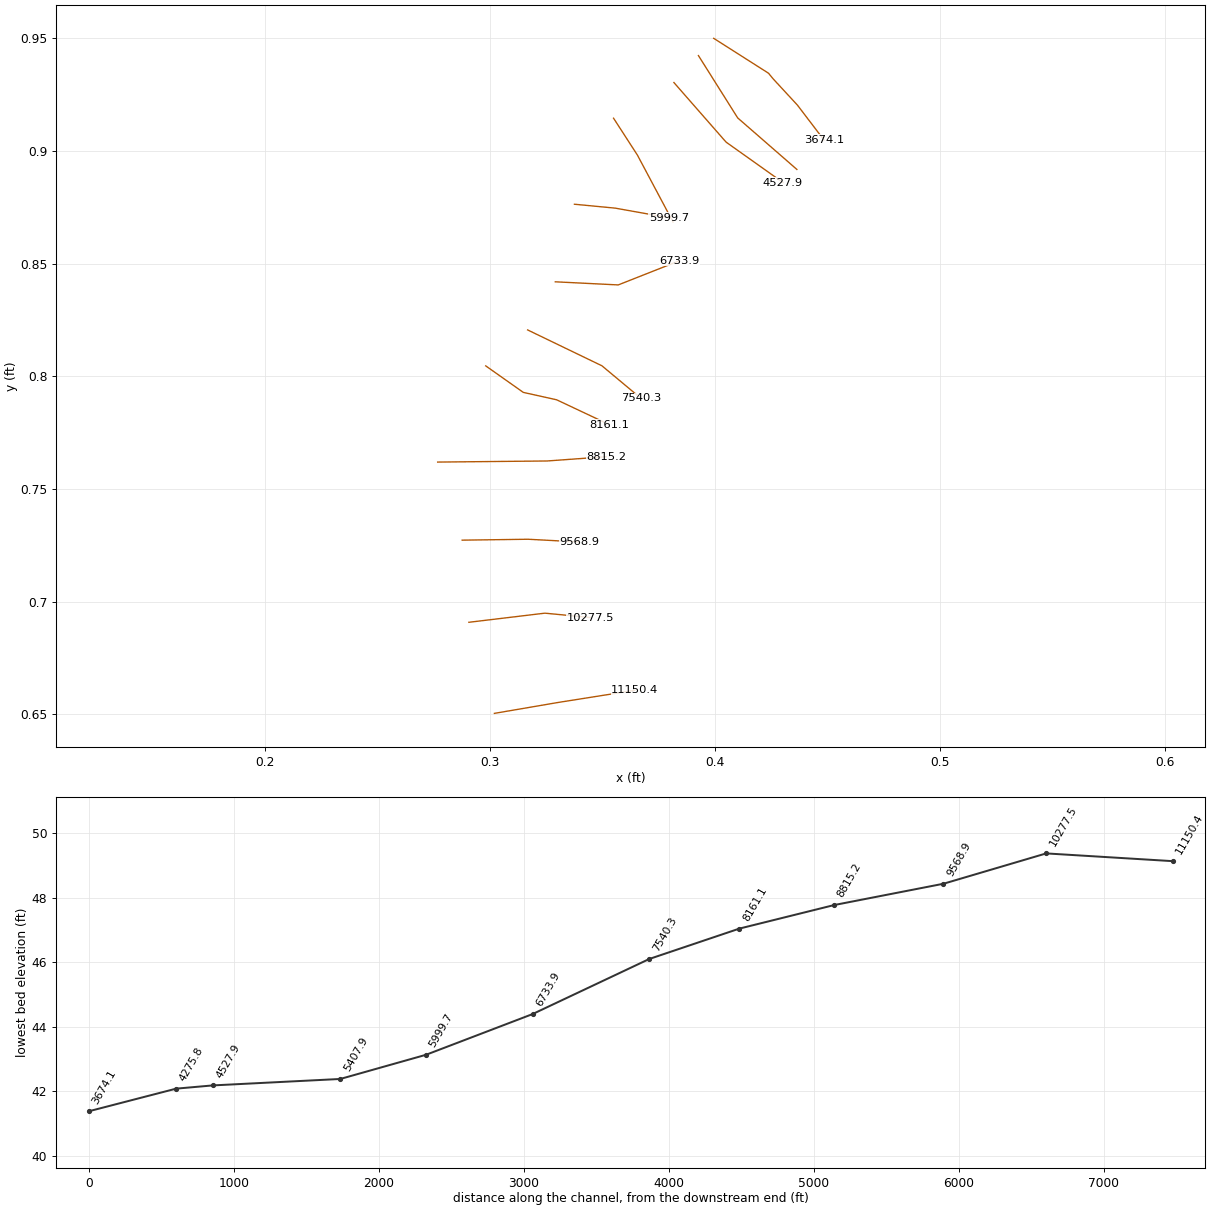
HEC-RAS study lds_fort_run_upper.prj: Fort Run

--- lds_fort_run_upper.g01 (geometry) --- (continued)

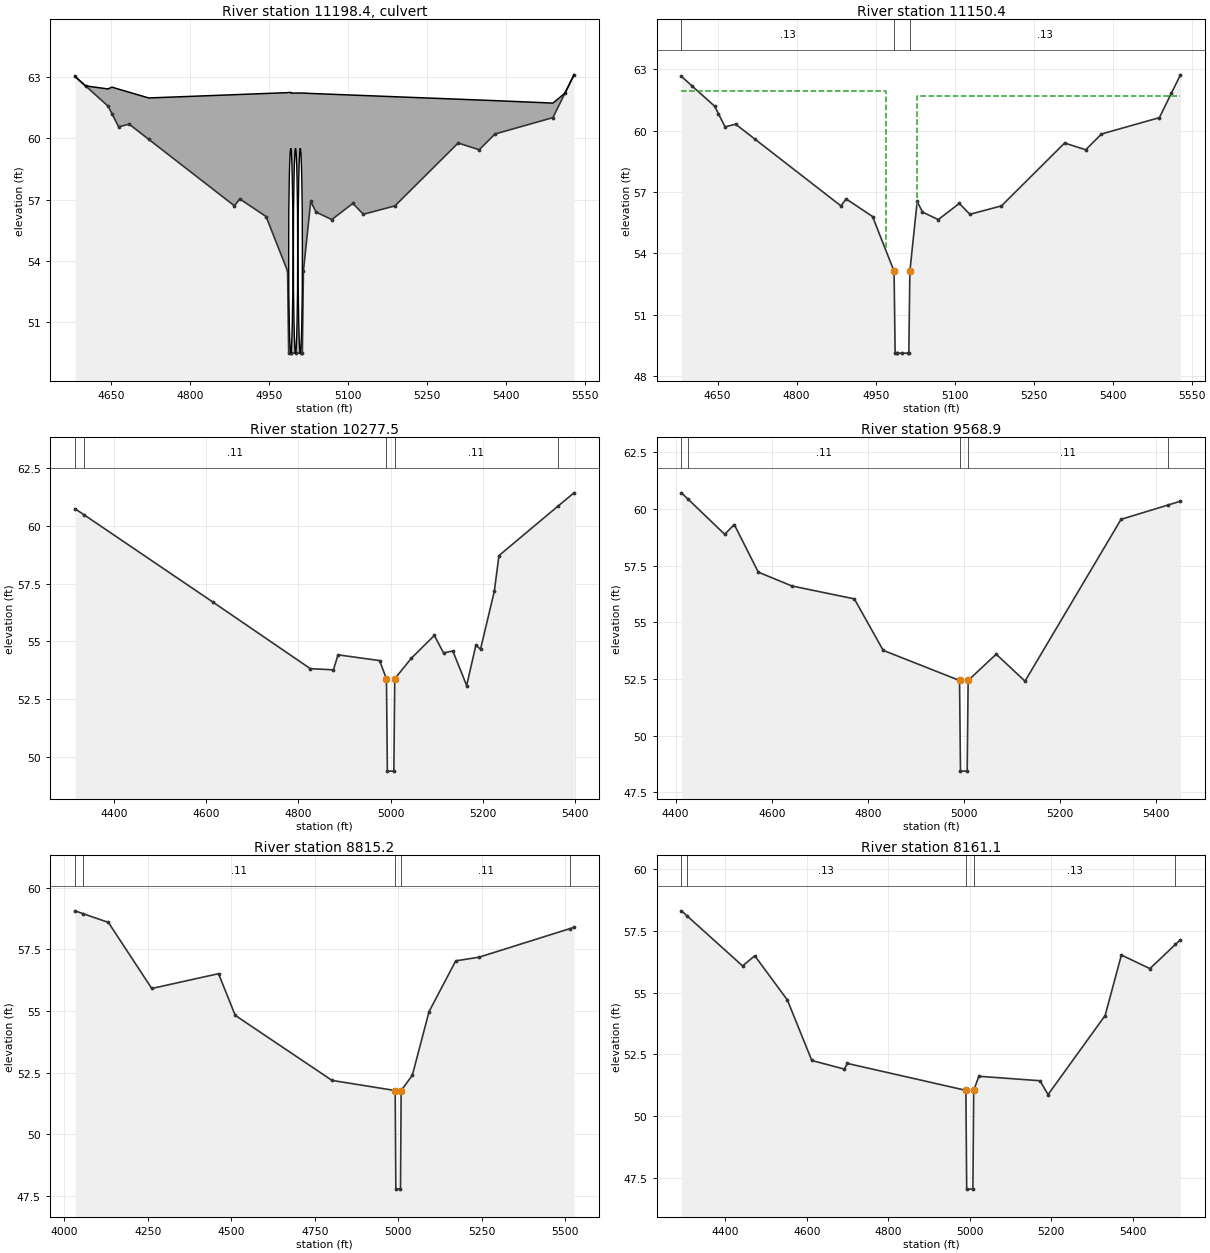
Type RM Length L Ch R = 2 ,11198.4 ,,,
BEGIN DESCRIPTION:
Saulston Rd-TOR
Structure ID: Saulston Rd-Culvert
Approximate Survey Structure
END DESCRIPTION:
Bridge Culvert--1,0,-1,-1, 0
Deck Dist Width WeirC Skew NumUp NumDn MinLoCord MaxHiCord MaxSubmerge Is_Ogee
10,76,3,0, 30, 30, , , 0.95, 0, 1,1,,
  4581.2  4601.2  4644.1  4651.2  4664.1  4684.1  4721.2  4884.1  4894.1  4944.1
    4985    4987  4991.2  4991.3    5000  5011.3    5013    5015  5028.9  5038.9
  5068.9  5108.9  5128.9  5188.9  5308.9  5348.9  5378.9  5488.9  5511.6  5528.9
   63.01   62.55    62.4   62.49   62.39   62.24   61.96   62.12   62.13   62.18
   62.22   62.23   62.23    62.2    62.2    62.2    62.2    62.2   62.18   62.17
   62.14    62.1   62.08   62.02    61.9   61.86   61.83   61.71   62.19   63.09
   63.01   62.55   61.56    61.2   60.55   60.68   59.94   56.69   57.03   56.17
    53.5    49.5    49.5    49.5    49.5    49.5    49.5    53.5   56.91   56.39
   56.02   56.81   56.28   56.69   59.76   59.43    60.2      61   62.19   63.09
  4581.2  4601.2  4644.1  4651.2  4664.1  4684.1  4721.2  4884.1  4894.1  4944.1
    4985    4987  4991.2  4991.3    5000  5011.3    5013    5015  5028.9  5038.9
  5068.9  5108.9  5128.9  5188.9  5308.9  5348.9  5378.9  5488.9  5511.6  5528.9
   62.82   62.37    62.4   62.49   62.39   62.24   61.96   62.12   62.13   62.18
   62.22   62.23   62.23    62.2    62.2    62.2    62.2    62.2   62.18   62.17
   62.14    62.1   62.08   62.02    61.9   61.86   61.83   61.71   62.01    62.9
   62.63   62.17   61.18   60.82   60.17    60.3   59.56   56.31   56.65   55.79
   53.12   49.12   49.12   49.12   49.12   49.12   49.12   53.12   56.53   56.01
   55.64   56.43    55.9   56.31   59.38   59.05   59.82   60.62   61.81   62.71
BR Coef= 1 , 0 , 0 ,1.25, 0 ,,,0.8,-1,2,0,
WSPro=,,,, 1 ,,,, 0 ,,,, 0 ,,,,-1 ,-1 ,-1 , 0 , 0 , 0 , 0 , 0
Culvert=4,10,8,76,0.015,0.9,1,29,1,49.5,4991.04,49.12,4991.04,Culvert #1  , 0 ,10
Culvert Bottom n=0.015
Culvert=4,10,8,76,0.015,0.9,1,29,1,49.5,5000.04,49.12,5000.04,Culvert #2  , 0 ,10
Culvert Bottom n=0.015
Culvert=4,10,8,76,0.015,0.9,1,29,1,49.5,5009.04,49.12,5009.04,Culvert #3  , 0 ,10
Culvert Bottom n=0.015
BR U #Sta/Elev= 30
  4581.2   63.01  4601.2   62.55  4644.1   61.56  4651.2    61.2  4664.1   60.55
  4684.1   60.68  4721.2   59.94  4884.1   56.69  4894.1   57.03  4944.1   56.17
    4985    53.5    4987    49.5  4991.2    49.5  4991.3    49.5    5000    49.5
  5011.3    49.5    5013    49.5    5015    53.5  5028.9   56.91  5038.9   56.39
  5068.9   56.02  5108.9   56.81  5128.9   56.28  5188.9   56.69  5308.9   59.76
  5348.9   59.43  5378.9    60.2  5488.9      61  5511.6   62.19  5528.9   63.09
BR U #Mann= 3
  4581.2     .13    4985    .048    5015     .13
BR U Banks=4985,5015
BR D #Sta/Elev= 30
  4581.2   62.63  4601.2   62.17  4644.1   61.18  4651.2   60.82  4664.1   60.17
  4684.1    60.3  4721.2   59.56  4884.1   56.31  4894.1   56.65  4944.1   55.79
    4985   53.12    4987   49.12  4991.2   49.12  4991.3   49.12    5000   49.12
  5011.3   49.12    5013   49.12    5015   53.12  5028.9   56.53  5038.9   56.01
  5068.9   55.64  5108.9   56.43  5128.9    55.9  5188.9   56.31  5308.9   59.38
  5348.9   59.05  5378.9   59.82  5488.9   60.62  5511.6   61.81  5528.9   62.71
BR D #Mann= 3
  4581.2     .13    4985    .048    5015     .13
BR D Banks=4985,5015
BC Design=,, 0 ,, 0 ,,,,,,
BC HTab HWMax=63.13
BC Use User HTab Curves=0
BC User HTab FreeFlow(D)= 0

Type RM Length L Ch R = 1 ,11150.4 ,872.9,872.9,872.9
BEGIN DESCRIPTION:
Downstream Section of Bridge/Culvert/Weir
END DESCRIPTION:
XS GIS Cut Line= 3
  0.302085264445  0.650347772232  0.330249941023  0.655170490824
  0.364394788656  0.660571935648
#Sta/Elev= 30
  4581.2   62.64  4601.2   62.18  4644.1   61.19  4651.2   60.83  4664.1   60.18
  4684.1   60.31  4721.2   59.57  4884.1   56.32  4894.1   56.66  4944.1    55.8
    4985   53.13    4987   49.13  4991.2   49.13  4991.3   49.13    5000   49.13
  5011.3   49.13    5013   49.13    5015   53.13  5028.9   56.54  5038.9   56.02
  5068.9   55.65  5108.9   56.44  5128.9   55.91  5188.9   56.32  5308.9   59.39
  5348.9   59.06  5378.9   59.83  5488.9   60.63  5511.6   61.82  5528.9   62.72
#Mann= 3 ,-1 , 0
  4581.2     .13       0    4985    .048       0    5015     .13       0
#XS Ineff= 2 , 0
       0    4970   61.94    5028       0    61.7
Permanent Ineff=
       F       F
Bank Sta=4985,5015
XS Rating Curve= 0 ,0
Exp/Cntr=0.5,0.3

Type RM Length L Ch R = 1 ,10277.5 ,708.6,708.6,708.6
BEGIN DESCRIPTION:
Fort Run 9.0
END DESCRIPTION:
XS GIS Cut Line= 3
  0.290750112122  0.690780675819  0.324509142267  0.694831759437
  0.344588628653  0.692896337508
#Sta/Elev= 22
  4316.1   60.74  4334.9   60.49  4616.1   56.68  4826.1   53.81  4876.1   53.76
  4886.1   54.41  4976.1   54.16    4991   53.37    4993   49.37    5007   49.37
    5009   53.37  5044.8   54.26  5094.8   55.25  5114.8   54.49  5134.8   54.58
  5164.8   53.08  5184.8   54.83  5194.8   54.65  5224.8   57.17  5234.8   58.71
  5361.9   60.84  5397.4   61.43
#Mann= 5 , 1 , 0
  4316.1      10       0  4334.9     .11       0    4991    .041       0
    5009     .11       0  5361.9      10       0
Bank Sta=4991,5009
XS Rating Curve= 0 ,0
Exp/Cntr=0.3,0.1

Type RM Length L Ch R = 1 ,9568.9  ,753.7,753.7,753.7
BEGIN DESCRIPTION:
Fort Run 8.0
END DESCRIPTION:
XS GIS Cut Line= 3
  0.287750245799  0.727240378031  0.317073227766  0.727642062716
  0.339768412439  0.726437008662
#Sta/Elev= 17
  4412.1   60.71  4424.9   60.45  4502.1   58.88  4522.1   59.31  4572.1   57.21
  4642.1    56.6  4772.1   56.03  4832.1   53.76  4991.1   52.43  4993.1   48.43
    5007   48.43    5009   52.43  5067.4   53.59  5127.4    52.4  5327.4   59.54
  5424.9   60.17  5451.1   60.34
#Mann= 5 , 1 , 0
  4412.1      10       0  4424.9     .11       0  4991.1    .041       0
    5009     .11       0  5424.9      10       0
Bank Sta=4991.1,5009
XS Rating Curve= 0 ,0
Exp/Cntr=0.3,0.1

Type RM Length L Ch R = 1 ,8815.2  ,654.1,654.1,654.1
BEGIN DESCRIPTION:
Fort Run 7.0
END DESCRIPTION:
XS GIS Cut Line= 3
  0.276886371742  0.761900348304   0.32550860614  0.762387787923
  0.351709275127  0.764278907164
#Sta/Elev= 17
  4031.8   59.06  4054.9   58.95  4131.8   58.59  4261.8   55.91  4461.8   56.51
  4511.8   54.82  4801.8   52.18    4991   51.77    4993   47.77  5006.9   47.77
  5008.9   51.77  5042.4   52.39  5092.4   54.97  5172.4   57.03  5242.4   57.18
  5514.9   58.34  5526.7   58.39
#Mann= 5 , 1 , 0
  4031.8      10       0  4054.9     .11       0    4991    .041       0
  5008.9     .11       0  5514.9      10       0
Bank Sta=4991,5008.9
XS Rating Curve= 0 ,0
Exp/Cntr=0.3,0.1

Type RM Length L Ch R = 1 ,8161.1  ,620.8,620.8,620.8
BEGIN DESCRIPTION:
Fort Run 6.0
END DESCRIPTION:
XS GIS Cut Line= 4
  0.298237525504  0.804602655828  0.314916452169  0.792834532734
  0.329717678346  0.789549952587  0.353059636333  0.778554154197
#Sta/Elev= 20
  4292.1   58.31  4304.9   58.12  4442.1   56.08  4472.1   56.49  4552.1    54.7
  4612.1   52.25  4692.1    51.9  4699.5   52.13  4990.4   51.04  4992.4   47.04
  5007.6   47.04  5009.6   51.04  5022.2   51.61  5172.2   51.43  5192.2   50.87
  5332.2   54.07  5372.2   56.52  5442.2   55.97  5504.9   56.95  5517.2   57.14
#Mann= 5 , 1 , 0
  4292.1      10       0  4304.9     .13       0  4990.4    .044       0
  5009.6     .13       0  5504.9      10       0
Bank Sta=4990.4,5009.6
XS Rating Curve= 0 ,0
Exp/Cntr=0.3,0.1

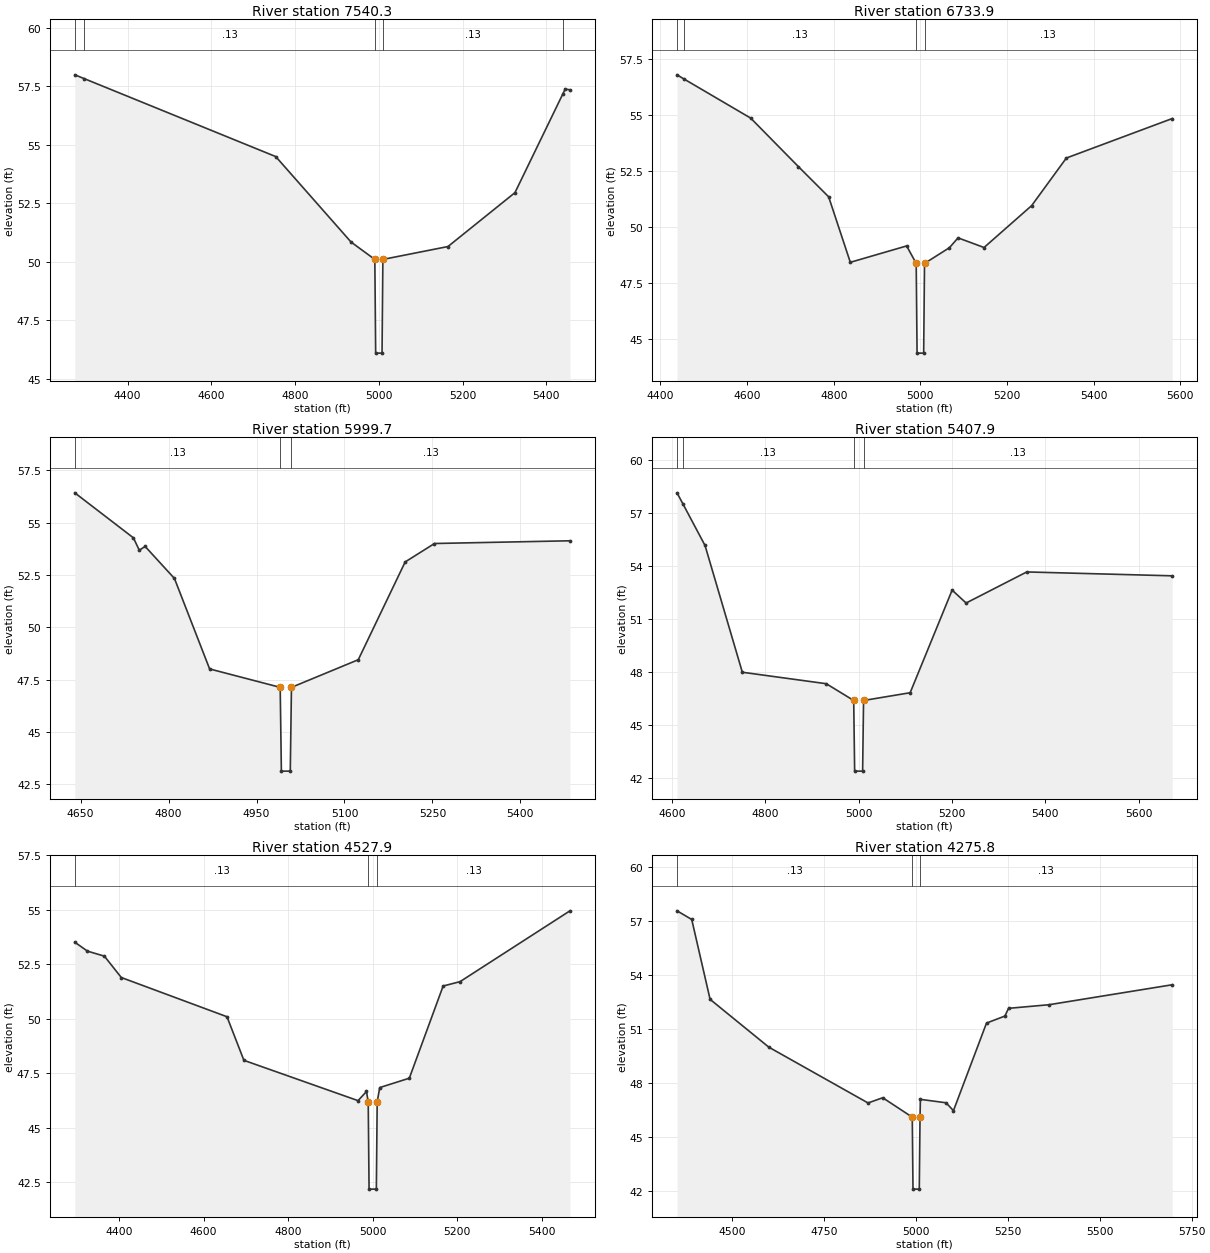
Type RM Length L Ch R = 1 ,7540.3  ,806.4,806.4,806.4
BEGIN DESCRIPTION:
Fort Run 5.0
END DESCRIPTION:
XS GIS Cut Line= 3
  0.316838361154  0.820561738555  0.349842178495  0.804638844224
  0.367212608674  0.790163485741
#Sta/Elev= 13
  4273.7   57.98  4295.9   57.82  4753.7   54.49  4933.7   50.84  4990.4    50.1
  4992.4    46.1  5007.6    46.1  5009.6    50.1  5165.1   50.65  5325.1   52.95
  5439.9   57.18  5445.1   57.37  5456.5   57.34
#Mann= 5 , 1 , 0
  4273.7      10       0  4295.9     .13       0  4990.4    .044       0
  5009.6     .13       0  5439.9      10       0
Bank Sta=4990.4,5009.6
XS Rating Curve= 0 ,0
Exp/Cntr=0.3,0.1

Type RM Length L Ch R = 1 ,6733.9  ,734.2,734.2,734.2
BEGIN DESCRIPTION:
Fort Run 4.0
END DESCRIPTION:
XS GIS Cut Line= 3
  0.329123768301   0.84192135545  0.357079857736  0.840537733261
   0.38431085281  0.851280750567
#Sta/Elev= 17
  4438.3    56.8  4453.9   56.62  4608.3   54.87  4718.3   52.71  4788.3   51.36
  4838.3   48.44  4968.3   49.17  4990.4   48.39  4992.4   44.39  5007.6   44.39
  5009.6   48.39    5067   49.09    5087   49.53    5147    49.1    5257   50.97
    5337   53.09  5581.3   54.85
#Mann= 4 , 1 , 0
  4438.3      10       0  4453.9     .13       0  4990.4    .044       0
  5009.6     .13       0
Bank Sta=4990.4,5009.6
XS Rating Curve= 0 ,0
Exp/Cntr=0.3,0.1

Type RM Length L Ch R = 1 ,5999.7  ,591.8,591.8,591.8
BEGIN DESCRIPTION:
Fort Run 3.0
END DESCRIPTION:
XS GIS Cut Line= 3
  0.337626936838  0.876358887247  0.355760358744  0.874622708553
  0.379488134218  0.870378716192
#Sta/Elev= 14
    4640   56.42    4740   54.27    4750   53.68    4760   53.86    4810   52.33
    4870   48.01  4990.4   47.13  4992.4   43.13  5007.6   43.13  5009.6   47.13
  5123.6   48.45  5203.6   53.12  5253.6      54  5484.7   54.13
#Mann= 3 , 1 , 0
    4640     .13       0  4990.4    .044       0  5009.6     .13       0
Bank Sta=4990.4,5009.6
XS Rating Curve= 0 ,0
Exp/Cntr=0.3,0.1

Type RM Length L Ch R = 1 ,5407.9  ,880,880,880
BEGIN DESCRIPTION:
Fort Run 2.0
END DESCRIPTION:
XS GIS Cut Line= 3
   0.35498872377  0.914554818497  0.365598704672  0.898157575283
  0.381417221655  0.868449628755
#Sta/Elev= 14
  4610.6   58.14  4622.9   57.53  4670.6   55.16  4750.6   47.98  4930.6   47.33
  4989.4   46.38  4991.4   42.38  5008.5   42.38  5010.5   46.38  5110.4   46.82
  5200.4   52.63  5230.4    51.9  5360.4   53.66  5672.2   53.44
#Mann= 4 , 1 , 0
  4610.6      10       0  4622.9     .13       0  4989.4    .044       0
  5010.5     .13       0
Bank Sta=4989.4,5010.5
XS Rating Curve= 0 ,0
Exp/Cntr=0.3,0.1

Type RM Length L Ch R = 1 ,4527.9  ,252.1,252.1,252.1
BEGIN DESCRIPTION:
Fort Run 1.0
END DESCRIPTION:
XS GIS Cut Line= 3
  0.381803039142  0.930373335479  0.404952088385  0.903944837594
  0.430223133808  0.886004324431
#Sta/Elev= 17
  4295.3   53.51  4325.3    53.1  4365.3   52.87  4405.3   51.89  4655.3   50.09
  4695.3   48.09  4965.3   46.24  4985.3   46.66  4989.4   46.18  4991.4   42.18
  5008.6   42.18  5010.6   46.18  5016.6   46.84  5086.6   47.27  5166.6    51.5
  5206.6    51.7  5466.6   54.95
#Mann= 3 , 1 , 0
  4295.3     .13       0  4989.4    .044       0  5010.6     .13       0
Bank Sta=4989.4,5010.6
XS Rating Curve= 0 ,0
Exp/Cntr=0.3,0.1

Type RM Length L Ch R = 1 ,4275.8  ,601.7,601.7,601.7
BEGIN DESCRIPTION:
Fort Run 0.5
END DESCRIPTION:
XS GIS Cut Line= 3
  0.392685042116  0.942343415225  0.410115698521  0.914685974804
  0.436398378859  0.891810308584
#Sta/Elev= 18
    4349   57.55    4389   57.07    4439   52.63    4599   49.97    4869   46.87
    4909   47.16  4989.4   46.08  4991.4   42.08  5008.5   42.08  5010.5   46.08
  5011.5   47.07  5081.5   46.88  5101.5   46.44  5191.5   51.31  5241.5    51.7
  5251.5   52.13  5361.5   52.33    5697   53.44
#Mann= 3 , 1 , 0
    4349     .13       0  4989.4    .044       0  5010.5     .13       0
Bank Sta=4989.4,5010.5
XS Rating Curve= 0 ,0
Exp/Cntr=0.3,0.1

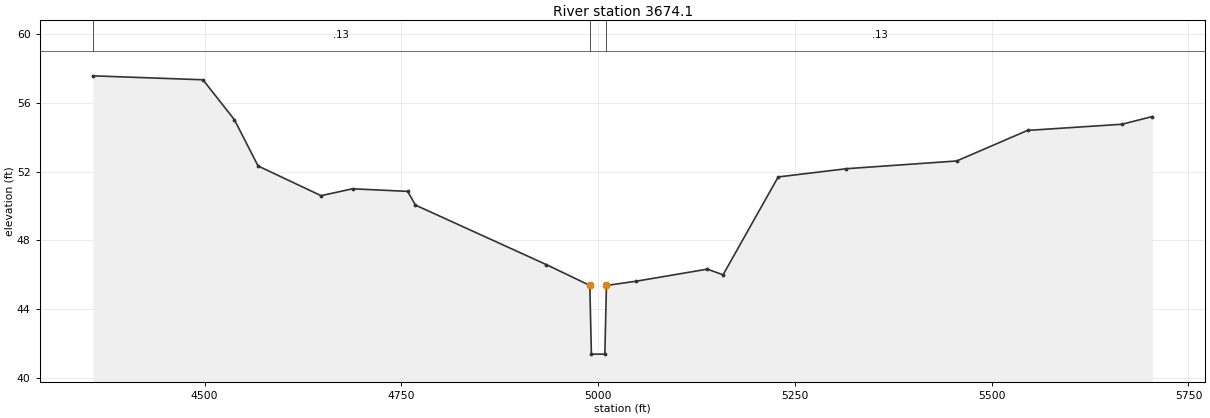
Type RM Length L Ch R = 1 ,3674.1  ,0,0,0
BEGIN DESCRIPTION:
Fort Run 0.1
END DESCRIPTION:
XS GIS Cut Line= 5
  0.399474790391            0.95  0.423818995869  0.934508232878
  0.425884564819   0.93200004201  0.436655031485  0.920344331508
  0.448458282626  0.904852564386
#Sta/Elev= 22
  4357.9   57.59  4497.9   57.36  4537.9   55.03  4567.9   52.34  4647.9   50.61
  4687.9   51.01  4757.9   50.86  4767.9   50.06  4933.9    46.6  4989.4   45.38
  4991.4   41.38  5008.5   41.38  5010.5   45.38  5048.7   45.63  5138.7   46.33
  5158.7      46  5228.7    51.7  5315.5   52.18  5455.5   52.63  5545.5   54.41
  5665.5   54.77  5704.2   55.22
#Mann= 3 , 1 , 0
  4357.9     .13       0  4989.4    .044       0  5010.5     .13       0
Bank Sta=4989.4,5010.5
XS Rating Curve= 0 ,0
Exp/Cntr=0.3,0.1

Chan Stop Cuts=-1
Use User Specified Reach Order=0