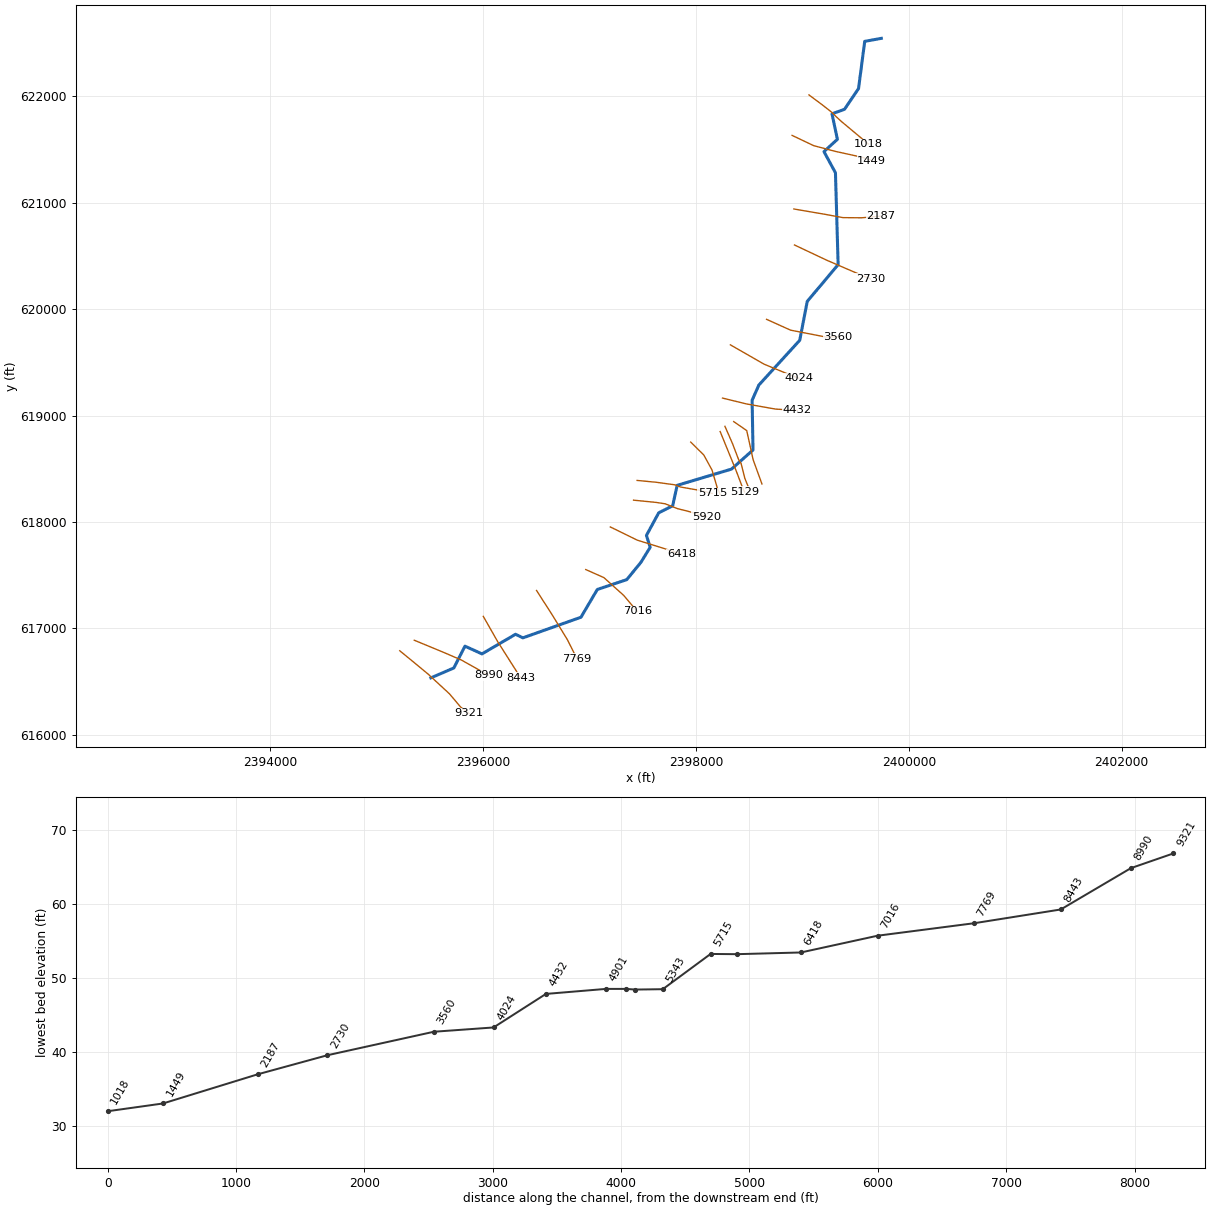
--- Poorhouse_Run.prj (project) ---

Proj Title=Poorhouse_Run
Current Plan=p03
Default Exp/Contr=0.3,0.1
English Units
Geom File=g01
Flow File=f01
Flow File=f02
Plan File=p03
Plan File=p04
Y Axis Title=Elevation
X Axis Title(PF)=Main Channel Distance
X Axis Title(XS)=Station
BEGIN DESCRIPTION:
END DESCRIPTION:
DSS Export Rating Curves= 0
DSS Export Rating Curve Sorted= 0
DSS Export Volume Flow Curves= 0
DXF OffsetX= 0
DXF OffsetY= 0
DXF ScaleX= 1
DXF ScaleY= 10

--- Poorhouse_Run.p03 (plan) ---

Plan Title=100 Year Single
Program Version=4.00
Short Identifier=100yr
Geom File=g01
Flow File=f01
Subcritical Flow
K Sum by GR= 0
Std Step Tol= 0.01
Critical Tol= 0.01
Num of Std Step Trials= 20
Max Error Tol= 0.3
Flow Tol Ratio= 0.001
Split Flow NTrial= 30
Split Flow Tol= 0.02
Split Flow Ratio= 0.02
Log Output Level= 0
Friction Slope Method= 1
Unsteady Friction Slope Method= 2
Unsteady Bridges Friction Slope Method= 1
Parabolic Critical Depth
Global Vel Dist= 0 , 0 , 0
Global Log Level= 0
CheckData=True
Encroach Param=-1 ,8,8, 2
Encroach River=Poorhouse Run
Encroach Reach=Poorhouse Run
Encroach Node=9321
       4      .7
Encroach Node=8990
       4      .7
Encroach Node=8443
       4      .7
Encroach Node=7769
       4      .7
Encroach Node=7016
       4      .7
Encroach Node=6418
       4      .7
Encroach Node=5920
       1     220     392
Encroach Node=5715
       4      .7
Encroach Node=5343
       1     327     456
Encroach Node=5129
       4      .7
Encroach Node=5056
       4      .7
Encroach Node=4901
       1  321.19  368.53
Encroach Node=4432
       4      .7
Encroach Node=4024
       4      .7
Encroach Node=3560
       4      .7
Encroach Node=2730
       4      .7
Encroach Node=2187
       1     372     448
Encroach Node=1449
       4      .7
Encroach Node=1018
       4      .7
Computation Interval=1HOUR
Output Interval=1HOUR
Run HTab= 0
Run UNet= 0
Run PostProcess= 0
Run WQNet= 0
UNET Theta= 1
UNET Theta Warmup= 1
UNET ZTol= 0.02
UNET ZSATol= 0.05
UNET MxIter= 20
UNET MaxInSteps= 0
UNET DtIC= 0
UNET DtMin= 0
UNET MaxCRTS= 20
UNET WFStab= 2
UNET SFStab= 1
UNET WFX= 1
UNET SFX= 1
UNET DSS MLevel= 4
UNET DZMax Abort= 100
UNET Convert EG Bridges=-1
UNET Use Existing IB Tables=-1
UNET Froude Reduction=False
UNET Froude Limit= 1
UNET Froude Power= 10
UNET Time Slicing=0,0, 5
Instantaneous Interval=1HOUR
Write IC File= 0
Echo Input=False
Echo Output=False
Write Detailed= 0
Detailed Automatic Start=False, 10
WQ ULTIMATE=-1
WQ Max Comp Step=1HOUR
WQ Output Interval=15MIN
WQ Output Selected Increments= 0
WQ Output face flow=0
WQ Output face velocity=0
WQ Output face area=0
WQ Output face dispersion=0
WQ Output cell volume=0
WQ Output cell surface area=0
WQ Output cell continuity=0
WQ Output face conc=0
WQ Output face dconc_dx=0
WQ Output face courant=0
WQ Output face peclet=0
WQ Output face adv mass=0
WQ Output face disp mass=0
WQ Output cell mass=0
WQ Output cell source sink temp=0
WQ Output cell source sink nsm=0
WQ Output MaxMinRange=-1
WQ Daily Max Min Mean=-1
WQ Daily Range=0
WQ Daily Time=0
WQ Create Restart=0
WQ Fixed Restart=0
WQ System Summary=False
Sorting and Armoring Iterations= 10
XS Update Threshold= 0.02
Hydraulics Update Threshold= 0.02
Energy Slope Method= 1
Volume Change Method= 0
XS Weighting Method= 0
Number of US Weighted Cross Sections= 1
Number of DS Weighted Cross Sections= 1
Upstream XS Weight=0.25
Main XS Weight=0.5
Downstream XS Weight=0.25
Number of DS XS's Weighted with US Boundary= 1
Upstream Boundary Weight= 1
Weight of XSs Associated with US Boundary= 0
Number of US XS's Weighted with DS Boundary= 1
Downstream Boundary Weight= 0.5
Weight of XSs Associated with DS Boundary= 0.5
Sediment Output Level= 4
Mass or Volume Output= 0
Output Increment Type= 1
Profile and TS Output Increment= 10
XS Output Flag= 0
XS Output Increment= 10
Disregard all LS=0
Disregard all Conn=0
Disregard all Breaches=0
Disregard all Pumps=0

--- Poorhouse_Run.p04 (plan) ---

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Plan Title=Multi_Profile
Program Version=3.13
Short Identifier=Multi_Pro
Geom File=g01
Flow File=f02

--- Poorhouse_Run.f01 (steady flow) ---

Flow Title=Poorhouse_Run
Program Version=4.00
Number of Profiles= 2
Profile Names=100-Year,AFW
River Rch & RM=Poorhouse Run,Poorhouse Run   ,9321
     530     530
River Rch & RM=Poorhouse Run,Poorhouse Run   ,5343
    1180    1180
Boundary for River Rch & Prof#=Poorhouse Run,Poorhouse Run   , 1
Up Type= 0
Dn Type= 3
Dn Slope=0.00244
Boundary for River Rch & Prof#=Poorhouse Run,Poorhouse Run   , 2
Up Type= 0
Dn Type= 3
Dn Slope=0.00244
DSS Import GetInterval= 0
DSS Import GetPeak= 0
DSS Import FillOption= 0

--- Poorhouse_Run.f02 (steady flow) ---

Flow Title=Multi_Profile
Program Version=4.00
Number of Profiles= 8
Profile Names=10-yr,25-yr,50-yr,500-yr,100-yr-10%,100-yr-20%,100-yr-35%,100-yr
River Rch & RM=Poorhouse Run,Poorhouse Run   ,9321
     210     320     410     870     930    1190    1450     530
River Rch & RM=Poorhouse Run,Poorhouse Run   ,5343
     550     840    1010    1710    1110    1420    1730    1180
Boundary for River Rch & Prof#=Poorhouse Run,Poorhouse Run   , 1
Up Type= 0
Dn Type= 3
Dn Slope=0.00244
Boundary for River Rch & Prof#=Poorhouse Run,Poorhouse Run   , 2
Up Type= 0
Dn Type= 3
Dn Slope=0.00244
DSS Import GetInterval= 0
DSS Import GetPeak= 0
DSS Import FillOption= 0

--- Poorhouse_Run.g01 (geometry) ---

Geom Title=Poorhouse_Run
Program Version=4.00

River Reach=Poorhouse Run   ,Poorhouse Run
Reach XY= 30
      2395509.25       616535.25      2395725.25     616628.3125
       2395829.5     616833.0625       2395989.5        616760.5
        2396305.     616944.8125        2396374.       616911.25
       2396919.5      617104.875        2397073.        617365.5
      2397350.25     617458.5625       2397482.5        617620.5
        2397570.         617762.      2397534.75     617873.6875
        2397650.      618085.875 2397781.2902715  618152.2480125
 2397823.4802138  618344.1117979 2398334.2798726  618496.7992081
 2398536.1888822  618676.6087242      2398527.75       619143.25
        2398591.     619286.5625 2398975.1651868  619707.2487437
      2399045.75     620072.6875        2399336.     620417.6875
      2399310.75      621281.125        2399203.         621480.
        2399329.      621595.625      2399278.25      621835.125
        2399396.       621877.75      2399527.75     622072.5625
      2399585.75     622515.9375        2399742.      622544.375

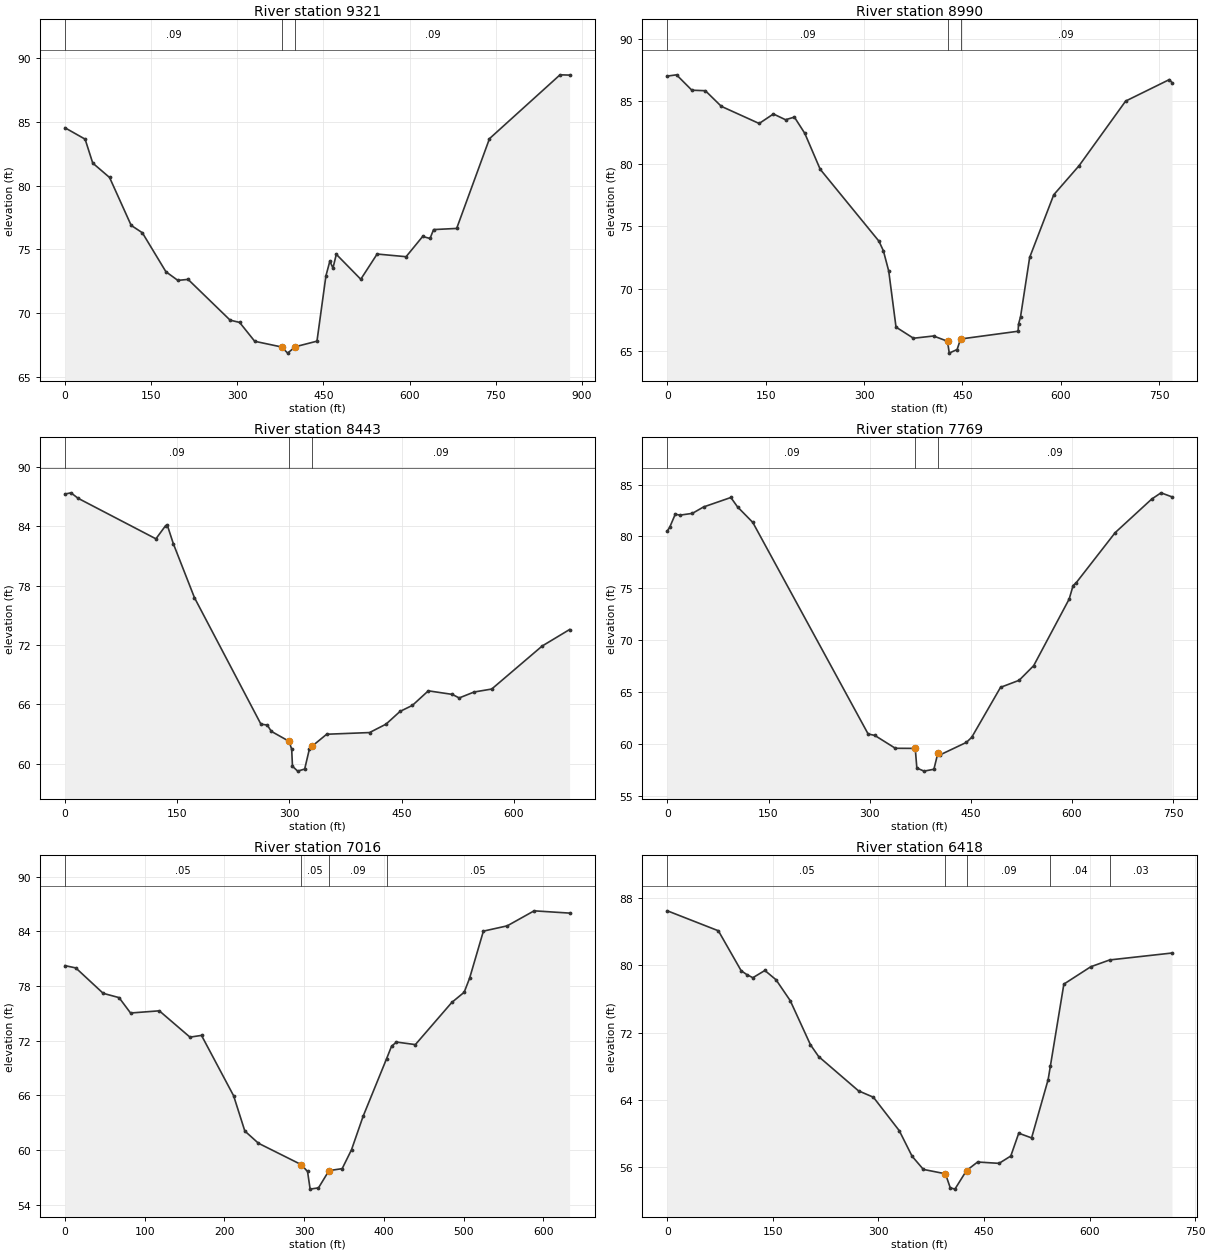
Type RM Length L Ch R = 1 ,9321    ,332.18,331.03,401.34
XS GIS Cut Line= 6
 2395216.6898558  616789.9790454 2395354.4197846  616677.2909218
  2395483.802445  616570.1676438 2395684.1368869  616385.1365273
 2395788.4777421  616261.3187126 2395866.3855806  616201.4966223
#Sta/Elev= 30
       0   84.53   34.97   83.64   48.29   81.76   77.58   80.63   115.2   76.87
  134.68   76.29  175.71   73.23  196.53   72.55   214.3   72.63  287.51   69.43
  304.09   69.25  330.36   67.77  377.42   67.32  387.69   66.84     401   67.34
  438.79   67.78  454.39   72.91  461.21   74.06  466.65   73.52  472.47    74.6
  515.07   72.64  543.55   74.62  593.98   74.41  622.86      76  635.65   75.84
   641.9   76.54  682.08   76.63  739.23   83.68  862.07   88.69  878.79   88.67
#Mann= 3 , 0 , 0
       0     .09       0  377.42     .05       0     401     .09       0
Bank Sta=377.42,401
XS Rating Curve= 0 ,0
Exp/Cntr=0.3,0.1

Type RM Length L Ch R = 1 ,8990    ,554.09,547.04,409.32
XS GIS Cut Line= 4
 2395353.2222428  616888.9362035 2395636.1128566  616771.6400953
 2395795.0642754    616703.23887 2396048.3741779  616561.1970777
#Sta/Elev= 30
       0      87   13.95    87.1   37.34   85.87   57.92   85.83   82.29   84.58
  139.99   83.21  161.72   83.97  180.19   83.51  193.74   83.72  209.61   82.42
  233.08   79.55  322.71    73.8  329.49   73.03  337.63   71.41  348.75   66.93
  375.37   66.04  405.99   66.22  427.29    65.8  429.95   64.85  441.93   65.14
  447.25   65.98  534.97    66.6  535.59   67.16   538.7   67.76  552.59    72.5
  589.34   77.51  628.06   79.84  698.98      85  765.68   86.72   769.7   86.48
#Mann= 3 ,-1 , 0
       0     .09       0  427.29     .05       0  447.25     .09       0
Bank Sta=427.29,447.25
XS Rating Curve= 0 ,0
Exp/Cntr=0.3,0.1

Type RM Length L Ch R = 1 ,8443    ,600.29,674.34,583.6
XS GIS Cut Line= 3
 2396001.8007232  617113.1787632 2396138.0712019  616873.4117186
 2396351.9641049   616537.047879
#Sta/Elev= 30
       0   87.27    7.96   87.39   17.42   86.84  121.49   82.74  134.43   84.07
  136.83   84.09  144.74   82.25  172.99   76.79  261.82      64  270.24   63.91
  275.79   63.27  299.33   62.27  302.94   61.47  303.99   59.74  310.98   59.25
   320.3   59.46  326.53   61.46  330.18   61.77  349.71   62.98  407.03   63.15
  429.01      64  447.79   65.29  464.31    65.9  485.55   67.37  517.52   67.01
   526.8   66.65  546.73   67.25  570.28   67.55  637.71    71.9   674.4   73.57
#Mann= 3 ,-1 , 0
       0     .09       0  299.33     .05       0  330.18     .09       0
Bank Sta=299.33,330.18
XS Rating Curve= 0 ,0
Exp/Cntr=0.3,0.1

Type RM Length L Ch R = 1 ,7769    ,637.29,752.1,688.37
XS GIS Cut Line= 4
 2396502.0341257  617356.3956933 2396645.2043753  617133.8780764
 2396791.8245105  616894.1110318 2396883.2464772  616712.9920412
#Sta/Elev= 30
       0   80.54    3.44   80.88   11.69   82.14   18.61   82.05   37.02   82.22
   53.68   82.84   94.15   83.75  104.01   82.85  126.68   81.35  297.77   60.97
  307.68   60.83  338.19   59.59  367.68   59.58  370.05   57.69   380.7   57.39
  395.34   57.57  401.44   59.18  404.96   58.97  443.59   60.16  451.47   60.65
  494.18   65.46  521.77   66.14  543.38   67.55  596.03   73.97  601.86   75.27
  606.22   75.52  664.33   80.37  718.46    83.6  732.27    84.2  748.53   83.81
#Mann= 3 , 0 , 0
       0     .09       0  367.68     .05       0  401.44     .09       0
Bank Sta=367.68,401.44
XS Rating Curve= 0 ,0
Exp/Cntr=0.3,0.1

Type RM Length L Ch R = 1 ,7016    ,496,597.91,573.62
XS GIS Cut Line= 5
 2396964.3187872  617553.0391687 2397135.0881211   617477.141687
   2397321.38194  617309.8222386 2397404.1791928  617211.5005009
 2397449.0277048  617161.4771606
#Sta/Elev= 30
       0   80.24   13.52   79.99   47.89    77.2   67.78   76.73    82.2   75.04
  118.27   75.28  156.75   72.39  171.21   72.58   211.5   65.95  225.56   62.08
   242.6   60.74  296.12    58.4  304.23   57.64  307.49    55.7  317.97   55.84
  331.13   57.73  347.68   57.95  359.41   60.03  373.95    63.7  403.29      70
  409.62   71.39  415.79   71.85  439.49   71.57   485.2    76.2  500.74   77.32
   507.6   78.88  524.83   84.03  554.73   84.61  588.48   86.26     633   86.01
#Mann= 4 ,-1 , 0
       0     .05       0  296.12     .05       0  331.13     .09       0
  403.29     .05       0
Bank Sta=296.12,331.13
XS Rating Curve= 0 ,0
Exp/Cntr=0.3,0.1

Type RM Length L Ch R = 1 ,6418    ,416.99,498.12,431.85
XS GIS Cut Line= 4
  2397195.461118  617953.2258907 2397449.0277048  617829.0300115
 2397704.3192343  617749.6826442 2397863.0139688  617696.2094184
#Sta/Elev= 30
       0   86.47   72.46    84.1  104.85   79.36  112.88    78.9  121.49   78.53
  138.57   79.39  154.46   78.28  174.58   75.81  203.33   70.57  214.97   69.17
  271.62    65.1   292.8   64.34  329.56   60.37  347.75   57.34  363.82   55.77
  395.16   55.25     402   53.59  408.65   53.43  425.16   55.64   440.9   56.65
  471.37   56.49  488.05   57.36  499.34   60.07  517.62   59.51  541.12   66.43
  544.32   68.04  563.48   77.77  601.71   79.83  628.65   80.64  717.15   81.46
#Mann= 5 ,-1 , 0
       0     .05       0  395.16     .05       0  425.16     .09       0
  544.32     .04       0  628.65     .03       0
Bank Sta=395.16,425.16
XS Rating Curve= 0 ,0
Exp/Cntr=0.5,0.3

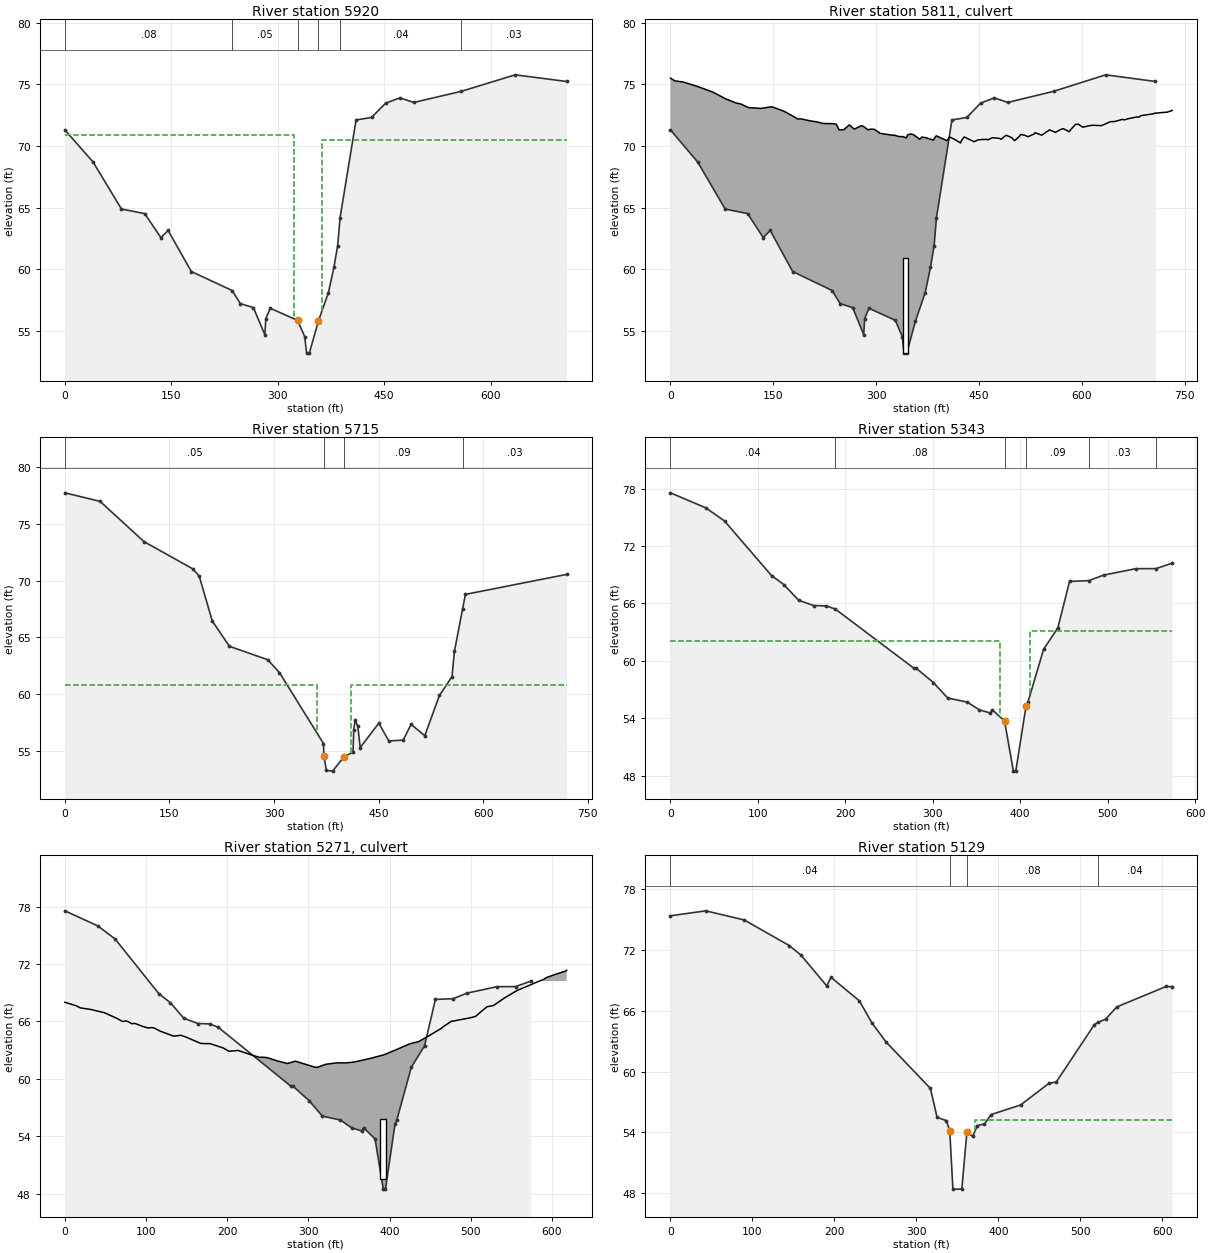
Type RM Length L Ch R = 1 ,5920    ,217.41,205.24,284.98
XS GIS Cut Line= 6
 2397413.7702963  618204.9344298 2397624.5177149   618183.859688
 2397710.6762183  618170.8429357 2397829.0666799  618124.3545345
 2397915.8673612  618103.1117904 2398099.9390972  618049.9730927
#Sta/Elev= 30
       0   71.31   39.65   68.71   79.75   64.89  112.51   64.52  135.29   62.57
  145.49   63.15  178.18   59.82  235.67   58.28  247.29   57.22  265.68   56.89
  281.78   54.69  283.15      56  289.36   56.84   327.9   55.86  337.92   54.54
  340.58   53.23  344.48    53.2   357.1   55.78  371.34    58.1  379.08   60.15
  384.37   61.91  387.83    64.2  410.35   72.12   432.1   72.32  452.06   73.48
  472.02   73.91  491.74   73.54  558.52   74.44  634.54   75.78  707.08   75.24
#Mann= 6 ,-1 , 0
       0     .08       0  235.67     .05       0   327.9     .05       0
   357.1     .09       0  387.83     .04       0  558.52     .03       0
#XS Ineff= 2 , 0
       0   322.9    70.9   362.1       0   70.48
Permanent Ineff=
       F       F
Bank Sta=327.9,357.1
XS Rating Curve= 0 ,0
Exp/Cntr=0.5,0.3

Type RM Length L Ch R = 2 ,5811    ,,,
Bridge Culvert--1,0,-1,-1, 0
Deck Dist Width WeirC Skew NumUp NumDn MinLoCord MaxHiCord MaxSubmerge Is_Ogee
88,35,2.6,0, 121, 121, , , 0.95, 0, 1,1,,
       0    6.45   18.49   24.63   39.29   42.69   60.24    60.9   65.28   78.53
   81.36   96.03  102.76  113.76   124.4  131.48  146.16  149.39  163.93   167.4
  168.17  185.78   190.7  204.27   213.5  222.96  236.71  241.85  245.87  252.76
   260.4  260.76  268.09  270.44  276.26  278.92  282.45   287.9  291.21  297.06
  304.45  304.97  324.47   325.3  333.29  338.74  343.92  345.82  351.46  355.28
  363.45  366.42  369.72  371.92  383.16  387.01  387.86  388.41  402.95  406.09
  407.73  414.94  422.88  424.12  428.17  442.36  442.72  443.42  448.73  460.84
  462.41  465.34  469.28  478.31   479.2  482.06  487.11  489.94  497.55  501.65
  508.77  510.76  515.98  521.36  530.51  531.54  534.42  541.22  552.27  552.41
  552.81  561.04  568.63  571.49  573.34  576.89  581.08   584.3   590.5  594.66
  601.11  609.46  615.81  621.53  628.39  637.02  641.75  647.49   658.5  662.27
  666.63  680.09  682.86  685.94  701.75  703.46  705.26  723.18  723.79  724.39
  731.45
   75.51   75.29    75.2   75.09   74.84   74.77   74.41    74.4   74.28   73.89
   73.81   73.49   73.41   73.12   73.09   73.05   73.18   73.16   72.86   72.77
   72.75    72.2    72.2   72.04   71.96   71.83   71.82   71.77   71.32   71.33
    71.7   71.72   71.37   71.44    71.6   71.66   71.55   71.32   71.37   71.36
   71.09   71.04   70.87    70.9   70.77   70.77   70.66   70.92   70.98   70.89
   70.55   70.73    70.7   70.69   70.48   70.81   70.83   70.81   70.44   70.68
   70.72   70.52   70.25   70.43   70.74   70.36   70.35   70.37   70.51   70.55
    70.5   70.57   70.68   70.63   70.63   70.55   70.79   70.87   70.68   70.43
   70.79   70.94   70.88   70.76   70.99   71.08   71.03   70.88    71.3   71.31
   71.31   71.11   71.34    71.4    71.4   71.29   71.16   71.38   71.76   71.77
   71.53   71.64   71.69   71.67   71.66   71.87   71.98   71.99   72.16   72.13
   72.21   72.36   72.35   72.47    72.6   72.61   72.66   72.75   72.74   72.76
   72.89
                                                                                
                                                                                
                                                                                
                                                                                
                                                                                
                                                                                
                                                                                
                                                                                
                                                                                
                                                                                
                                                                                
                                                                                
        
       0    6.45   18.49   24.63   39.29   42.69   60.24    60.9   65.28   78.53
   81.36   96.03  102.76  113.76   124.4  131.48  146.16  149.39  163.93   167.4
  168.17  185.78   190.7  204.27   213.5  222.96  236.71  241.85  245.87  252.76
   260.4  260.76  268.09  270.44  276.26  278.92  282.45   287.9  291.21  297.06
  304.45  304.97  324.47   325.3  333.29  338.74  343.92  345.82  351.46  355.28
  363.45  366.42  369.72  371.92  383.16  387.01  387.86  388.41  402.95  406.09
  407.73  414.94  422.88  424.12  428.17  442.36  442.72  443.42  448.73  460.84
  462.41  465.34  469.28  478.31   479.2  482.06  487.11  489.94  497.55  501.65
  508.77  510.76  515.98  521.36  530.51  531.54  534.42  541.22  552.27  552.41
  552.81  561.04  568.63  571.49  573.34  576.89  581.08   584.3   590.5  594.66
  601.11  609.46  615.81  621.53  628.39  637.02  641.75  647.49   658.5  662.27
  666.63  680.09  682.86  685.94  701.75  703.46  705.26  723.18  723.79  724.39
  731.45
   75.51   75.29    75.2   75.09   74.84   74.77   74.41    74.4   74.28   73.89
   73.81   73.49   73.41   73.12   73.09   73.05   73.18   73.16   72.86   72.77
   72.75    72.2    72.2   72.04   71.96   71.83   71.82   71.77   71.32   71.33
    71.7   71.72   71.37   71.44    71.6   71.66   71.55   71.32   71.37   71.36
   71.09   71.04   70.87    70.9   70.77   70.77   70.66   70.92   70.98   70.89
   70.55   70.73    70.7   70.69   70.48   70.81   70.83   70.81   70.44   70.68
   70.72   70.52   70.25   70.43   70.74   70.36   70.35   70.37   70.51   70.55
    70.5   70.57   70.68   70.63   70.63   70.55   70.79   70.87   70.68   70.43
   70.79   70.94   70.88   70.76   70.99   71.08   71.03   70.88    71.3   71.31
   71.31   71.11   71.34    71.4    71.4   71.29   71.16   71.38   71.76   71.77
   71.53   71.64   71.69   71.67   71.66   71.87   71.98   71.99   72.16   72.13
   72.21   72.36   72.35   72.47    72.6   72.61   72.66   72.75   72.74   72.76
   72.89
                                                                                
                                                                                
                                                                                
                                                                                
                                                                                
                                                                                
                                                                                
                                                                                
                                                                                
                                                                                
                                                                                
                                                                                
        
BR Coef=-1 , 1 , 0 ,1.25, 0 ,,,0.8,0,2,0,
WSPro=,,,, 1 ,,,, 0 ,,,, 0 ,,,,-1 ,-1 ,-1 , 0 , 0 , 0 , 0 , 0
Culvert=2,7.7,7.7,175,0.012,0.4,1,8,1,53.2,342.6,53.1,386.45,Culvert #1  , 0 ,20
Culvert Bottom n=0.012
BC Design=,, 0 ,, 0 ,,,,,,
BC Use User HTab Curves=0
BC User HTab FreeFlow(D)= 0

Type RM Length L Ch R = 1 ,5715    ,439.45,372.37,190.92
XS GIS Cut Line= 6
 2397447.0335754  618390.3872681 2397626.4276232  618373.1378403
 2397802.3717854  618348.9886416 2397855.7200299  618328.2836542
 2398036.7148716  618296.6715414 2398154.2601099  618267.9163316
#Sta/Elev= 30
       0   77.73    50.5   76.98  113.56   73.43  183.67   71.03  192.73   70.39
  211.44   66.45  235.99   64.22  290.92   63.04  307.85    61.9  370.98   55.66
  371.62   54.54  375.17   53.29  384.04   53.23  400.06   54.47  413.34   54.91
  414.33   56.88  416.33    57.7  420.12   57.21  423.66   55.31  450.33   57.45
  464.63   55.89  485.26   55.96  496.61   57.35  516.27   56.35  537.26   59.89
  555.36   61.55  558.76   63.77  570.58   67.53  574.58   68.79   719.8   70.55
#Mann= 4 ,-1 , 0
       0     .05       0  371.62     .05       0  400.06     .09       0
  570.58     .03       0
#XS Ineff= 2 , 0
       0  361.62    60.8  410.06       0    60.8
Permanent Ineff=
       F       F
Bank Sta=371.62,400.06
XS Rating Curve= 0 ,0
Exp/Cntr=0.5,0.3

Type RM Length L Ch R = 1 ,5343    ,220.69,214.15,219.08
XS GIS Cut Line= 5
 2397950.8440519  618750.4717596 2398073.3149884   618629.725766
 2398150.9374129  618488.2804591  2398202.685696  618312.3362969
 2398226.8348947  618260.5880138
#Sta/Elev= 30
       0   77.55   40.46   75.98   61.84   74.61  115.63    68.9  129.83   67.95
  146.59   66.32  163.71   65.77  178.16   65.73  188.56    65.4  278.64    59.2
  281.08   59.21  300.71   57.72  317.09    56.1  339.29   55.68  353.38   54.86
  365.75   54.54  368.01   54.87  382.06   53.71  392.16   48.48  394.94   48.46
  406.62   55.23  408.85   55.67  426.77    61.2  443.04   63.43  456.42   68.29
   478.4   68.37  495.43   68.95  532.17   69.62  555.35   69.63  573.83    70.2
#Mann= 6 ,-1 , 0
       0     .04       0  188.56     .08       0  382.06     .04       0
  406.62     .09       0   478.4     .03       0  555.35     .04       0
#XS Ineff= 2 , 0
       0  377.06   62.09  411.62       0   63.12
Permanent Ineff=
       F       F
Bank Sta=382.06,406.62
XS Rating Curve= 0 ,0
Exp/Cntr=0.5,0.3

Type RM Length L Ch R = 2 ,5271    ,,,
Bridge Culvert--1,0,-1,-1, 0
Deck Dist Width WeirC Skew NumUp NumDn MinLoCord MaxHiCord MaxSubmerge Is_Ogee
55,35,2.6,0, 82, 82, , , 0.95, 0, 1,1,,
       0    4.27   13.78    19.3   32.03   49.05   49.68   51.01   65.01   70.95
   75.56   78.62   82.06   86.66   95.69  102.55  106.05  109.45  117.84  134.01
  134.38  142.88  149.61  167.31  167.47  173.89  178.68   178.8  194.87  202.19
  210.79  213.33  231.41  239.81  244.99  249.37  261.43  274.09  283.85  283.99
  284.15  284.96  287.11  307.17  310.38  319.48  322.19  335.32  346.62  353.87
  359.82  374.65  393.05  396.71  410.46  424.62  429.34  435.42  448.52  463.81
   466.2  476.66   479.7  485.08  498.53  506.05  513.61  520.26  522.21  527.74
  543.26  544.04  544.41  545.07  557.55  571.27  582.77  589.39  593.64  606.33
  617.19  618.12
   67.99   67.88   67.63    67.4   67.24   66.89   66.86   66.81   66.27   65.98
   66.04   65.94   65.76   65.77   65.47    65.3   65.34   65.32   64.96   64.45
   64.45   64.54   64.34   63.69   63.69   63.67   63.67   63.67   63.22   62.87
   62.93   62.96   62.44   62.24   62.24    62.2   61.87   61.59   61.83   61.83
   61.83   61.81   61.75   61.23   61.18   61.45   61.52   61.66   61.66   61.72
   61.81   62.09    62.5   62.63   63.12   63.64   63.75   63.87   64.49   65.27
   65.45   66.03   66.04   66.14   66.35   66.52   67.08   67.53   67.56   67.64
   68.54   68.57   68.59   68.62   69.25   69.73   70.15   70.37   70.59   70.97
   71.26   71.34
                                                                                
                                                                                
                                                                                
                                                                                
                                                                                
                                                                                
                                                                                
                                                                                
                
       0    4.27   13.78    19.3   32.03   49.05   49.68   51.01   65.01   70.95
   75.56   78.62   82.06   86.66   95.69  102.55  106.05  109.45  117.84  134.01
  134.38  142.88  149.61  167.31  167.47  173.89  178.68   178.8  194.87  202.19
  210.79  213.33  231.41  239.81  244.99  249.37  261.43  274.09  283.85  283.99
  284.15  284.96  287.11  307.17  310.38  319.48  322.19  335.32  346.62  353.87
  359.82  374.65  393.05  396.71  410.46  424.62  429.34  435.42  448.52  463.81
   466.2  476.66   479.7  485.08  498.53  506.05  513.61  520.26  522.21  527.74
  543.26  544.04  544.41  545.07  557.55  571.27  582.77  589.39  593.64  606.33
  617.19  618.12
   67.99   67.88   67.63    67.4   67.24   66.89   66.86   66.81   66.27   65.98
   66.04   65.94   65.76   65.77   65.47    65.3   65.34   65.32   64.96   64.45
   64.45   64.54   64.34   63.69   63.69   63.67   63.67   63.67   63.22   62.87
   62.93   62.96   62.44   62.24   62.24    62.2   61.87   61.59   61.83   61.83
   61.83   61.81   61.75   61.23   61.18   61.45   61.52   61.66   61.66   61.72
   61.81   62.09    62.5   62.63   63.12   63.64   63.75   63.87   64.49   65.27
   65.45   66.03   66.04   66.14   66.35   66.52   67.08   67.53   67.56   67.64
   68.54   68.57   68.59   68.62   69.25   69.73   70.15   70.37   70.59   70.97
   71.26   71.34
                                                                                
                                                                                
                                                                                
                                                                                
                                                                                
                                                                                
                                                                                
                                                                                
                
BR Coef=-1 , 1 , 0 ,1.25, 0 ,,,0.8,0,2,0,
WSPro=,,,, 1 ,,,, 0 ,,,, 0 ,,,,-1 ,-1 ,-1 , 0 , 0 , 0 , 0 , 0
Culvert=2,6.3,7.8,105,0.012,0.4,1,8,1,49.5,391.82,49.4,350.91,Culvert #1  , 0 ,19
Culvert Bottom n=0.012
BC Design=,, 0 ,, 0 ,,,,,,
BC Use User HTab Curves=0
BC User HTab FreeFlow(D)= 0

Type RM Length L Ch R = 1 ,5129    ,63.42,72.67,62.98
XS GIS Cut Line= 4
 2398227.4852872  618849.6554994 2398379.3030666  618477.3640752
  2398443.125949   618308.319684 2398456.9254911  618282.4455425
#Sta/Elev= 30
       0   75.36   43.12   75.85      90   74.95  145.06   72.42  159.42   71.47
  190.63   68.45  195.88   69.29  230.42   66.98   245.6   64.82     263   62.92
   317.1   58.34  325.28   55.49  336.65   55.16  340.69   54.17  344.57   48.41
  355.43   48.41  361.64   54.07  368.63    53.6  374.47   54.68  383.02   54.83
  391.18   55.76  427.18   56.71  461.98   58.86  470.55   58.96  517.18   64.64
  521.67   64.85  531.11   65.18  544.28   66.37  604.57   68.39  612.07   68.37
#Mann= 4 ,-1 , 0
       0     .04       0  340.69     .04       0  361.64     .08       0
  521.67     .04       0
#XS Ineff= 2 , 0
       0  330.69    55.2  371.64       0    55.2
Permanent Ineff=
       F       F
Bank Sta=340.69,361.64
XS Rating Curve= 0 ,0
Exp/Cntr=0.5,0.3

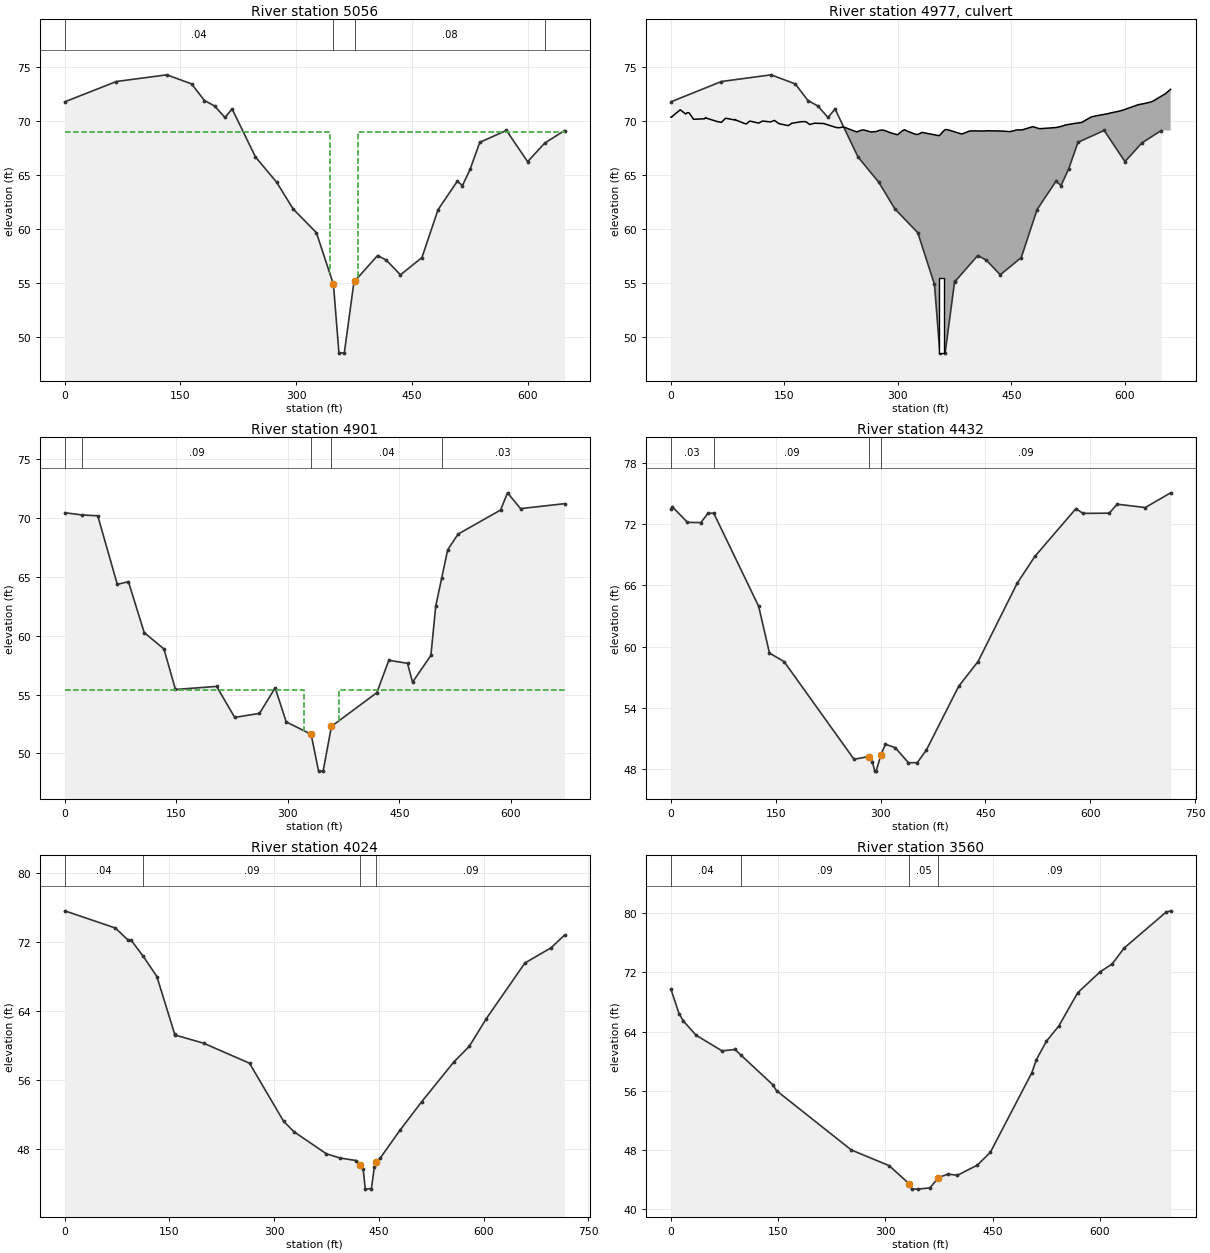
Type RM Length L Ch R = 1 ,5056    ,246.07,155.37,131.95
XS GIS Cut Line= 6
 2398272.3609166  618898.7469912 2398343.4096193  618736.6469664
  2398402.596882  618581.4803589 2398424.1922345   618549.487244
 2398459.3846609  618409.9172801 2398504.9748497  618296.3417221
#Sta/Elev= 30
       0   71.77   66.84   73.65  132.38   74.27  164.37   73.43  181.15   71.89
  194.18   71.39  207.68   70.32  216.96   71.11  247.22   66.67  274.85   64.31
  296.06   61.85   326.3   59.65  348.35   54.86  355.43   48.55  362.42    48.5
  374.85   55.05  375.76   55.15   405.6   57.54   416.9   57.11  435.27   55.75
  463.08   57.35     484   61.79  508.87   64.41  515.66   64.02   525.6   65.53
  538.06   68.02  572.63   69.12  600.13   66.23  622.45   67.96  647.98   69.11
#Mann= 4 ,-1 , 0
       0     .04       0  348.35     .04       0  375.76     .08       0
  622.45     .04       0
#XS Ineff= 2 , 0
       0  343.35   68.94  380.76       0   68.94
Permanent Ineff=
       F       F
Bank Sta=348.35,375.76
XS Rating Curve= 0 ,0
Exp/Cntr=0.5,0.3

Type RM Length L Ch R = 2 ,4977    ,,,
BEGIN DESCRIPTION:
HWY 258
END DESCRIPTION:
Bridge Culvert--1,0,-1,-1, 0
Deck Dist Width WeirC Skew NumUp NumDn MinLoCord MaxHiCord MaxSubmerge Is_Ogee
49,36,2.6,0, 99, 99, , , 0.95, 0, 1,1,,
       0     .63    2.94   12.32   19.66   21.22   23.95      30   44.31   45.99
   46.78   61.91   66.76   72.31   84.54   84.98   85.37   86.92   93.95   97.43
  100.06  103.53  104.78  116.02  121.04  131.79  136.89  142.66  154.87  156.02
  159.54  172.34   178.4  183.48  189.83  201.89  219.07  220.97  221.12  222.53
  226.96  227.43  230.57   245.7  251.35  254.58  264.34  271.31  272.33  276.05
  280.98  290.93  299.54  305.43  306.89  308.66  314.32  323.98  326.98  331.97
  354.68   361.1  363.15  366.11  383.83  386.21  394.75  398.62   414.7  417.42
  425.14  435.51  447.74  452.75  456.85  464.22  477.63  478.47  487.23  505.35
  510.18  518.06  521.44  533.82  542.87  554.53  555.63   561.8   578.4  580.33
   590.2  596.47  616.34  617.48   627.8  635.99   654.3  655.05  660.51
   70.35   70.34   70.49   71.03   70.64   70.75   70.76   70.15    70.2   70.32
   70.26   69.93   69.87   70.25   70.09   70.14   70.12   70.05   69.86   69.76
   69.73   69.96   69.98    69.8   69.99   69.91   70.05   69.75   69.57    69.6
   69.78   69.93   69.93   69.67   69.79   69.76   69.38   69.38   69.38   69.37
   69.43   69.45   69.38   68.98   69.14   69.17   68.98   69.02   69.04   69.14
   69.15   68.89   68.72   69.06   69.12   69.19      69   68.75   68.77   68.94
   68.63   69.12   69.21   69.18    68.8   68.83   69.07   69.08   69.07   69.09
   69.08   69.07   69.01   69.08   69.17   69.17   69.46   69.47   69.28   69.37
    69.4   69.54   69.63   69.77   69.86   70.33   70.37   70.47   70.68   70.73
   70.87   70.98   71.47    71.5   71.64   71.79   72.55   72.61   72.93
                                                                                
                                                                                
                                                                                
                                                                                
                                                                                
                                                                                
                                                                                
                                                                                
                                                                                
                                                                        
       0     .63    2.94   12.32   19.66   21.22   23.95      30   44.31   45.99
   46.78   61.91   66.76   72.31   84.54   84.98   85.37   86.92   93.95   97.43
  100.06  103.53  104.78  116.02  121.04  131.79  136.89  142.66  154.87  156.02
  159.54  172.34   178.4  183.48  189.83  201.89  219.07  220.97  221.12  222.53
  226.96  227.43  230.57   245.7  251.35  254.58  264.34  271.31  272.33  276.05
  280.98  290.93  299.54  305.43  306.89  308.66  314.32  323.98  326.98  331.97
  354.68   361.1  363.15  366.11  383.83  386.21  394.75  398.62   414.7  417.42
  425.14  435.51  447.74  452.75  456.85  464.22  477.63  478.47  487.23  505.35
  510.18  518.06  521.44  533.82  542.87  554.53  555.63   561.8   578.4  580.33
   590.2  596.47  616.34  617.48   627.8  635.99   654.3  655.05  660.51
   70.35   70.34   70.49   71.03   70.64   70.75   70.76   70.15    70.2   70.32
   70.26   69.93   69.87   70.25   70.09   70.14   70.12   70.05   69.86   69.76
   69.73   69.96   69.98    69.8   69.99   69.91   70.05   69.75   69.57    69.6
   69.78   69.93   69.93   69.67   69.79   69.76   69.38   69.38   69.38   69.37
   69.43   69.45   69.38   68.98   69.14   69.17   68.98   69.02   69.04   69.14
   69.15   68.89   68.72   69.06   69.12   69.19      69   68.75   68.77   68.94
   68.63   69.12   69.21   69.18    68.8   68.83   69.07   69.08   69.07   69.09
   69.08   69.07   69.01   69.08   69.17   69.17   69.46   69.47   69.28   69.37
    69.4   69.54   69.63   69.77   69.86   70.33   70.37   70.47   70.68   70.73
   70.87   70.98   71.47    71.5   71.64   71.79   72.55   72.61   72.93
                                                                                
                                                                                
                                                                                
                                                                                
                                                                                
                                                                                
                                                                                
                                                                                
                                                                                
                                                                        
BR Coef=-1 , 1 , 0 ,1.25, 0 ,,,0.8,0,2,0,
WSPro=,,,, 1 ,,,, 0 ,,,, 0 ,,,,-1 ,-1 ,-1 , 0 , 0 , 0 , 0 , 0
Culvert=2,7,7,110,0.012,0.4,1,8,1,48.5,358,48.4,342.73,Culvert #1  , 0 ,16
Culvert Bottom n=0.012
BC Design=,, 0 ,, 0 ,,,,,,
BC Use User HTab Curves=0
BC User HTab FreeFlow(D)= 0

Type RM Length L Ch R = 1 ,4901    ,247.91,468.39,532.49
XS GIS Cut Line= 4
 2398354.6226574  618943.3430389 2398477.0935939  618858.8208434
 2398537.4665907  618584.5549434 2398620.2638435  618356.8624982
#Sta/Elev= 30
       0   70.43   23.58   70.24   44.34   70.17   70.61   64.35   85.55   64.58
  106.78   60.26   133.3   58.87  148.81   55.43  204.15   55.69  228.46   53.06
  261.79    53.4  282.86   55.57  297.72   52.68  331.19   51.63  341.27    48.5
  347.34    48.5  358.53    52.3  419.58   55.16  435.68   57.91   460.8   57.65
  467.57   56.05  492.24   58.32  498.74    62.5  506.83   64.91  514.78   67.28
  528.84   68.62  585.94   70.66  595.24   72.12  612.82   70.78  671.92    71.2
#Mann= 5 ,-1 , 0
       0     .04       0   23.58     .09       0  331.19     .04       0
  358.53     .04       0  506.83     .03       0
#XS Ineff= 2 , 0
       0  321.19    55.4  368.53       0    55.4
Permanent Ineff=
       F       F
Bank Sta=331.19,358.53
XS Rating Curve= 0 ,0
Exp/Cntr=0.5,0.3

Type RM Length L Ch R = 1 ,4432    ,416.38,407.96,390.38
XS GIS Cut Line= 4
 2398249.4011486  619164.1357131 2398475.3686511  619108.9375446
 2398747.9096083  619060.6391471 2398953.1777976  619048.5645477
#Sta/Elev= 30
       0   73.41    2.01   73.68   23.75   72.15   42.88   72.13   52.96   73.03
   61.28   73.05  125.65   63.93     141   59.37  161.99   58.53  262.01   48.98
  283.29   49.25  288.27   48.74  291.64   47.82  293.65   47.84  300.66   49.44
  306.96   50.45  320.82   50.12  339.93   48.64  352.55   48.65  365.65    49.9
  411.75   56.12  439.47   58.54  495.47    66.2  520.72   68.82  579.59    73.5
  589.48   73.03  627.12   73.05  638.55   73.93  678.64    73.6  715.02   75.04
#Mann= 4 ,-1 , 0
       0     .03       0   61.28     .09       0  283.29     .05       0
  300.66     .09       0
Bank Sta=283.29,300.66
XS Rating Curve= 0 ,0
Exp/Cntr=0.3,0.1

Type RM Length L Ch R = 1 ,4024    ,432.38,464.65,460.33
XS GIS Cut Line= 4
 2398323.5736876  619664.3691155 2398639.2382139   619483.250125
  2398868.655602  619388.3782728 2398965.2523969  619350.4295319
#Sta/Elev= 30
       0   75.62   72.56   73.62   90.14   72.26   94.92   72.22  112.41   70.34
  131.97   67.98  157.21   61.35  158.35   61.18  198.84   60.24  264.68   57.91
  313.45   51.17  328.35   49.95  374.74   47.39  393.89    46.9  417.63    46.6
  423.62   46.11  427.43   45.64  430.55   43.28  439.25   43.34  443.51   45.85
  446.07   46.45  451.47   46.84  480.56   50.16  511.36   53.44  556.97   58.02
  579.58   59.88  603.86   63.09  659.23   69.56  696.59   71.32  715.98    72.8
#Mann= 4 ,-1 , 0
       0     .04       0  112.41     .09       0  423.62     .05       0
  446.07     .09       0
Bank Sta=423.62,446.07
XS Rating Curve= 0 ,0
Exp/Cntr=0.3,0.1

Type RM Length L Ch R = 1 ,3560    ,761.31,829.86,728.28
XS GIS Cut Line= 4
 2398663.3874127  619904.1361602 2398889.3549151  619802.3645369
 2399225.7187547  619736.8167118 2399334.3901491  619740.2665973
#Sta/Elev= 30
       0   69.74   11.37   66.44   17.31   65.44   35.17   63.51   71.53   61.39
   89.81   61.58   98.52   60.77  142.51   56.82  147.79   56.01  252.44   47.99
  305.31   45.88  333.12   43.45  336.95   42.72   345.3    42.7  362.49   42.87
  374.31   44.27  387.98   44.73  400.94   44.57  428.86   45.95  446.95   47.67
   505.1   58.45   511.4   60.22  525.47    62.7  542.89   64.77  569.19   69.25
  600.63   72.08  617.33   73.13  634.07   75.28  692.53   80.12  699.25   80.32
#Mann= 4 ,-1 , 0
       0     .04       0   98.52     .09       0  333.12     .05       0
  374.31     .09       0
Bank Sta=333.12,374.31
XS Rating Curve= 0 ,0
Exp/Cntr=0.3,0.1

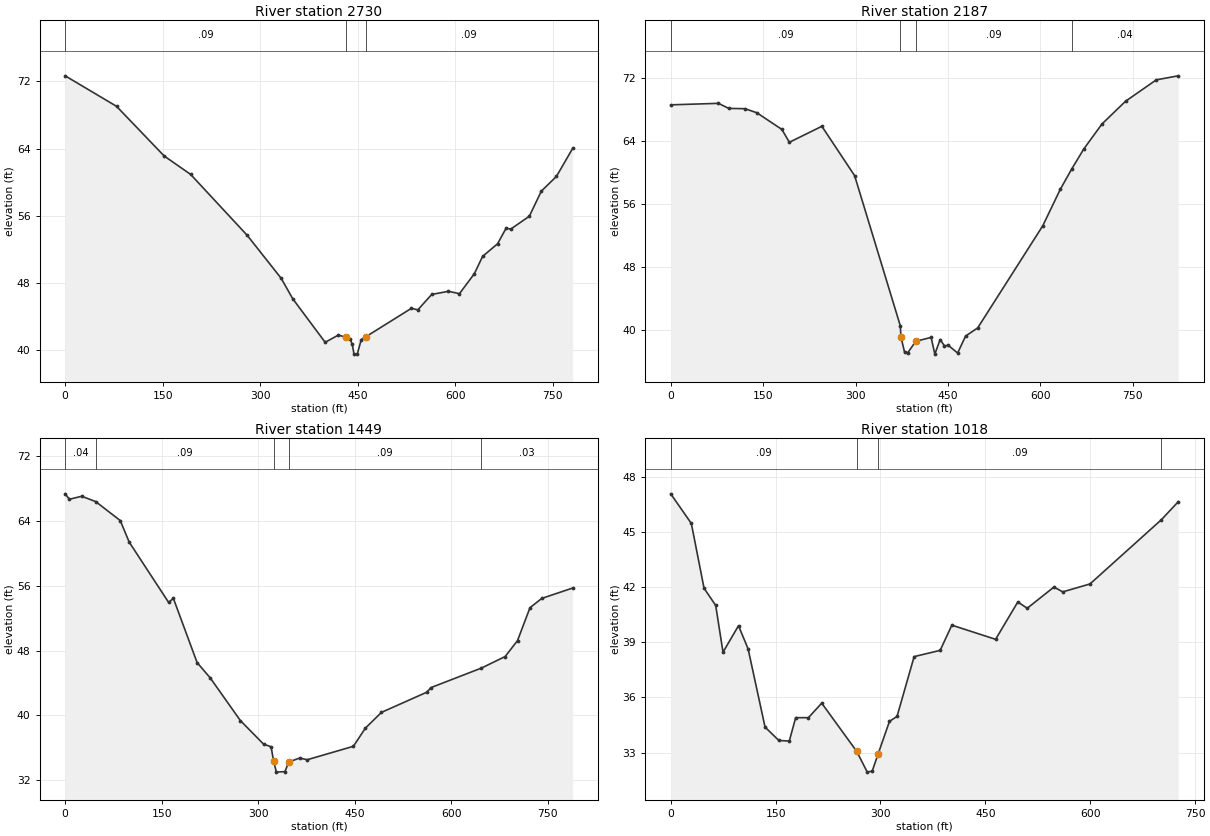
Type RM Length L Ch R = 1 ,2730    ,451.44,542.48,486.71
XS GIS Cut Line= 4
 2398925.5787133  620602.7379808 2399229.1686403  620459.5677311
 2399432.7118868    620371.59565  2399637.980076  620283.6235689
#Sta/Elev= 30
       0   72.66   79.03   69.03  152.25   63.12  193.03   60.92  280.01   53.67
  332.39   48.54  350.01   46.12  399.95   40.93  420.35   41.79  432.29   41.52
  437.96   41.38  441.65   40.69  444.35   39.52  449.36   39.53  455.57   41.26
  462.58   41.59  532.75   44.98  542.47   44.79  563.95   46.63  589.63      47
  606.55   46.72  629.49    49.1  642.19   51.16   665.2   52.66   678.3   54.51
  685.47   54.41  714.04   55.94  732.51   58.93  755.75   60.68  780.72   64.02
#Mann= 3 ,-1 , 0
       0     .09       0  432.29     .05       0  462.58     .09       0
Bank Sta=432.29,462.58
XS Rating Curve= 0 ,0
Exp/Cntr=0.3,0.1

Type RM Length L Ch R = 1 ,2187    ,685.37,738.29,632.64
XS GIS Cut Line= 5
  2398920.403885  620940.8267631 2399222.2688692  620889.0784801
 2399380.9636038  620859.7544531 2399553.4578805  620858.0295103
 2399736.3018138  620873.5539952
#Sta/Elev= 30
       0   68.56   77.46   68.75   94.11   68.11  120.64   68.07  139.87   67.55
  180.42   65.44  192.54   63.81  245.27   65.84  298.43   59.58  372.54   40.55
  373.72   39.08  379.54   37.18  384.86   37.14  397.74   38.57   422.6   39.06
  428.63   36.94  437.24   38.79  444.16      38  450.54   38.05  465.65   37.08
   478.5   39.23  498.13   40.26  603.73   53.21  632.29   57.85  650.69   60.41
  670.37   62.96  699.88   66.13  738.21   69.02  788.07   71.73  823.65   72.24
#Mann= 4 ,-1 , 0
       0     .09       0  372.54     .05       0  397.74     .09       0
  650.69     .04       0
Bank Sta=373.72,397.74
XS Rating Curve= 0 ,0
Exp/Cntr=0.3,0.1

Type RM Length L Ch R = 1 ,1449    ,432.46,430.94,259.55
XS GIS Cut Line= 5
 2398903.1544573  621632.5288127 2399106.6977038  621535.9320177
 2399308.5160076   621482.458792 2399560.3576515  621427.2606234
 2399651.7796182  621396.2116536
#Sta/Elev= 30
       0   67.35    6.58   66.68   25.72   67.05   47.46   66.39   85.58   64.05
   99.48   61.39  160.78   53.94  168.08   54.45  204.94   46.52   225.3   44.63
  272.27   39.35  308.19   36.45  319.95   36.12  323.73   34.38  328.16   32.99
  341.46   33.06  347.39   34.25  364.48   34.73  376.07   34.52  447.84   36.18
  466.27   38.41  491.45   40.37  561.91   42.86  568.14   43.42  646.77   45.84
  683.54   47.26  702.77   49.23  722.14   53.29  740.49   54.44  788.45   55.72
#Mann= 5 ,-1 , 0
       0     .04       0   47.46     .09       0  323.73     .05       0
  347.39     .09       0  646.77     .03       0
Bank Sta=323.73,347.39
XS Rating Curve= 0 ,0
Exp/Cntr=0.3,0.1

Type RM Length L Ch R = 1 ,1018    ,1050.19,1018,893.98
XS GIS Cut Line= 6
 2399061.9981713   622012.586649 2399181.6423518  621923.5491192
 2399270.6798816  621853.9885491 2399322.1547035  621803.9049387
 2399369.4558911  621760.7773852 2399621.2651549  621550.7044635
#Sta/Elev= 30
       0   47.07   29.47   45.46   47.65   41.94   64.34      41   74.77   38.46
   96.94    39.9  110.68   38.64  134.91   34.39  154.63   33.66   169.6   33.63
  178.71    34.9  196.93    34.9  215.97   35.69  265.97   33.07  281.15   31.94
  288.22      32  296.38    32.9  312.87    34.7   323.7   34.97  348.15   38.22
  385.39   38.56   402.1   39.93  464.67   39.16  496.43   41.19  509.91   40.85
  548.09      42  560.76   41.74  599.65   42.17  701.72   45.66  725.89   46.64
#Mann= 4 ,-1 , 0
       0     .09       0  265.97     .05       0  296.38     .09       0
  701.72     .03       0
Bank Sta=265.97,296.38
XS Rating Curve= 0 ,0
Exp/Cntr=0.3,0.1

Chan Stop Cuts=-1
Use User Specified Reach Order=0
User Specified Reach Order=Poorhouse Run   ,Poorhouse Run