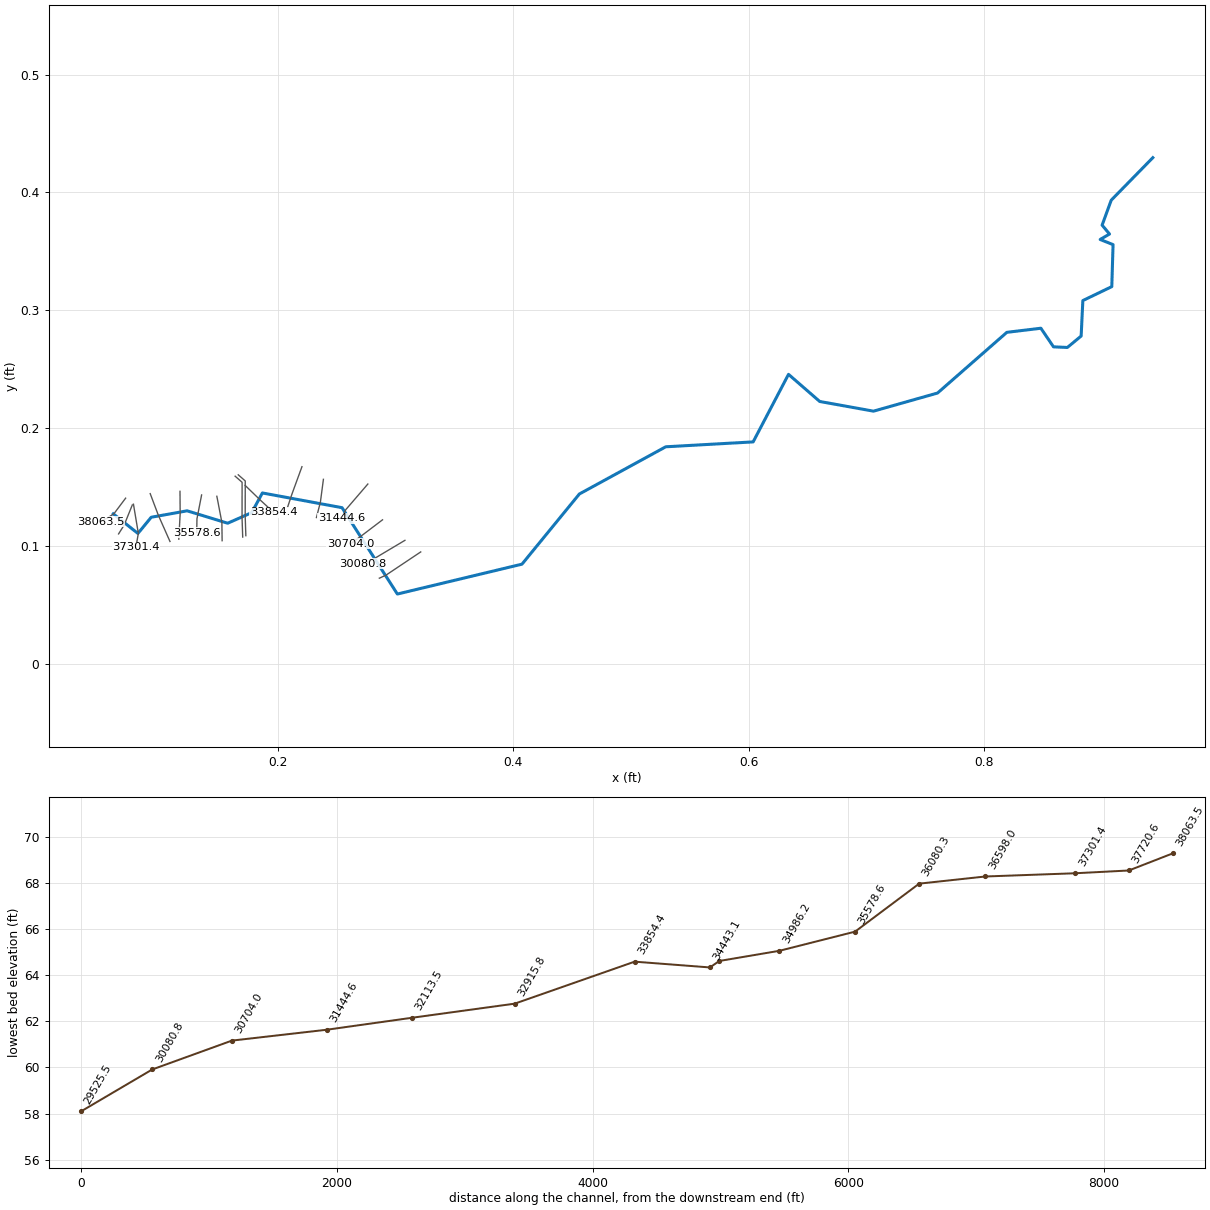
--- Rainbow_Creek_FINAL.prj (project) ---

Proj Title=Rainbow Creek
Current Plan=p01
Default Exp/Contr=0.3,0.1
English Units
Geom File=g01
Flow File=f02
Flow File=f01
Plan File=p02
Plan File=p01
Y Axis Title=Elevation
X Axis Title(PF)=Main Channel Distance
X Axis Title(XS)=Station
BEGIN DESCRIPTION:
####(Watershed Name)####
RAINBOW CREEK
HCFCD Unit X###-##-##
(Flood Hazard, Floodway) Model
10, 2, 1, 0.2% Event
Filename:  N:\NC_flood\60138\Approximates\Eng\Toisnot_Nahunta\ENG\Rainbow_Creek\Temp_Rainbow\Rainbow Creek.prj
Prepared by:  ________     Date: ________
Reviewed by:  ________     Date: ________
STATUS (Draft RAS, SVSQ, FINAL)
END DESCRIPTION:
DSS Export Rating Curves= 0
DSS Export Rating Curve Sorted= 0
DSS Export Volume Flow Curves= 0
DXF OffsetX= 0
DXF OffsetY= 0
DXF ScaleX= 1
DXF ScaleY= 10

--- Rainbow_Creek_FINAL.p01 (plan) ---

Plan Title=100 Year Single
Program Version=4.00
Short Identifier=Plan01
Geom File=g01
Flow File=f01
Subcritical Flow
K Sum by GR= 0
Std Step Tol= 0.01
Critical Tol= 0.01
Num of Std Step Trials= 20
Max Error Tol= 0.3
Flow Tol Ratio= 0.001
Split Flow NTrial= 30
Split Flow Tol= 0.02
Split Flow Ratio= 0.02
Log Output Level= 0
Friction Slope Method= 1
Unsteady Friction Slope Method= 2
Unsteady Bridges Friction Slope Method= 1
Parabolic Critical Depth
Global Vel Dist= 0 , 0 , 0
Global Log Level= 0
CheckData=True
Encroach Param=-1 ,10,10, 2
Encroach River=Rainbow Creek
Encroach Reach=Reach - 1
Encroach Node=38063.5
       4      .7
Encroach Node=37720.6
       4      .7
Encroach Node=37301.4
       1    4955    5150
Encroach Node=36598.0
       1    4935    5300
Encroach Node=36080.3
       1    4983    5325
Encroach Node=35578.6
       1    4855    5100
Encroach Node=34986.2
       1    4960    5140
Encroach Node=34517.1
       4      .7
Encroach Node=34443.1
       4      .7
Encroach Node=33854.4
       1    4905    5095
Encroach Node=32915.8
       1    4725    5125
Encroach Node=32113.5
       1    4800    5175
Encroach Node=31444.6
       1    4750    5030
Encroach Node=30704.0
       1    4700    5040
Encroach Node=30080.8
       1    4600    5020
Encroach Node=29525.5
       14802.1355022.135
Computation Interval=1HOUR
Output Interval=1HOUR
Run HTab= 0
Run UNet= 0
Run PostProcess= 0
Run WQNet= 0
UNET Theta= 1
UNET Theta Warmup= 1
UNET ZTol= 0.02
UNET ZSATol= 0.1
UNET MxIter= 20
UNET MaxInSteps= 20
UNET DtIC= 0
UNET DtMin= 0
UNET MaxCRTS= 20
UNET WFStab= 2
UNET SFStab= 1
UNET WFX= 1
UNET SFX= 1
UNET DSS MLevel= 4
UNET DZMax Abort= 100
UNET Convert EG Bridges=-1
UNET Use Existing IB Tables=-1
UNET Froude Reduction=False
UNET Froude Limit= 1
UNET Froude Power= 10
UNET Time Slicing=0,0, 5
Instantaneous Interval=1HOUR
Write IC File= 0
Echo Input=False
Echo Output=False
Write Detailed= 0
Detailed Automatic Start=False, 10
WQ ULTIMATE=-1
WQ Max Comp Step=1HOUR
WQ Output Interval=15MIN
WQ Output Selected Increments= 0
WQ Output face flow=0
WQ Output face velocity=0
WQ Output face area=0
WQ Output face dispersion=0
WQ Output cell volume=0
WQ Output cell surface area=0
WQ Output cell continuity=0
WQ Output face conc=0
WQ Output face dconc_dx=0
WQ Output face courant=0
WQ Output face peclet=0
WQ Output face adv mass=0
WQ Output face disp mass=0
WQ Output cell mass=0
WQ Output cell source sink temp=0
WQ Output cell source sink nsm=0
WQ Output MaxMinRange=-1
WQ Daily Max Min Mean=-1
WQ Daily Range=0
WQ Daily Time=0
WQ Create Restart=0
WQ Fixed Restart=0
WQ System Summary=False
Sorting and Armoring Iterations= 10
XS Update Threshold= 0.02
Hydraulics Update Threshold= 0.02
Energy Slope Method= 1
Volume Change Method= 0
XS Weighting Method= 0
Number of US Weighted Cross Sections= 1
Number of DS Weighted Cross Sections= 1
Upstream XS Weight=0.25
Main XS Weight=0.5
Downstream XS Weight=0.25
Number of DS XS's Weighted with US Boundary= 1
Upstream Boundary Weight= 1
Weight of XSs Associated with US Boundary= 0
Number of US XS's Weighted with DS Boundary= 1
Downstream Boundary Weight= 0.5
Weight of XSs Associated with DS Boundary= 0.5
Sediment Output Level= 4
Mass or Volume Output= 0
Output Increment Type= 1
Profile and TS Output Increment= 10
XS Output Flag= 0
XS Output Increment= 10
Disregard all LS=0
Disregard all Conn=0
Disregard all Breaches=0
Disregard all Pumps=0

--- Rainbow_Creek_FINAL.p02 (plan) ---

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Plan Title=Multi_Profile
Short Identifier=Multi_Pro
Geom File=g01
Flow File=f02

--- Rainbow_Creek_FINAL.f01 (steady flow) ---

Flow Title= 100 Year Single
Program Version=4.00
Number of Profiles= 2
Profile Names=100-Year,AFW
River Rch & RM=Rainbow Creek,Reach - 1       ,38063.5
     929     929
River Rch & RM=Rainbow Creek,Reach - 1       ,36080.3
    1153    1153
River Rch & RM=Rainbow Creek,Reach - 1       ,34517.1
    1202    1202
River Rch & RM=Rainbow Creek,Reach - 1       ,31444.6
    1300    1300
Boundary for River Rch & Prof#=Rainbow Creek,Reach - 1       , 1
Up Type= 0
Dn Type= 1
Dn Known WS=65.99
Boundary for River Rch & Prof#=Rainbow Creek,Reach - 1       , 2
Up Type= 0
Dn Type= 1
Dn Known WS=66.98
DSS Import GetInterval= 0
DSS Import GetPeak= 0
DSS Import FillOption= 0

--- Rainbow_Creek_FINAL.f02 (steady flow) ---

Flow Title=Multi_Profile
Program Version=4.00
Number of Profiles= 7
Profile Names=10-yr,25-yr,50-yr,500-yr,100-yr-10%,100-yr-20%,100-yr-35%
River Rch & RM=Rainbow Creek,Reach - 1       ,38063.5
     396     577     740    1486    1607    2059    2516
River Rch & RM=Rainbow Creek,Reach - 1       ,36080.3
     501     723     923    1824    1979    2536    3098
River Rch & RM=Rainbow Creek,Reach - 1       ,34517.1
     524     755     964    1899    2060    2641    3227
River Rch & RM=Rainbow Creek,Reach - 1       ,31444.6
     569     817    1040    2039    2215    2839    3469
Boundary for River Rch & Prof#=Rainbow Creek,Reach - 1       , 1
Up Type= 0
Dn Type= 1
Dn Known WS=65
Boundary for River Rch & Prof#=Rainbow Creek,Reach - 1       , 2
Up Type= 0
Dn Type= 1
Dn Known WS=65.37
Boundary for River Rch & Prof#=Rainbow Creek,Reach - 1       , 3
Up Type= 0
Dn Type= 1
Dn Known WS=65.66
Boundary for River Rch & Prof#=Rainbow Creek,Reach - 1       , 4
Up Type= 0
Dn Type= 1
Dn Known WS=66.67
Boundary for River Rch & Prof#=Rainbow Creek,Reach - 1       , 5
Up Type= 0
Dn Type= 1
Dn Known WS=66.82
Boundary for River Rch & Prof#=Rainbow Creek,Reach - 1       , 6
Up Type= 0
Dn Type= 1
Dn Known WS=67.29
Boundary for River Rch & Prof#=Rainbow Creek,Reach - 1       , 7
Up Type= 0
Dn Type= 1
Dn Known WS=67.72
DSS Import GetInterval= 0
DSS Import GetPeak= 0
DSS Import FillOption= 0

--- Rainbow_Creek_FINAL.g01 (geometry) ---

Geom Title=Geom 01 by CodeH2 for Windows
Program Version=4.00

River Reach=Rainbow Creek   ,Reach - 1
Reach XY= 30
       0.0603231       0.1271661       0.0812395       0.1105308
       0.0925343        0.124263       0.1230298       0.1297319
       0.1574491       0.1192102       0.1778688       0.1281864
       0.1869339       0.1448907       0.2545734       0.1323918
       0.3015597       0.0591013       0.4073787       0.0844598
        0.456087       0.1440071       0.5294506       0.1840848
       0.6036507       0.1882327       0.6336924       0.2455724
       0.6601874       0.2225561       0.7058515       0.2143266
       0.7602473       0.2297151       0.8190919       0.2812339
       0.8479959        0.284713       0.8587012        0.268923
       0.8704766       0.2683878       0.8821855       0.2780891
        0.883624       0.3081973       0.9082043       0.3200367
       0.9092829       0.3557014       0.8983102       0.3600503
       0.9062722        0.364667       0.8999827       0.3722276
       0.9077442       0.3934373       0.9430519       0.4294906

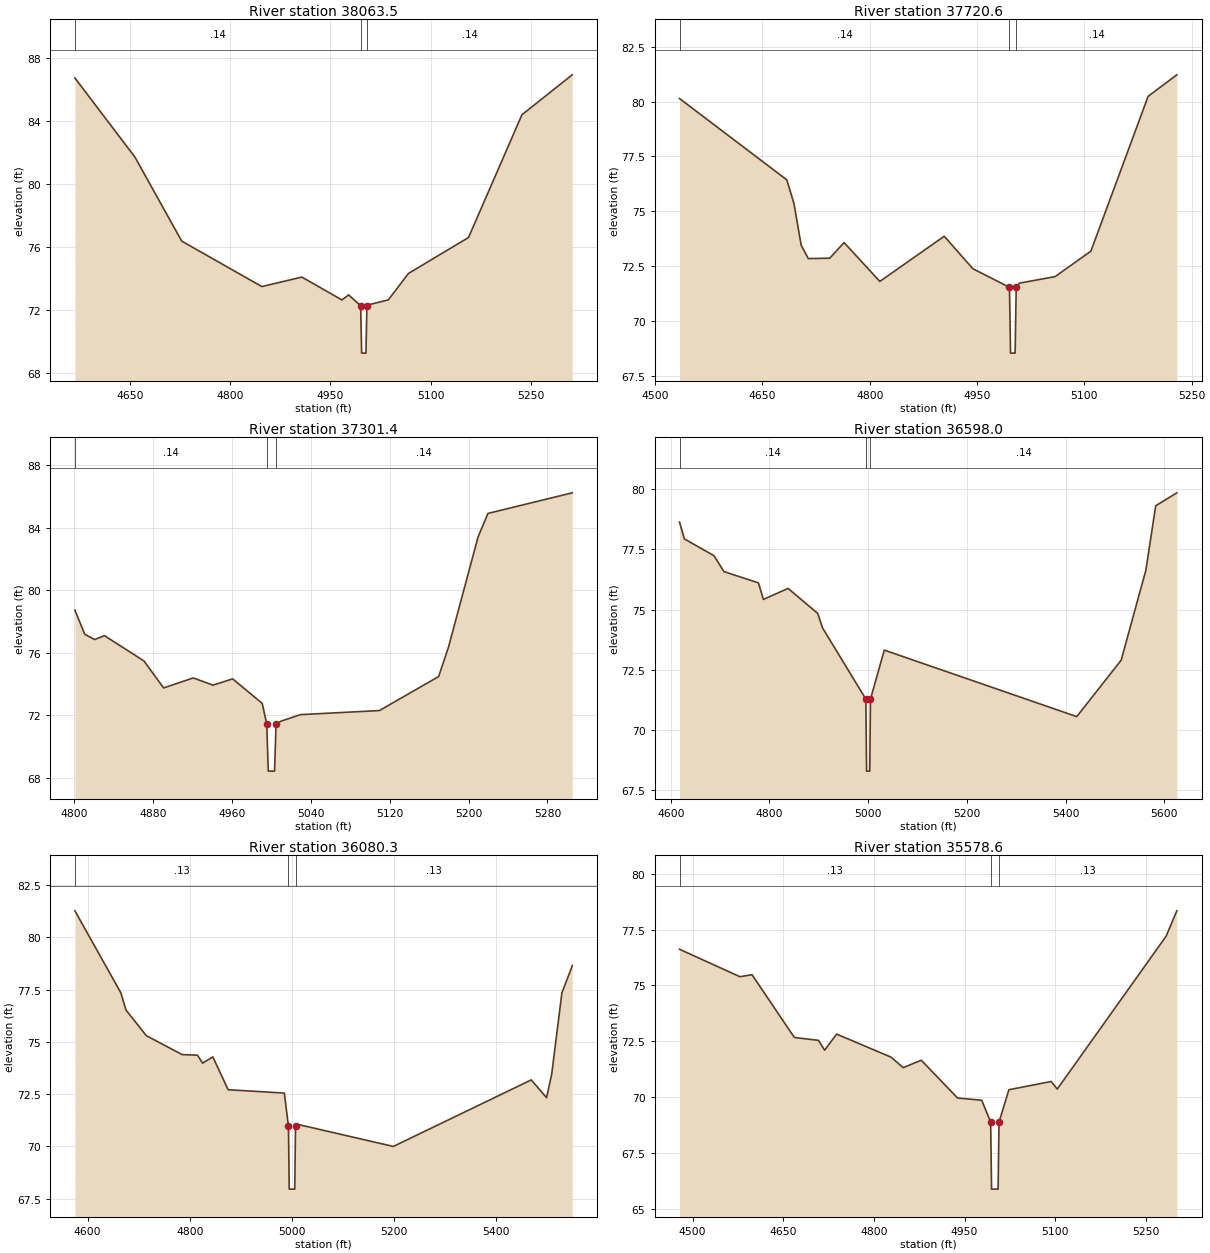
Type RM Length L Ch R = 1 ,38063.5 ,342.9,342.9,342.9
BEGIN DESCRIPTION:
Rainbow Creek 49.0
END DESCRIPTION:
XS GIS Cut Line= 3
          0.0708       0.1404785       0.0606573       0.1269698
            0.05        0.120633
#Sta/Elev= 17
  4567.3   86.71  4657.3   81.69  4727.3   76.37  4847.3   73.49  4907.3   74.09
  4967.3   72.64  4977.3   72.96  4995.3   72.27  4996.8   69.27  5003.2   69.27
  5004.7   72.27  5006.9   72.33  5036.9   72.65  5066.9   74.32  5156.9    76.6
  5236.9   84.38  5312.2   86.91
#Mann= 3 , 1 , 0
  4567.3     .14       0  4995.3    .048       0  5004.7     .14       0
Bank Sta=4995.3,5004.7
XS Rating Curve= 0 ,0
Exp/Cntr=0.3,0.1

Type RM Length L Ch R = 1 ,37720.6 ,419.2,419.2,419.2
BEGIN DESCRIPTION:
Rainbow Creek 48.0
END DESCRIPTION:
XS GIS Cut Line= 3
       0.0764882         0.13473       0.0696139        0.117784
       0.0648179       0.1101103
#Sta/Elev= 19
  4534.1   80.14  4684.1   76.43  4694.1   75.35  4704.1   73.46  4714.1   72.84
  4744.1   72.86  4764.1   73.57  4814.1    71.8  4904.1   73.86  4944.1   72.38
  4995.3   71.53  4996.8   68.53  5003.2   68.53  5004.7   71.53  5009.1   71.72
  5059.1   72.02  5109.1   73.18  5189.1   80.24  5229.2   81.22
#Mann= 3 , 1 , 0
  4534.1     .14       0  4995.3    .048       0  5004.7     .14       0
Bank Sta=4995.3,5004.7
XS Rating Curve= 0 ,0
Exp/Cntr=0.3,0.1

Type RM Length L Ch R = 1 ,37301.4 ,703.4,703.4,703.4
BEGIN DESCRIPTION:
Rainbow Creek 47.0
END DESCRIPTION:
XS GIS Cut Line= 3
       0.0774474       0.1353694        0.081604       0.1105899
       0.0795257       0.0987597
#Sta/Elev= 22
  4800.7   78.72  4810.7   77.18  4820.7   76.84  4830.7   77.09  4870.7   75.47
  4890.7   73.74  4920.7   74.38  4940.7   73.92  4960.7   74.32  4990.7   72.75
  4995.3   71.41  4996.8   68.41  5003.2   68.41  5004.7   71.41  5009.6   71.61
  5029.6   72.03  5109.6   72.29  5169.6   74.47  5179.6   76.35  5209.6   83.41
  5219.6   84.92  5305.1   86.24
#Mann= 3 , 1 , 0
  4800.7     .14       0  4995.3    .048       0  5004.7     .14       0
Bank Sta=4995.3,5004.7
XS Rating Curve= 0 ,0
Exp/Cntr=0.3,0.1

Type RM Length L Ch R = 1 ,36598.0 ,517.7,517.7,517.7
BEGIN DESCRIPTION:
Rainbow Creek 46.0
END DESCRIPTION:
XS GIS Cut Line= 3
       0.0916757       0.1443221       0.0985341       0.1261057
       0.1084618       0.1037156
#Sta/Elev= 19
  4617.7   78.64  4627.7   77.94  4687.7   77.24  4707.7   76.58  4777.7   76.11
  4787.7   75.42  4837.7   75.88  4897.7   74.84  4907.7   74.23  4995.3   71.27
  4996.8   68.27  5003.2   68.27  5004.7   71.27  5032.7   73.31  5422.7   70.54
  5512.7   72.89  5562.7   76.63  5582.7   79.32  5625.5   79.86
#Mann= 3 , 1 , 0
  4617.7     .14       0  4995.3    .048       0  5004.7     .14       0
Bank Sta=4995.3,5004.7
XS Rating Curve= 0 ,0
Exp/Cntr=0.3,0.1

Type RM Length L Ch R = 1 ,36080.3 ,501.7,501.7,501.7
BEGIN DESCRIPTION:
Rainbow Creek 45.0
END DESCRIPTION:
XS GIS Cut Line= 3
       0.1169684       0.1462682       0.1171124       0.1272578
       0.1159603       0.1056551
#Sta/Elev= 22
    4575   81.26    4665   77.34    4675   76.52    4715   75.29    4785   74.39
    4815   74.36    4825   73.98    4845   74.28    4875   72.71    4985   72.55
  4993.1   70.96  4994.6   67.96  5005.4   67.96  5006.9   70.96  5008.4   71.07
  5198.4      70  5468.4   73.18  5498.4   72.33  5508.4   73.45  5528.4   77.34
  5548.4   78.61  5548.6   78.65
#Mann= 3 , 1 , 0
    4575     .13       0  4993.1    .048       0  5006.9     .13       0
Bank Sta=4993.1,5006.9
XS Rating Curve= 0 ,0
Exp/Cntr=0.3,0.1

Type RM Length L Ch R = 1 ,35578.6 ,592.4,592.4,592.4
BEGIN DESCRIPTION:
Rainbow Creek 44.0
END DESCRIPTION:
XS GIS Cut Line= 3
       0.1353196        0.143203       0.1313702       0.1229373
       0.1311631       0.1112294
#Sta/Elev= 21
  4478.3   76.62  4578.3   75.39  4598.3   75.48  4668.3   72.67  4708.3   72.54
  4718.3    72.1  4738.3   72.82  4828.3   71.79  4848.3   71.32  4878.3   71.65
  4938.3   69.96  4978.3   69.86  4993.1   68.88  4994.6   65.88  5005.4   65.88
  5006.9   68.88  5023.3   70.33  5093.3    70.7  5103.3   70.36  5283.3    77.2
  5301.1   78.34
#Mann= 3 , 1 , 0
  4478.3     .13       0  4993.1    .048       0  5006.9     .13       0
Bank Sta=4993.1,5006.9
XS Rating Curve= 0 ,0
Exp/Cntr=0.3,0.1

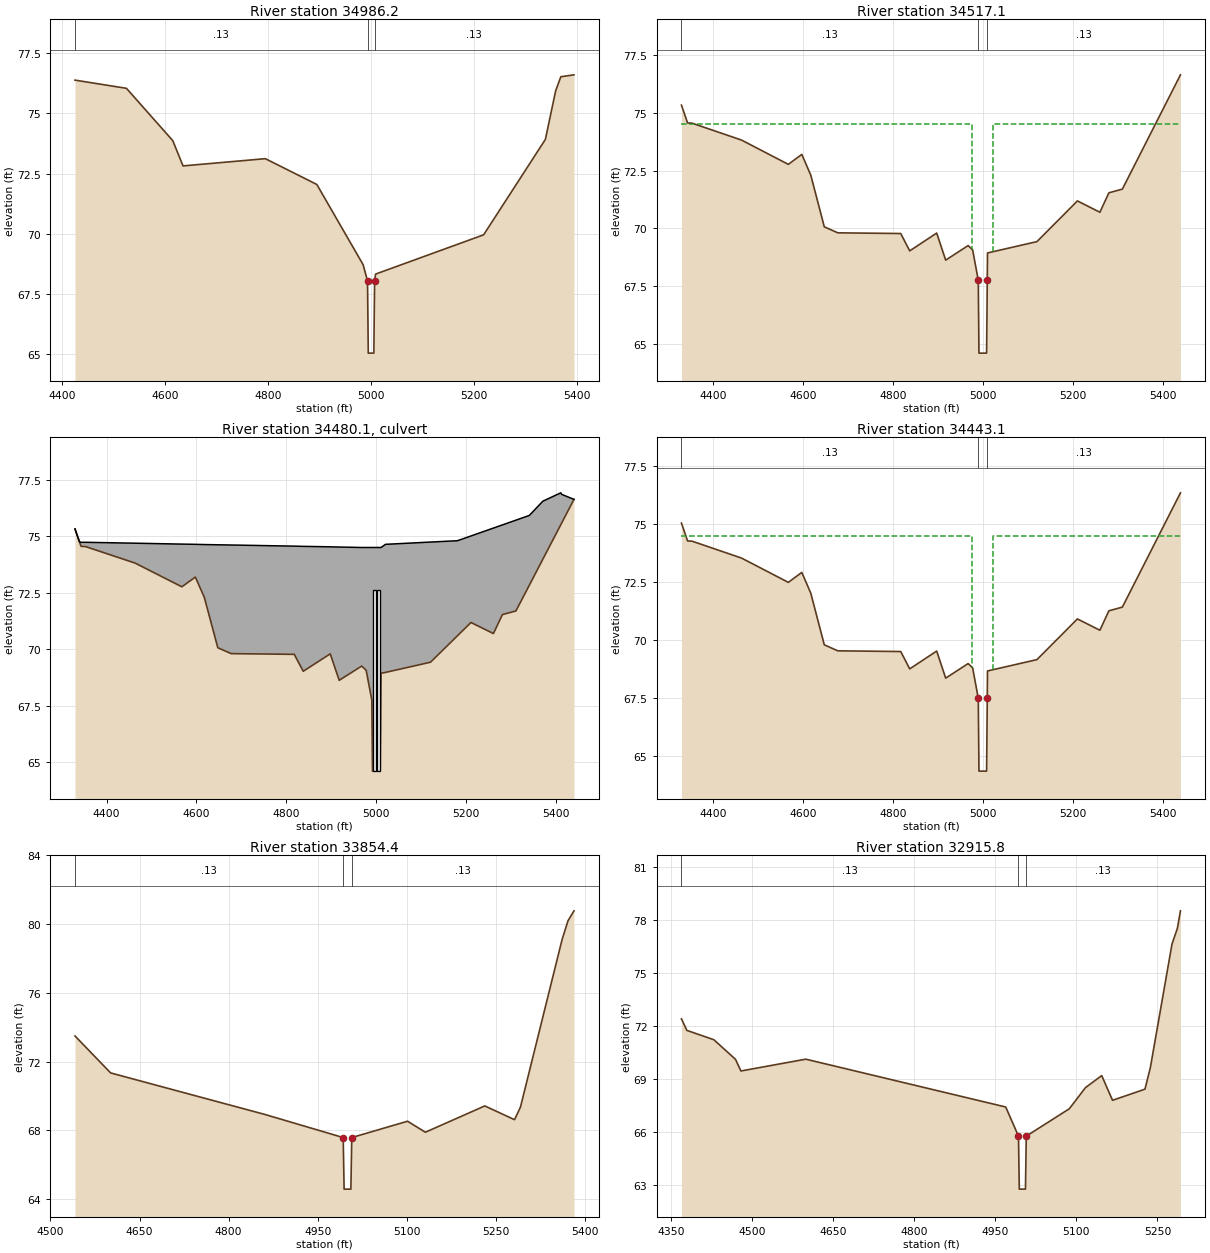
Type RM Length L Ch R = 1 ,34986.2 ,469.1,469.1,469.1
BEGIN DESCRIPTION:
Rainbow Creek 43.0
END DESCRIPTION:
XS GIS Cut Line= 3
       0.1482689       0.1420839       0.1525409       0.1199129
       0.1527452       0.1043551
#Sta/Elev= 17
  4424.6   76.38  4524.6   76.04  4614.6   73.87  4634.6   72.82  4794.6   73.12
  4894.6   72.05  4984.6   68.72  4993.1   68.05  4994.6   65.05  5005.4   65.05
  5006.9   68.05  5008.8   68.33  5218.8   69.96  5338.8   73.92  5358.8   75.94
  5368.8   76.52  5394.4    76.6
#Mann= 3 , 1 , 0
  4424.6     .13       0  4993.1    .048       0  5006.9     .13       0
Bank Sta=4993.1,5006.9
XS Rating Curve= 0 ,0
Exp/Cntr=0.5,0.3

Type RM Length L Ch R = 1 ,34517.1 ,74,74,74
BEGIN DESCRIPTION:
Upstream Section of Bridge/Culvert/Weir
END DESCRIPTION:
XS GIS Cut Line= 4
       0.1637925       0.1591277       0.1697114       0.1539584
       0.1696681       0.1236561       0.1702195       0.1074593
#Sta/Elev= 26
  4329.8   75.33  4343.4   74.56  4353.4   74.55  4463.4   73.82  4567.5   72.77
  4597.5    73.2  4617.5    72.3  4647.5   70.07  4677.5   69.81  4817.5   69.78
  4837.5   69.03  4897.5    69.8  4917.5   68.63  4967.5   69.26  4977.5   69.07
    4990   67.76  4991.5   64.61  5008.5   64.61    5010   67.76  5010.5   68.94
  5120.5   69.43  5210.5   71.19  5260.5    70.7  5280.5   71.54  5310.5    71.7
  5439.7   76.64
#Mann= 3 , 1 , 0
  4329.8     .13       0    4990    .048       0    5010     .13       0
#XS Ineff= 2 , 0
       0    4977    74.5    5023       0    74.5
Permanent Ineff=
       F       F
Bank Sta=4990,5010
XS Rating Curve= 0 ,0
Exp/Cntr=0.5,0.3

Type RM Length L Ch R = 2 ,34480.1 ,,,
BEGIN DESCRIPTION:
HWY 258 3-TOR
Structure ID: US 258-Culvert
Approximate Survey Structure
END DESCRIPTION:
Bridge Culvert--1,0,-1,-1, 0
Deck Dist Width WeirC Skew NumUp NumDn MinLoCord MaxHiCord MaxSubmerge Is_Ogee
10,54,3,0, 37, 37, , , 0.95, 0, 1,1,,
  4329.8  4339.8  4343.4  4353.4  4463.4  4567.5  4597.5  4617.5  4647.5  4677.5
  4817.5  4837.5  4897.5  4917.5  4967.5  4977.5  4979.8    4990  4991.5  4992.5
    5000  5008.5    5010  5010.2  5010.5  5020.4  5120.5  5180.4  5210.5  5260.5
  5280.5  5310.5  5340.4  5370.4  5410.4  5412.5  5439.7
   75.32   74.75   74.73   74.73   74.69   74.65   74.64   74.63   74.62   74.61
   74.56   74.55   74.53   74.52    74.5    74.5    74.5    74.5    74.5    74.5
    74.5    74.5    74.5    74.5    74.5   74.64   74.74    74.8   75.01   75.36
    75.5   75.71   75.92   76.55   76.92   76.85   76.63
   75.32   74.75   74.55   74.54   73.81   72.76   73.19   72.29   70.06    69.8
   69.77   69.02   69.79   68.62   69.25   69.06   68.82   67.75    64.6    64.6
    64.6    64.6   67.75   68.22   68.93   68.97   69.42   70.59   71.18   70.69
   71.53   71.69   72.83   73.98   75.51   75.59   76.63
  4329.8  4339.8  4343.4  4353.4  4463.4  4567.5  4597.5  4617.5  4647.5  4677.5
  4817.5  4837.5  4897.5  4917.5  4967.5  4977.5  4979.8    4990  4991.5  4992.5
    5000  5008.5    5010  5010.2  5010.5  5020.4  5120.5  5180.4  5210.5  5260.5
  5280.5  5310.5  5340.4  5370.4  5410.4  5412.5  5439.7
   75.18   74.73   74.73   74.73   74.69   74.65   74.64   74.63   74.62   74.61
   74.56   74.55   74.53   74.52    74.5    74.5    74.5    74.5    74.5    74.5
    74.5    74.5    74.5    74.5    74.5   74.64   74.74    74.8   75.01   75.36
    75.5   75.71   75.92   76.55   76.92   76.85   76.49
   75.05   74.48   74.28   74.27   73.54   72.49   72.92   72.02   69.79   69.53
    69.5   68.75   69.52   68.35   68.98   68.79   68.55   67.48   64.33   64.33
   64.33   64.33   67.48   67.95   68.66    68.7   69.15   70.32   70.91   70.42
   71.26   71.42   72.56   73.71   75.24   75.32   76.36
BR Coef= 1 , 0 , 0 ,1.25, 0 ,,,0.8,-1,2,0,
WSPro=,,,, 1 ,,,, 0 ,,,, 0 ,,,,-1 ,-1 ,-1 , 0 , 0 , 0 , 0 , 0
Culvert=2,8,8,54,0.015,0.4,1,8,1,64.6,4995.53,64.33,4995.53,Culvert #1  , 0 ,10
Culvert Bottom n=0.015
Culvert=2,8,8,54,0.015,0.4,1,8,1,64.6,5004.53,64.33,5004.53,Culvert #2  , 0 ,10
Culvert Bottom n=0.015
BR U #Sta/Elev= 37
  4329.8   75.32  4339.8   74.75  4343.4   74.55  4353.4   74.54  4463.4   73.81
  4567.5   72.76  4597.5   73.19  4617.5   72.29  4647.5   70.06  4677.5    69.8
  4817.5   69.77  4837.5   69.02  4897.5   69.79  4917.5   68.62  4967.5   69.25
  4977.5   69.06  4979.8   68.82    4990   67.75  4991.5    64.6  4992.5    64.6
    5000    64.6  5008.5    64.6    5010   67.75  5010.2   68.22  5010.5   68.93
  5020.4   68.97  5120.5   69.42  5180.4   70.59  5210.5   71.18  5260.5   70.69
  5280.5   71.53  5310.5   71.69  5340.4   72.83  5370.4   73.98  5410.4   75.51
  5412.5   75.59  5439.7   76.63
BR U #Mann= 3
  4329.8     .13    4990    .048    5010     .13
BR U Banks=4990,5010
BR D #Sta/Elev= 37
  4329.8   75.05  4339.8   74.48  4343.4   74.28  4353.4   74.27  4463.4   73.54
  4567.5   72.49  4597.5   72.92  4617.5   72.02  4647.5   69.79  4677.5   69.53
  4817.5    69.5  4837.5   68.75  4897.5   69.52  4917.5   68.35  4967.5   68.98
  4977.5   68.79  4979.8   68.55    4990   67.48  4991.5   64.33  4992.5   64.33
    5000   64.33  5008.5   64.33    5010   67.48  5010.2   67.95  5010.5   68.66
  5020.4    68.7  5120.5   69.15  5180.4   70.32  5210.5   70.91  5260.5   70.42
  5280.5   71.26  5310.5   71.42  5340.4   72.56  5370.4   73.71  5410.4   75.24
  5412.5   75.32  5439.7   76.36
BR D #Mann= 3
  4329.8     .13    4990    .048    5010     .13
BR D Banks=4990,5010
BC Design=,, 0 ,, 0 ,,,,,,
BC HTab HWMax=76.64
BC Use User HTab Curves=0
BC User HTab FreeFlow(D)= 0

Type RM Length L Ch R = 1 ,34443.1 ,588.7,588.7,588.7
BEGIN DESCRIPTION:
Downstream Section of Bridge/Culvert/Weir
END DESCRIPTION:
XS GIS Cut Line= 4
       0.1664645       0.1602803       0.1723834        0.155111
       0.1723402       0.1248087       0.1728916       0.1086118
#Sta/Elev= 26
  4329.8   75.05  4343.4   74.28  4353.4   74.27  4463.4   73.54  4567.5   72.49
  4597.5   72.92  4617.5   72.02  4647.5   69.79  4677.5   69.53  4817.5    69.5
  4837.5   68.75  4897.5   69.52  4917.5   68.35  4967.5   68.98  4977.5   68.79
    4990   67.48  4991.5   64.33  5008.5   64.33    5010   67.48  5010.5   68.66
  5120.5   69.15  5210.5   70.91  5260.5   70.42  5280.5   71.26  5310.5   71.42
  5439.7   76.36
#Mann= 3 , 1 , 0
  4329.8     .13       0    4990    .048       0    5010     .13       0
#XS Ineff= 2 , 0
       0    4977    74.5    5023       0    74.5
Permanent Ineff=
       F       F
Bank Sta=4990,5010
XS Rating Curve= 0 ,0
Exp/Cntr=0.5,0.3

Type RM Length L Ch R = 1 ,33854.4 ,938.6,938.6,938.6
BEGIN DESCRIPTION:
Rainbow Creek 42.0
END DESCRIPTION:
XS GIS Cut Line= 3
       0.1722491       0.1513562        0.185233       0.1387793
       0.1962293        0.128655
#Sta/Elev= 15
  4541.4   73.49  4601.4   71.34  4861.4   68.92  4992.8   67.58  4994.3   64.58
  5005.7   64.58  5007.2   67.58  5101.1   68.53  5131.1   67.89  5231.1   69.42
  5281.1   68.62  5291.1   69.35  5361.1   79.09  5371.1   80.19  5381.2   80.77
#Mann= 3 , 1 , 0
  4541.4     .13       0  4992.8    .048       0  5007.2     .13       0
Bank Sta=4992.8,5007.2
XS Rating Curve= 0 ,0
Exp/Cntr=0.3,0.1

Type RM Length L Ch R = 1 ,32915.8 ,802.3,802.3,802.3
BEGIN DESCRIPTION:
Rainbow Creek 41.0
END DESCRIPTION:
XS GIS Cut Line= 3
       0.2205292       0.1671832       0.2120562       0.1440023
       0.2083792       0.1329714
#Sta/Elev= 20
  4369.2    72.4  4379.2   71.75  4429.2   71.22  4469.2   70.11  4479.2   69.45
  4599.2   70.12  4969.2   67.41  4992.8   65.76  4994.3   62.76  5005.7   62.76
  5007.2   65.76  5086.8   67.31  5116.8   68.51  5146.8   69.19  5166.8   67.79
  5226.8   68.42  5236.8   69.64  5276.8   76.63  5286.8   77.53  5292.5   78.52
#Mann= 3 , 1 , 0
  4369.2     .13       0  4992.8    .048       0  5007.2     .13       0
Bank Sta=4992.8,5007.2
XS Rating Curve= 0 ,0
Exp/Cntr=0.3,0.1

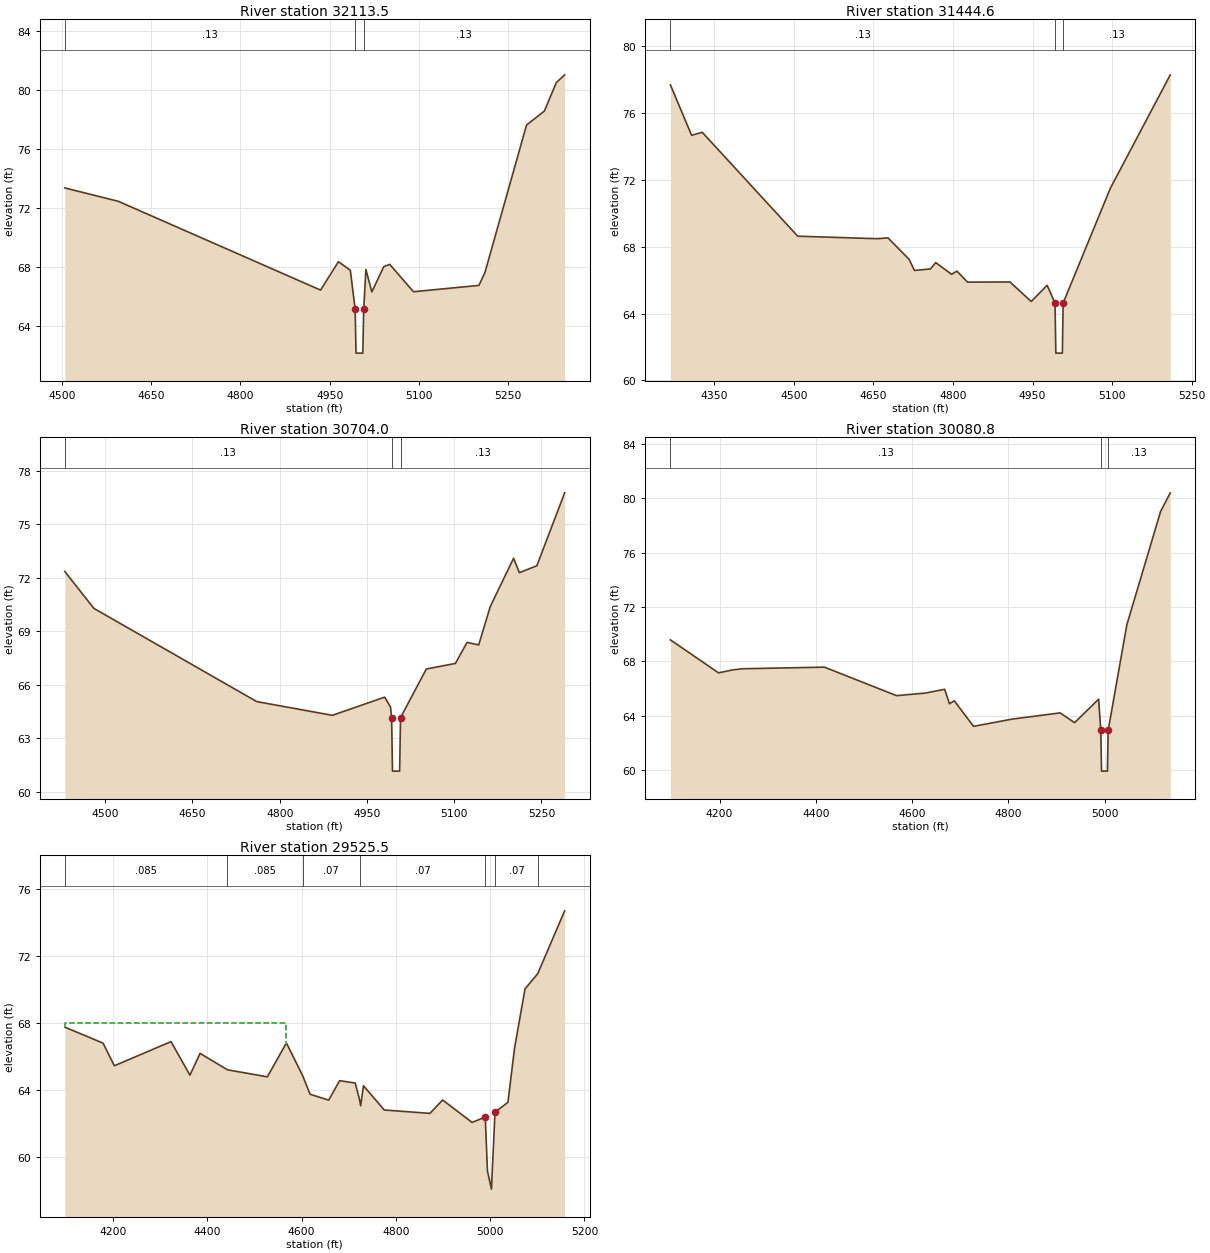
Type RM Length L Ch R = 1 ,32113.5 ,668.9,668.9,668.9
BEGIN DESCRIPTION:
Rainbow Creek 40.0
END DESCRIPTION:
XS GIS Cut Line= 3
       0.2387541        0.156472       0.2361962        0.137128
        0.232839       0.1240188
#Sta/Elev= 20
  4504.7   73.37  4594.7   72.46  4934.7   66.43  4964.7   68.36  4984.7   67.78
  4992.8   65.15  4994.3   62.15  5005.7   62.15  5007.2   65.15  5010.9   67.83
  5020.9   66.31  5040.9   68.02  5050.9   68.18  5090.9   66.32  5200.9   66.75
  5210.9   67.61  5280.9   77.64  5310.9   78.59  5330.9   80.52    5345   81.05
#Mann= 3 , 1 , 0
  4504.7     .13       0  4992.8    .048       0  5007.2     .13       0
Bank Sta=4992.8,5007.2
XS Rating Curve= 0 ,0
Exp/Cntr=0.3,0.1

Type RM Length L Ch R = 1 ,31444.6 ,740.6,740.6,740.6
BEGIN DESCRIPTION:
Rainbow Creek 39.0
END DESCRIPTION:
XS GIS Cut Line= 3
        0.276483       0.1524753       0.2577784       0.1307333
       0.2541015       0.1232195
#Sta/Elev= 22
  4267.5   77.69  4307.5   74.67  4327.5   74.85  4507.5   68.63  4657.5   68.48
  4677.5   68.53  4717.5   67.24  4727.5   66.58  4757.5   66.67  4767.5   67.05
  4797.5   66.35  4807.5   66.54  4827.5   65.88  4907.5   65.89  4947.5   64.72
  4977.5   65.69  4992.4   64.63  4993.9   61.63  5006.2   61.63  5007.7   64.63
  5096.8   71.51  5209.6   78.29
#Mann= 3 , 1 , 0
  4267.5     .13       0  4992.4    .048       0  5007.7     .13       0
Bank Sta=4992.4,5007.7
XS Rating Curve= 0 ,0
Exp/Cntr=0.3,0.1

Type RM Length L Ch R = 1 ,30704.0 ,623.2,623.2,623.2
BEGIN DESCRIPTION:
Rainbow Creek 38.0
END DESCRIPTION:
XS GIS Cut Line= 3
       0.2889526       0.1221004       0.2710474       0.1085116
        0.261935       0.1017972
#Sta/Elev= 19
  4430.5   72.36  4480.5   70.29  4760.5   65.06  4890.5   64.29  4980.5   65.31
  4990.5   64.76  4992.4   64.16  4993.9   61.16  5006.2   61.16  5007.7   64.16
  5052.1   66.89  5102.1    67.2  5122.1   68.38  5142.1   68.24  5162.1    70.4
  5202.1    73.1  5212.1   72.29  5242.1   72.68  5289.9   76.77
#Mann= 3 , 1 , 0
  4430.5     .13       0  4992.4    .048       0  5007.7     .13       0
Bank Sta=4992.4,5007.7
XS Rating Curve= 0 ,0
Exp/Cntr=0.3,0.1

Type RM Length L Ch R = 1 ,30080.8 ,555.3,555.3,555.3
BEGIN DESCRIPTION:
Rainbow Creek 37.0
END DESCRIPTION:
XS GIS Cut Line= 3
       0.3079769       0.1046748        0.277602       0.0866097
       0.2723264       0.0850111
#Sta/Elev= 22
  4097.8   69.58  4197.8   67.15  4227.8   67.37  4247.8   67.45  4417.8   67.57
  4567.8   65.47  4627.8   65.66  4667.8   65.94  4677.8   64.87  4687.8   65.09
  4727.8   63.21  4807.8   63.74  4907.8    64.2  4937.8   63.48  4987.8   65.21
  4992.3   62.91  4993.8   59.91  5006.1   59.91  5007.6   62.91  5046.5    70.7
  5116.5   79.03  5136.7   80.41
#Mann= 3 , 1 , 0
  4097.8     .13       0  4992.3    .048       0  5007.6     .13       0
Bank Sta=4992.3,5007.6
XS Rating Curve= 0 ,0
Exp/Cntr=0.3,0.1

Type RM Length L Ch R = 1 ,29525.5 ,25310.1,25310.1,25310.1
BEGIN DESCRIPTION:
Rainbow Creek 36.0
END DESCRIPTION:
XS GIS Cut Line= 3
       0.3213927        0.094847       0.2918303       0.0750993
       0.2862349       0.0725414
#Sta/Elev= 30
  4097.6  67.7664178.785   66.814202.785   65.464322.955    66.94363.095    64.9
4384.625    66.24442.615   65.224527.355    64.84567.805   66.824602.385   64.86
4618.035   63.764657.505   63.414680.655   64.574713.795   64.434722.875   63.45
4725.315   63.074731.265   64.274775.405   62.824872.295   62.624899.175   63.42
4961.715   62.084989.665    62.44994.335   59.185002.775    58.15010.335   62.69
5037.755   63.285051.865   66.535074.055   70.055100.895   70.95  5158.1  74.704
#Mann= 7 ,-1 , 0
  4097.6    .085       04442.615    .085       04602.385     .07       0
4722.875     .07       04989.665     .05       05010.335     .07       0
5100.895     .08       0
#XS Ineff= 2 , 0
       0 4567.17      68               0
Permanent Ineff=
       F       F
Bank Sta=4989.665,5010.335
XS Rating Curve= 0 ,0
Exp/Cntr=0.3,0.1

Chan Stop Cuts=-1
Use User Specified Reach Order=0
User Specified Reach Order=Rainbow Creek   ,Reach - 1