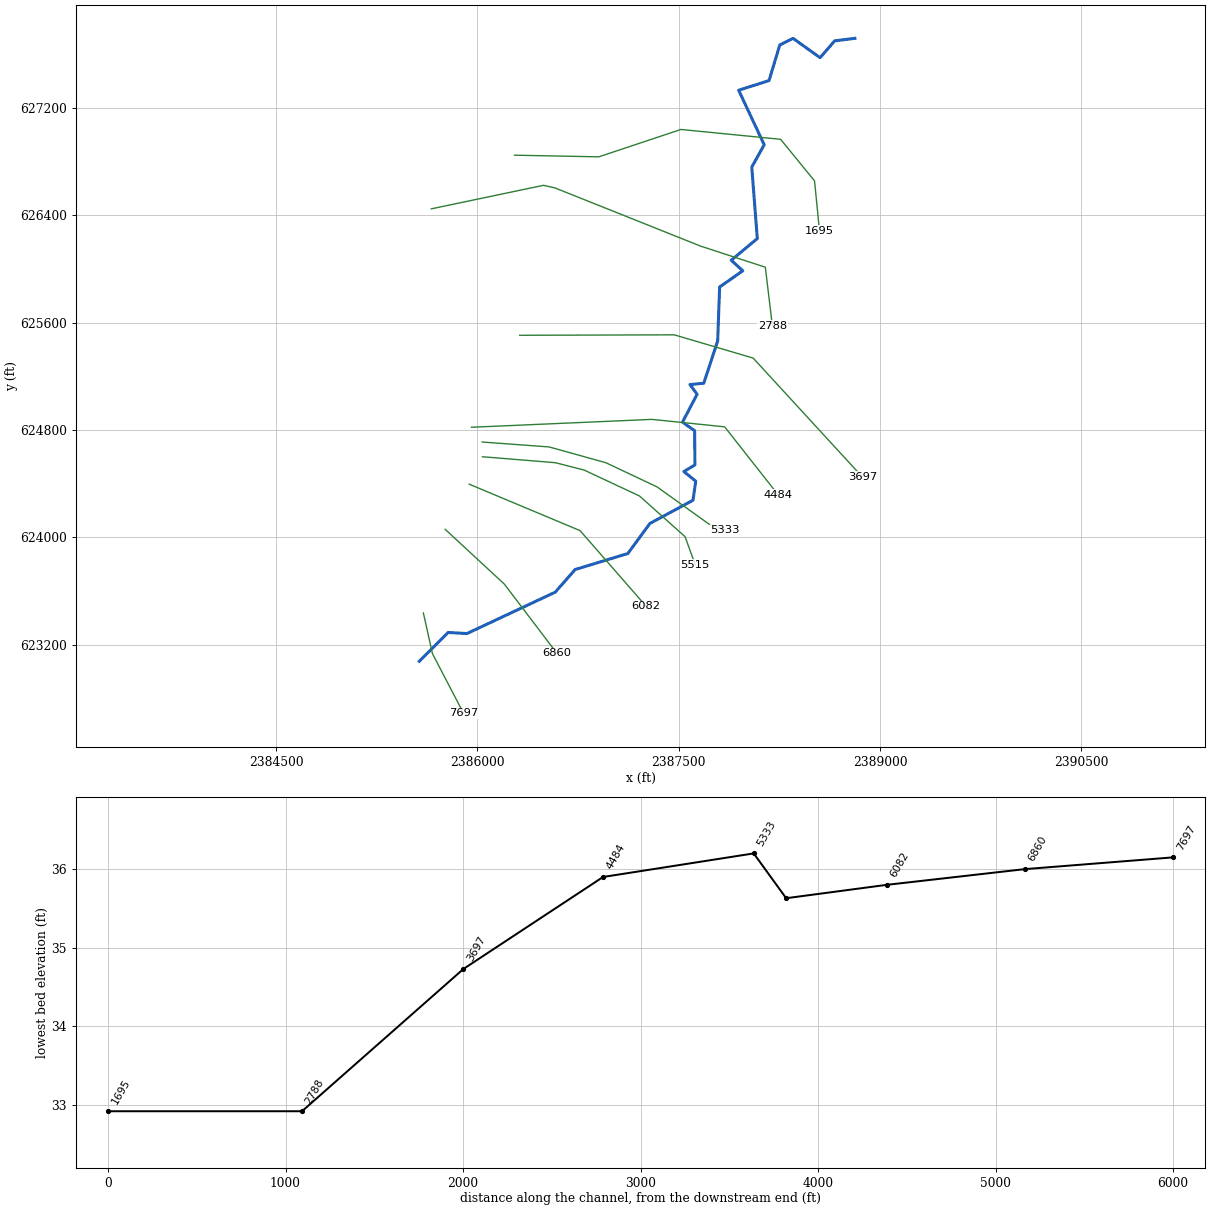
--- lds_tyson_marsh_lower.prj (project) ---

Proj Title=lds_tyson_marsh_ds
Current Plan=p01
Default Exp/Contr=0.3,0.1
English Units
Geom File=g01
Flow File=f01
Flow File=f02
Plan File=p01
Plan File=p02
Y Axis Title=Elevation
X Axis Title(PF)=Main Channel Distance
X Axis Title(XS)=Station
BEGIN DESCRIPTION:
END DESCRIPTION:
DSS Export Rating Curves= 0
DSS Export Rating Curve Sorted= 0
DSS Export Volume Flow Curves= 0
DXF OffsetX= 0
DXF OffsetY= 0
DXF ScaleX= 1
DXF ScaleY= 10

--- lds_tyson_marsh_lower.p01 (plan) ---

Plan Title=lds_tyson_marsh_ds_100-yr_FW
Program Version=4.00
Short Identifier=100-yr_FW
Geom File=g01
Flow File=f01
Subcritical Flow
K Sum by GR= 0
Std Step Tol= 0.01
Critical Tol= 0.01
Num of Std Step Trials= 20
Max Error Tol= 0.3
Flow Tol Ratio= 0.001
Split Flow NTrial= 30
Split Flow Tol= 0.02
Split Flow Ratio= 0.02
Log Output Level= 0
Friction Slope Method= 1
Unsteady Friction Slope Method= 2
Unsteady Bridges Friction Slope Method= 1
Parabolic Critical Depth
Global Vel Dist= 0 , 0 , 0
Global Log Level= 0
CheckData=True
Encroach Param=-1 ,0,0, 2
Encroach River=Tyson Marsh
Encroach Reach=Reach - 1
Encroach Node=7697
       4      .7
Encroach Node=6860
       4      .7
Encroach Node=6082
       4      .7
Encroach Node=5515
       1  1436.5  1491.5
Encroach Node=5333
       1  1593.5  1648.5
Encroach Node=4484
       4      .7
Encroach Node=3697
       4      .7
Encroach Node=2788
       4      .7
Encroach Node=1695
       4      .7
Computation Interval=1HOUR
Output Interval=1HOUR
Run HTab= 0
Run UNet= 0
Run PostProcess= 0
Run WQNet= 0
UNET Theta= 1
UNET Theta Warmup= 1
UNET ZTol= 0.02
UNET ZSATol= 0.05
UNET MxIter= 20
UNET MaxInSteps= 0
UNET DtIC= 0
UNET DtMin= 0
UNET MaxCRTS= 20
UNET WFStab= 2
UNET SFStab= 1
UNET WFX= 1
UNET SFX= 1
UNET DSS MLevel= 4
UNET DZMax Abort= 100
UNET Convert EG Bridges= 0
UNET Use Existing IB Tables=-1
UNET Froude Reduction=False
UNET Froude Limit= 1
UNET Froude Power= 10
UNET Time Slicing=0,0, 5
Instantaneous Interval=1HOUR
Write IC File= 0
Echo Input=False
Echo Output=False
Write Detailed= 0
Detailed Automatic Start=False, 10
WQ ULTIMATE=-1
WQ Max Comp Step=1HOUR
WQ Output Interval=15MIN
WQ Output Selected Increments= 0
WQ Output face flow=0
WQ Output face velocity=0
WQ Output face area=0
WQ Output face dispersion=0
WQ Output cell volume=0
WQ Output cell surface area=0
WQ Output cell continuity=0
WQ Output face conc=0
WQ Output face dconc_dx=0
WQ Output face courant=0
WQ Output face peclet=0
WQ Output face adv mass=0
WQ Output face disp mass=0
WQ Output cell mass=0
WQ Output cell source sink temp=0
WQ Output cell source sink nsm=0
WQ Output MaxMinRange=-1
WQ Daily Max Min Mean=-1
WQ Daily Range=0
WQ Daily Time=0
WQ Create Restart=0
WQ Fixed Restart=0
WQ System Summary=False
Sorting and Armoring Iterations= 10
XS Update Threshold= 0.02
Hydraulics Update Threshold= 0.02
Energy Slope Method= 1
Volume Change Method= 0
XS Weighting Method= 0
Number of US Weighted Cross Sections= 1
Number of DS Weighted Cross Sections= 1
Upstream XS Weight=0.25
Main XS Weight=0.5
Downstream XS Weight=0.25
Number of DS XS's Weighted with US Boundary= 1
Upstream Boundary Weight= 1
Weight of XSs Associated with US Boundary= 0
Number of US XS's Weighted with DS Boundary= 1
Downstream Boundary Weight= 0.5
Weight of XSs Associated with DS Boundary= 0.5
Sediment Output Level= 4
Mass or Volume Output= 0
Output Increment Type= 1
Profile and TS Output Increment= 10
XS Output Flag= 0
XS Output Increment= 10
Disregard all LS=0
Disregard all Conn=0
Disregard all Breaches=0
Disregard all Pumps=0

--- lds_tyson_marsh_lower.p02 (plan) ---

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Plan Title=lds_tyson_marsh_ds_Multi_Future
Short Identifier=Multi_Future
Geom File=g01
Flow File=f02
Encroach Param=-1 ,0,0, 0

--- lds_tyson_marsh_lower.f01 (steady flow) ---

Flow Title=lds_tyson_marsh_ds_100-yr_FW
Program Version=4.00
Number of Profiles= 2
Profile Names=100-YR,FW
River Rch & RM=Tyson Marsh,Reach - 1       ,7697
    2165    2165
River Rch & RM=Tyson Marsh,Reach - 1       ,6860
    2340    2340
Boundary for River Rch & Prof#=Tyson Marsh,Reach - 1       , 1
Up Type= 0
Dn Type= 3
Dn Slope=2.01281E-04
Boundary for River Rch & Prof#=Tyson Marsh,Reach - 1       , 2
Up Type= 0
Dn Type= 3
Dn Slope=2.01281E-04
DSS Import GetInterval= 0
DSS Import GetPeak= 0
DSS Import FillOption= 0

--- lds_tyson_marsh_lower.f02 (steady flow) ---

Flow Title=lds_tyson_marsh_ds_multi-profile
Program Version=4.00
Number of Profiles= 7
Profile Names=10-YR,25-YR,50-YR,500-YR,100-YR-10%,100-YR-20%,100-YR-35%
River Rch & RM=Tyson Marsh,Reach - 1       ,7697
     993    1398    1758    3324    3637    4661    5695
River Rch & RM=Tyson Marsh,Reach - 1       ,6860
    1083    1520    1908    3585    3928    5034    6151
Boundary for River Rch & Prof#=Tyson Marsh,Reach - 1       , 1
Up Type= 0
Dn Type= 3
Dn Slope=2.01281E-04
Boundary for River Rch & Prof#=Tyson Marsh,Reach - 1       , 2
Up Type= 0
Dn Type= 3
Dn Slope=2.01281E-04
Boundary for River Rch & Prof#=Tyson Marsh,Reach - 1       , 3
Up Type= 0
Dn Type= 3
Dn Slope=2.01281E-04
Boundary for River Rch & Prof#=Tyson Marsh,Reach - 1       , 4
Up Type= 0
Dn Type= 3
Dn Slope=2.01281E-04
Boundary for River Rch & Prof#=Tyson Marsh,Reach - 1       , 5
Up Type= 0
Dn Type= 3
Dn Slope=2.01281E-04
Boundary for River Rch & Prof#=Tyson Marsh,Reach - 1       , 6
Up Type= 0
Dn Type= 3
Dn Slope=0.00002
Boundary for River Rch & Prof#=Tyson Marsh,Reach - 1       , 7
Up Type= 0
Dn Type= 3
Dn Slope=0.00002
DSS Import GetInterval= 0
DSS Import GetPeak= 0
DSS Import FillOption= 0

--- lds_tyson_marsh_lower.g01 (geometry) ---

Geom Title=lds_tyson_marsh_ds
Program Version=4.00

River Reach=Tyson Marsh     ,Reach - 1
Reach XY= 30
2385567.74323837623076.1386255472385783.00000001623290.697265625
2385922.83138023623282.4713541722386580.85937501623590.922526062
2386728.91536461623759.5416666872387121.67578129623878.809244797
2387286.18294273624102.9505208432387606.97135417624275.682942703
2387627.53515625624417.569661453 2387539.1126302624489.541666687
2387621.36588542624538.8938802182387619.30924483624793.879557312
 2387528.8307292624857.6263020932387637.81640626 625065.31640625
2387584.35156256625137.2877604222387687.16861986625147.569661468
2387791.01367192625463.2174479512387805.40820317   625864.203125
2387978.14062501 625985.527343752387891.77408856 626063.66796878
2388086.09830733626225.0904947972388044.97135422626757.682291687
2388137.50651045626924.2454427182387947.29557292627330.371744812
2388173.49283861627402.3437500152388253.68945317627667.611328125
2388352.39388023627716.9635416872388553.91471359 627573.01953125
2388662.90104172627698.4563802182388813.51432297627717.098958343

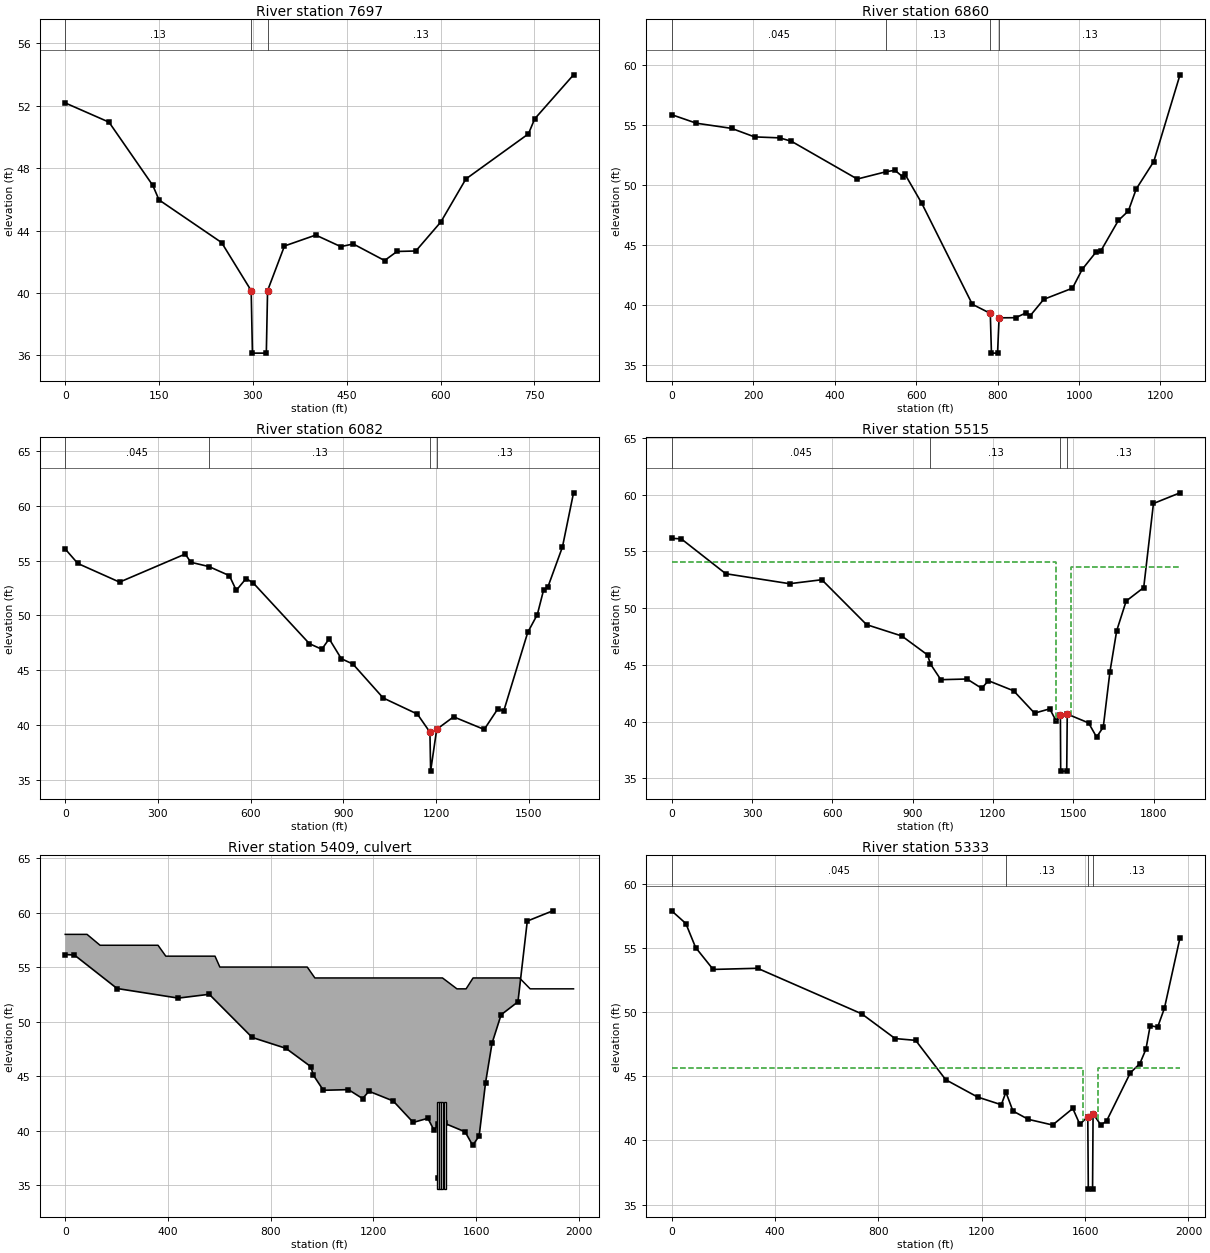
Type RM Length L Ch R = 1 ,7697    ,824.01,837.22,843.77
XS GIS Cut Line= 3
      2385598.25     623436.31252385665.75000001623133.187500015
      2385897.75622687.875000015
#Sta/Elev= 21
       0   52.17      70   50.94     140   46.89     150   45.96     250   43.23
   297.3   40.15   299.3   36.15   321.5   36.15   323.5   40.15   350.5   43.01
   400.5   43.71   440.5   42.97   460.5   43.14   510.5   42.08   530.5   42.66
   560.5   42.69   600.5   44.55   640.5    47.3   740.5   50.19   750.5   51.15
   812.6   53.97
#Mann= 3 ,-1 , 0
       0     .13       0   297.3    .046       0   323.5     .13       0
Bank Sta=297.3,323.5
XS Rating Curve= 0 ,0
Exp/Cntr=0.3,0.1

Type RM Length L Ch R = 1 ,6860    ,775.63,778.26,779.6
XS GIS Cut Line= 3
2385760.82020009624059.0977544492386201.38146307 623651.17065911
 2386592.9914746623135.550810575
#Sta/Elev= 30
       0   55.86   60.59   55.15  147.03   54.72  203.45   54.01  265.02   53.93
  293.74   53.65  455.59    50.5  526.48   51.11  547.97   51.23  567.55   50.68
   572.4   50.92  613.79   48.49  737.99   40.07  782.18   39.31     785      36
     800      36  803.77   38.94   844.5   38.95   870.4   39.36  880.51   39.13
  913.33   40.48  983.88   41.41 1007.86   42.98 1042.27   44.44 1052.81   44.47
 1096.56   47.05 1121.13   47.84  1140.4   49.67 1183.55   51.96 1247.89   59.18
#Mann= 4 ,-1 , 0
       0    .045       0  526.48     .13       0  782.18    .046       0
  803.77     .13       0
Bank Sta=782.18,803.77
XS Rating Curve= 0 ,0
Exp/Cntr=0.3,0.1

Type RM Length L Ch R = 1 ,6082    ,561.41,566.46,572.85
XS GIS Cut Line= 3
2385940.30812208 624395.229681032386765.95256308624049.307504162
2387258.72849421 623484.73640421
#Sta/Elev= 30
       0   56.05   40.79   54.73  175.86   53.03  388.35   55.59  406.39   54.84
  464.82   54.45  531.17   53.62  553.43   52.28  585.29   53.36  609.11   52.93
  789.98   47.42  830.09   46.91     854   47.86  893.19   46.05  930.86   45.56
 1028.71   42.47 1139.32      41 1179.97   39.35 1182.23    35.8 1201.85   39.61
 1256.45   40.75  1355.6    39.6 1399.48   41.47 1418.72   41.28 1496.42   48.45
 1527.39   50.07 1547.75   52.32 1561.39   52.57 1608.74   56.24 1644.56   61.17
#Mann= 4 ,-1 , 0
       0    .045       0  464.82     .13       0 1179.97     .05       0
 1201.85     .13       0
Bank Sta=1179.97,1201.85
XS Rating Curve= 0 ,0
Exp/Cntr=0.5,0.3

Type RM Length L Ch R = 1 ,5515    ,181.59,182.68,182.06
XS GIS Cut Line= 6
2386038.86330831624599.8459120542386581.89585762624555.463444084
 2386795.9759973 624500.63804248 2387208.4718761624307.443770111
2387547.86721943624004.5986945482387623.57848834623795.740021691
#Sta/Elev= 30
       0   56.15   35.99    56.1     202   53.03  440.36   52.15  560.88    52.5
  728.05   48.54  859.73   47.54  955.84   45.87  966.58   45.07 1005.32   43.69
 1103.09   43.75 1158.01   42.93 1183.01    43.6 1277.31   42.71 1355.29   40.74
 1412.21   41.12 1436.75   40.01  1451.9   40.59    1453   35.63 1475.54   35.63
 1477.54   40.66 1557.18   39.88 1587.12   38.63 1612.07   39.51 1636.92   44.38
 1662.27   48.01 1697.54   50.62 1763.14   51.81 1799.48   59.22 1898.66   60.16
#Mann= 4 ,-1 , 0
       0    .045       0  966.58     .13       0  1451.9     .05       0
 1477.54     .13       0
#XS Ineff= 2 , 0
       0  1436.5   54.03  1491.5       0    53.6
Permanent Ineff=
       F       F
Bank Sta=1451.9,1477.54
XS Rating Curve= 0 ,0
Exp/Cntr=0.5,0.3

Type RM Length L Ch R = 2 ,5409    ,,,
Bridge Culvert--1,0,-1,-1, 0
Deck Dist Width WeirC Skew NumUp NumDn MinLoCord MaxHiCord MaxSubmerge Is_Ogee
86,25,2.6,0, 56, 56, , , 0.98, 0, 0,0,,
       0      85  135.72  171.57  199.73  232.75  284.21  328.61  361.45  391.69
  433.55   472.6  503.14  531.06   557.4  561.96  583.37  602.23  634.32  664.29
  686.65  731.69  769.01  792.09  815.32  838.56  861.79  883.89  905.96  928.07
  942.69  972.22  994.39    1050 1089.61 1126.76 1168.07 1220.48  1268.5 1348.83
 1389.63 1426.18 1469.33  1525.5  1561.2 1588.35 1740.55 1769.03 1810.61 1844.35
 1873.67 1903.92 1938.42  1961.5 1974.26 1979.58
      58      58      57      57      57      57      57      57      57      56
      56      56      56      56      56      56      56      55      55      55
      55      55      55      55      55      55      55      55      55      55
      55      54      54      54      54      54      54      54      54      54
      54      54      54      53      53      54      54      54      53      53
      53      53      53      53      53      53
                                                                                
                                                                                
                                                                                
                                                                                
                                                                                
                                                
       0      85  135.72  171.57  199.73  232.75  284.21  328.61  361.45  391.69
  433.55   472.6  503.14  531.06   557.4  561.96  583.37  602.23  634.32  664.29
  686.65  731.69  769.01  792.09  815.32  838.56  861.79  883.89  905.96  928.07
  942.69  972.22  994.39    1050 1089.61 1126.76 1168.07 1220.48  1268.5 1348.83
 1389.63 1426.18 1469.33  1525.5  1561.2 1588.35 1740.55 1769.03 1810.61 1844.35
 1873.67 1903.92 1938.42  1961.5 1974.26 1979.58
      58      58      57      57      57      57      57      57      57      56
      56      56      56      56      56      56      56      55      55      55
      55      55      55      55      55      55      55      55      55      55
      55      54      54      54      54      54      54      54      54      54
      54      54      54      53      53      54      54      54      53      53
      53      53      53      53      53      53
                                                                                
                                                                                
                                                                                
                                                                                
                                                                                
                                                
BR Coef=-1 , 0 , 0 ,, 0 ,,,0.8,-1,,0,
WSPro=,,,, 1 ,,,, 0 ,,,, 0 ,,,,-1 ,-1 ,-1 , 0 , 0 , 0 , 0 , 0
Multiple Barrel Culv=2,8,8,42,0.012,0.4,1,8,1,34.62,34.22, 4,Culvert #1  , 0 ,81
  1450.5  1607.5  1459.5  1616.5  1468.5  1625.5  1477.5  1634.5
Culvert Bottom n=0.012
BC Design=,, 0 ,, 0 ,,,,,,
BC Use User HTab Curves=0
BC User HTab FreeFlow(D)= 0

Type RM Length L Ch R = 1 ,5333    ,836.53,848.87,780.22
XS GIS Cut Line= 6
2386036.25257489624709.4967152772386534.90265626624672.946447536
2386957.84146874624555.4634440842387339.00854661624375.322838783
2387725.39709133624098.5850972832387848.10156159624056.813362733
#Sta/Elev= 30
       0    57.9   54.86   56.91   92.64   55.04  160.55   53.33  332.41   53.42
  735.35   49.87  864.66   47.94  944.18    47.8 1060.55   44.73 1183.94   43.38
 1275.68   42.78 1293.38   43.76 1320.65   42.29  1380.4   41.64 1474.11    41.2
 1552.36   42.49 1579.54   41.25 1610.31   41.85 1612.31    36.21628.777    36.2
 1630.77   42.08 1660.87    41.2 1682.97   41.51 1774.95   45.27 1811.68   45.98
  1835.3   47.11 1851.78   48.95 1880.61   48.83 1906.79    50.3 1967.15    55.8
#Mann= 4 ,-1 , 0
       0    .045       0 1293.38     .13       0 1610.31     .05       0
 1630.77     .13       0
#XS Ineff= 2 , 0
       0  1593.5   45.65  1648.5       0   45.65
Permanent Ineff=
       F       F
Bank Sta=1610.31,1630.77
XS Rating Curve= 0 ,0
Exp/Cntr=0.5,0.3

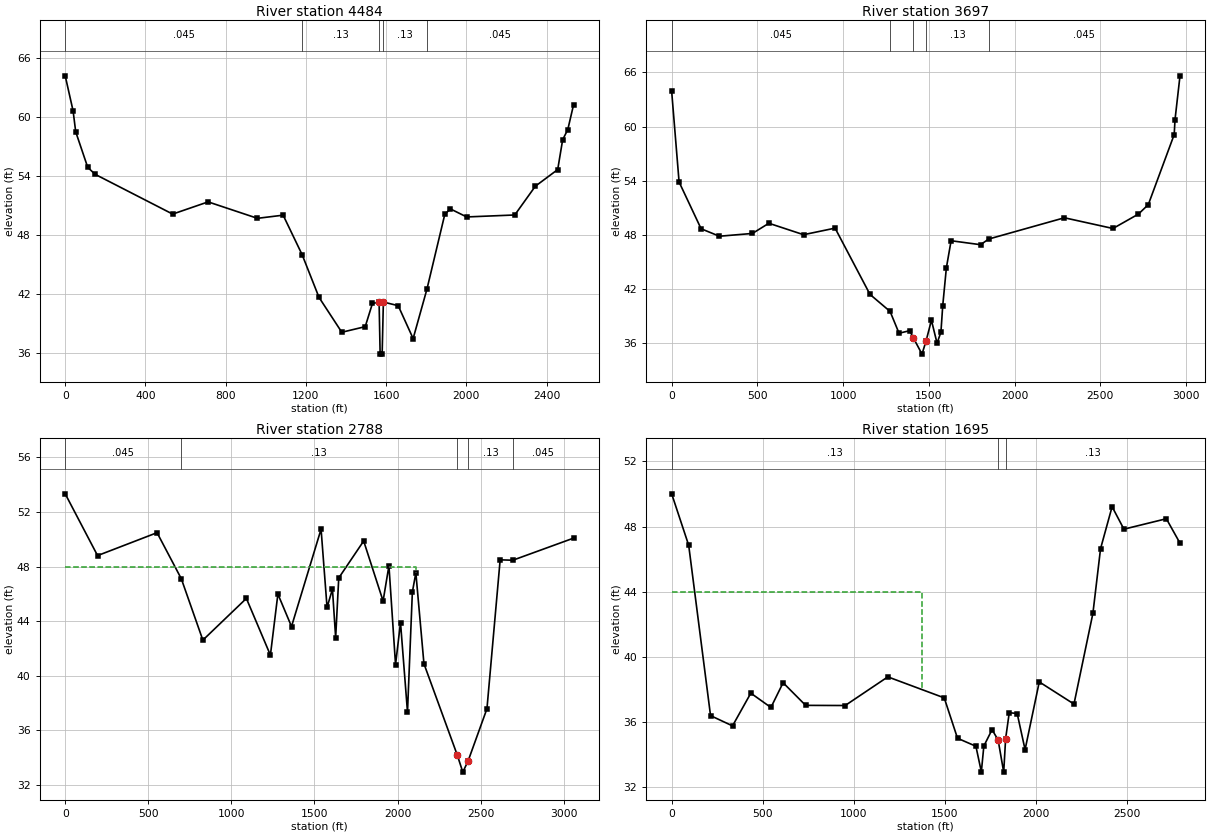
Type RM Length L Ch R = 1 ,4484    ,767.07,786.59,763.36
XS GIS Cut Line= 4
2385956.62520589624819.4738601892387301.15291214624878.215361923
2387842.88009478624822.7372769562388241.01693983624316.907678723
#Sta/Elev= 30
       0   64.16   39.31    60.6   52.33   58.48   112.2   54.87  149.12   54.16
   535.7   50.12  712.46   51.36  958.43   49.69 1086.47   50.01 1181.27   45.99
  1265.3   41.66 1378.87   38.12 1495.59   38.69  1531.8   41.06  1564.8   41.16
    1570    35.9    1580    35.9 1586.09   41.19 1659.94   40.82 1734.48   37.48
 1803.44   42.51 1892.26   50.09 1919.94   50.65 2001.35   49.83 2241.16   50.03
 2343.68   52.95 2455.14   54.64 2479.88   57.67 2505.45    58.7 2534.09   61.21
#Mann= 5 ,-1 , 0
       0    .045       0 1181.27     .13       0  1564.8     .05       0
 1586.09     .13       0 1803.44    .045       0
Bank Sta=1564.8,1586.09
XS Rating Curve= 0 ,0
Exp/Cntr=0.3,0.1

Type RM Length L Ch R = 1 ,3697    ,738.58,909.35,909.18
XS GIS Cut Line= 4
2386315.60104977625504.7913803912387467.58716704625508.054797143
2388055.00218438625335.0937087242388867.59295833624450.707765996
#Sta/Elev= 30
       0   63.89   43.23   53.84  171.62   48.65  278.36   47.82  471.04   48.13
  567.08   49.26  769.42   47.99  953.26   48.72 1156.94   41.36  1274.1   39.47
 1326.42   37.05  1388.1   37.33 1410.56   36.51 1460.33   34.73 1484.46   36.22
 1515.31   38.49 1548.18   35.94 1570.74   37.18 1581.29   40.12 1602.52   44.32
 1630.07   47.32 1801.78   46.88  1849.6   47.51 2291.06   49.87  2574.4   48.68
 2722.81   50.28 2780.43   51.33 2931.56   59.11 2936.25   60.76 2965.36   65.63
#Mann= 5 ,-1 , 0
       0    .045       0  1274.1     .13       0 1410.56     .05       0
 1484.46     .13       0  1849.6    .045       0
Bank Sta=1410.56,1484.46
XS Rating Curve= 0 ,0
Exp/Cntr=0.3,0.1

Type RM Length L Ch R = 1 ,2788    ,1083.46,1093.02,1097.01
XS GIS Cut Line= 6
2385657.20671788626446.6950435492386493.45726335626622.103694558
2386578.31660378626602.843145385 2387663.4026774626169.157992572
2388145.98655885626011.9835076482388198.59252195625573.731059492
#Sta/Elev= 30
       0   53.33  194.76    48.8  552.75   50.48  698.82    47.1  828.41    42.6
 1090.36   45.66 1234.93    41.5 1279.93   45.98 1361.94    43.6 1539.87   50.74
 1575.82      45 1608.33   46.34 1627.61   42.78 1646.19   47.16  1796.2   49.87
 1913.09   45.47 1948.26   48.06 1988.01    40.8  2017.9   43.89 2059.92   37.32
 2089.21   46.12 2110.27   47.54 2158.94   40.87 2358.95   34.19 2392.92   32.92
 2425.63   33.77 2538.13   37.57 2617.58   48.49 2693.64   48.46  3059.2   50.08
#Mann= 5 ,-1 , 0
       0    .045       0  698.82     .13       0 2358.95     .05       0
 2425.63     .13       0 2693.64    .045       0
#XS Ineff= 2 , 0
       0 2110.27      48               0
Permanent Ineff=
       F       F
Bank Sta=2358.95,2425.63
XS Rating Curve= 0 ,0
Exp/Cntr=0.3,0.1

Type RM Length L Ch R = 1 ,1695    ,1726.94,1694.78,1661.83
XS GIS Cut Line= 6
 2386277.2559028626846.4635969852386905.46362971626834.225784123
2387517.35427269627038.1893318152388259.78158624626964.762454644
2388512.69638535626654.7378621852388549.40982391626283.524205416
#Sta/Elev= 30
       0   50.01   93.49   46.85  213.51   36.39  334.23   35.76  434.75   37.77
  545.27   36.89  612.13   38.41  735.91   37.02   953.1   37.01 1187.43   38.77
 1497.34   37.48 1570.24      35 1671.23   34.51 1701.21   32.94 1714.89   34.52
 1760.01   35.53 1793.38   34.89 1824.01   32.92 1834.62   34.98 1854.45   36.57
 1898.05   36.52 1941.41    34.3 2019.37   38.46 2210.02    37.1 2314.01   42.67
    2356   46.64 2419.47   49.22 2484.39   47.84 2717.51   48.48 2792.49   46.98
#Mann= 3 , 0 , 0
       0     .13       0 1793.38     .05       0 1834.62     .13       0
#XS Ineff= 2 , 0
       0    1375      44               0
Permanent Ineff=
       F       F
Bank Sta=1793.38,1834.62
XS Rating Curve= 0 ,0
Exp/Cntr=0.3,0.1

Chan Stop Cuts=-1
Use User Specified Reach Order=0