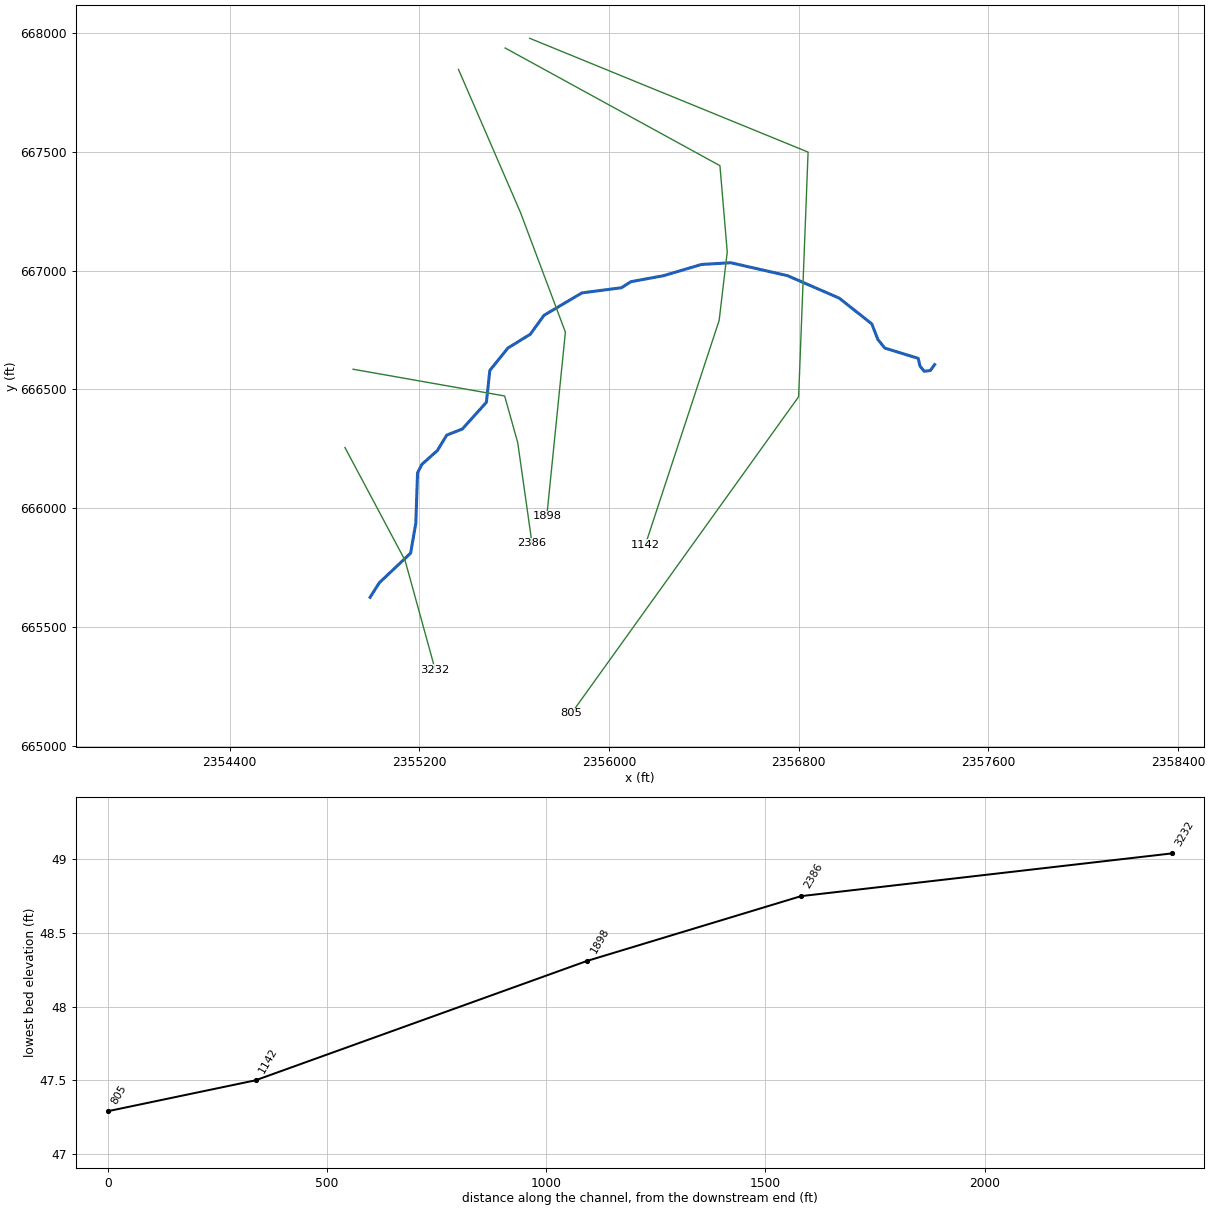
--- lds_watery_bch_lower.prj (project) ---

Proj Title=lds_watery_bch_dwnstrm
Current Plan=p01
Default Exp/Contr=0.3,0.1
English Units
Geom File=g01
Flow File=f01
Flow File=f02
Plan File=p01
Plan File=p02
Y Axis Title=Elevation
X Axis Title(PF)=Main Channel Distance
X Axis Title(XS)=Station
BEGIN DESCRIPTION:
END DESCRIPTION:
DSS File=dss
DSS Export Rating Curves= 0
DSS Export Rating Curve Sorted= 0
DSS Export Volume Flow Curves= 0
DXF OffsetX= 0
DXF OffsetY= 0
DXF ScaleX= 1
DXF ScaleY= 10

--- lds_watery_bch_lower.p01 (plan) ---

Plan Title=lds_watery_bch_dwnstrm
Program Version=4.00
Short Identifier=lds_watery_b
Geom File=g01
Flow File=f01
Subcritical Flow
K Sum by GR= 0
Std Step Tol= 0.01
Critical Tol= 0.01
Num of Std Step Trials= 20
Max Error Tol= 0.3
Flow Tol Ratio= 0.001
Split Flow NTrial= 30
Split Flow Tol= 0.02
Split Flow Ratio= 0.02
Log Output Level= 0
Friction Slope Method= 1
Unsteady Friction Slope Method= 2
Unsteady Bridges Friction Slope Method= 1
Parabolic Critical Depth
Global Vel Dist= 0 , 0 , 0
Global Log Level= 0
CheckData=True
Encroach Param=-1 ,10,10, 2
Encroach River=Water_Branch
Encroach Reach=Lower
Encroach Node=3232
       4      .7
Encroach Node=2386
       4      .7
Encroach Node=1898
       4      .7
Encroach Node=1142
       4      .7
Encroach Node=805
       4      .7
Computation Interval=1HOUR
Output Interval=1HOUR
Run HTab= 0
Run UNet= 0
Run PostProcess= 0
Run WQNet= 0
UNET Theta= 1
UNET Theta Warmup= 1
UNET ZTol= 0.02
UNET ZSATol= 0.05
UNET MxIter= 20
UNET MaxInSteps= 0
UNET DtIC= 0
UNET DtMin= 0
UNET MaxCRTS= 20
UNET WFStab= 2
UNET SFStab= 1
UNET WFX= 1
UNET SFX= 1
UNET DSS MLevel= 4
UNET DZMax Abort= 100
UNET Convert EG Bridges= 0
UNET Use Existing IB Tables=-1
UNET Froude Reduction=False
UNET Froude Limit= 1
UNET Froude Power= 10
UNET Time Slicing=0,0, 5
Instantaneous Interval=1HOUR
DSS File=dss
Write IC File= 0
Echo Input=False
Echo Output=False
Write Detailed= 0
Detailed Automatic Start=False, 10
WQ ULTIMATE=-1
WQ Max Comp Step=1HOUR
WQ Output Interval=15MIN
WQ Output Selected Increments= 0
WQ Output face flow=0
WQ Output face velocity=0
WQ Output face area=0
WQ Output face dispersion=0
WQ Output cell volume=0
WQ Output cell surface area=0
WQ Output cell continuity=0
WQ Output face conc=0
WQ Output face dconc_dx=0
WQ Output face courant=0
WQ Output face peclet=0
WQ Output face adv mass=0
WQ Output face disp mass=0
WQ Output cell mass=0
WQ Output cell source sink temp=0
WQ Output cell source sink nsm=0
WQ Output MaxMinRange=-1
WQ Daily Max Min Mean=-1
WQ Daily Range=0
WQ Daily Time=0
WQ Create Restart=0
WQ Fixed Restart=0
WQ System Summary=False
Sorting and Armoring Iterations= 10
XS Update Threshold= 0.02
Hydraulics Update Threshold= 0.02
Energy Slope Method= 1
Volume Change Method= 0
XS Weighting Method= 0
Number of US Weighted Cross Sections= 1
Number of DS Weighted Cross Sections= 1
Upstream XS Weight=0.25
Main XS Weight=0.5
Downstream XS Weight=0.25
Number of DS XS's Weighted with US Boundary= 1
Upstream Boundary Weight= 1
Weight of XSs Associated with US Boundary= 0
Number of US XS's Weighted with DS Boundary= 1
Downstream Boundary Weight= 0.5
Weight of XSs Associated with DS Boundary= 0.5
Sediment Output Level= 4
Mass or Volume Output= 0
Output Increment Type= 1
Profile and TS Output Increment= 10
XS Output Flag= 0
XS Output Increment= 10
Disregard all LS=0
Disregard all Conn=0
Disregard all Breaches=0
Disregard all Pumps=0

--- lds_watery_bch_lower.p02 (plan) ---

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Plan Title=lds_watery_bch_dwnstrm_multiprofile
Short Identifier=Multi
Geom File=g01
Flow File=f02
Encroach River=Watery Branch
Encroach Reach=Reach - 1
Encroach Node=2310
Encroach Node=1662
Encroach Node=793
Encroach Node=371

--- lds_watery_bch_lower.f01 (steady flow) ---

Flow Title=lds_watery_bch_dwnstrm
Program Version=4.00
Number of Profiles= 2
Profile Names=100YR,FW
River Rch & RM=Water_Branch,Lower           ,3232
    2286    2286
Boundary for River Rch & Prof#=Water_Branch,Lower           , 1
Up Type= 0
Dn Type= 3
Dn Slope=0.0006
Boundary for River Rch & Prof#=Water_Branch,Lower           , 2
Up Type= 0
Dn Type= 3
Dn Slope=0.0006
DSS Import GetInterval= 0
DSS Import GetPeak= 0
DSS Import FillOption= 0

--- lds_watery_bch_lower.f02 (steady flow) ---

Flow Title=lds_watery_bch_dwnstrm_multiprofile
Program Version=4.00
Number of Profiles= 7
Profile Names=10yr,25yr,50yr,500yr,100yr_10%,100yr_20%,100yr_35%
River Rch & RM=Water_Branch,Lower           ,3232
    1095    1514    1881    3435    2471    3167    3870
Boundary for River Rch & Prof#=Water_Branch,Lower           , 1
Up Type= 0
Dn Type= 3
Dn Slope=0.0006
Boundary for River Rch & Prof#=Water_Branch,Lower           , 2
Up Type= 0
Dn Type= 3
Dn Slope=0.0006
Boundary for River Rch & Prof#=Water_Branch,Lower           , 3
Up Type= 0
Dn Type= 3
Dn Slope=0.0006
Boundary for River Rch & Prof#=Water_Branch,Lower           , 4
Up Type= 0
Dn Type= 3
Dn Slope=0.0006
Boundary for River Rch & Prof#=Water_Branch,Lower           , 5
Up Type= 0
Dn Type= 3
Dn Slope=0.0006
Boundary for River Rch & Prof#=Water_Branch,Lower           , 6
Up Type= 0
Dn Type= 3
Dn Slope=0.0006
Boundary for River Rch & Prof#=Water_Branch,Lower           , 7
Up Type= 0
Dn Type= 3
Dn Slope=0.0006
DSS Import GetInterval= 0
DSS Import GetPeak= 0
DSS Import FillOption= 0

--- lds_watery_bch_lower.g01 (geometry) ---

Geom Title=lds_watery_bch_dwnstm
Program Version=4.00

River Reach=Water_Branch    ,Lower
Reach XY= 30
2354992.83251953665624.1795043952355031.25012207     665685.0625
2355163.75012207 665810.250122072355185.50012207     665937.1875
2355192.75012207 666147.625122072355211.00012207 666183.87512207
2355276.25012207     666241.93752355316.00012207     666307.1875
2355381.50012207 666332.625122072355483.00012207     666445.0625
2355497.50012207     666579.31252355573.75012207 666673.62512207
2355668.00012207 666731.625122072355726.00012207     666811.4375
2355885.75012207 666905.750122072356052.50012207     666927.5625
2356092.50012207     666952.93752356230.25012207     666978.3125
2356390.00012207 667025.500122072356513.25048828 667032.75012207
2356752.75012207     666978.31252356970.25012207 666884.00012207
2357108.25012207     666775.18752357133.50012207 666709.87512207
2357162.50012207 666673.625122072357304.00012207     666630.0625
2357311.25012207     666597.43752357329.50012207     666575.6875
2357355.00012207     666579.31252357373.00012207 666603.87512207

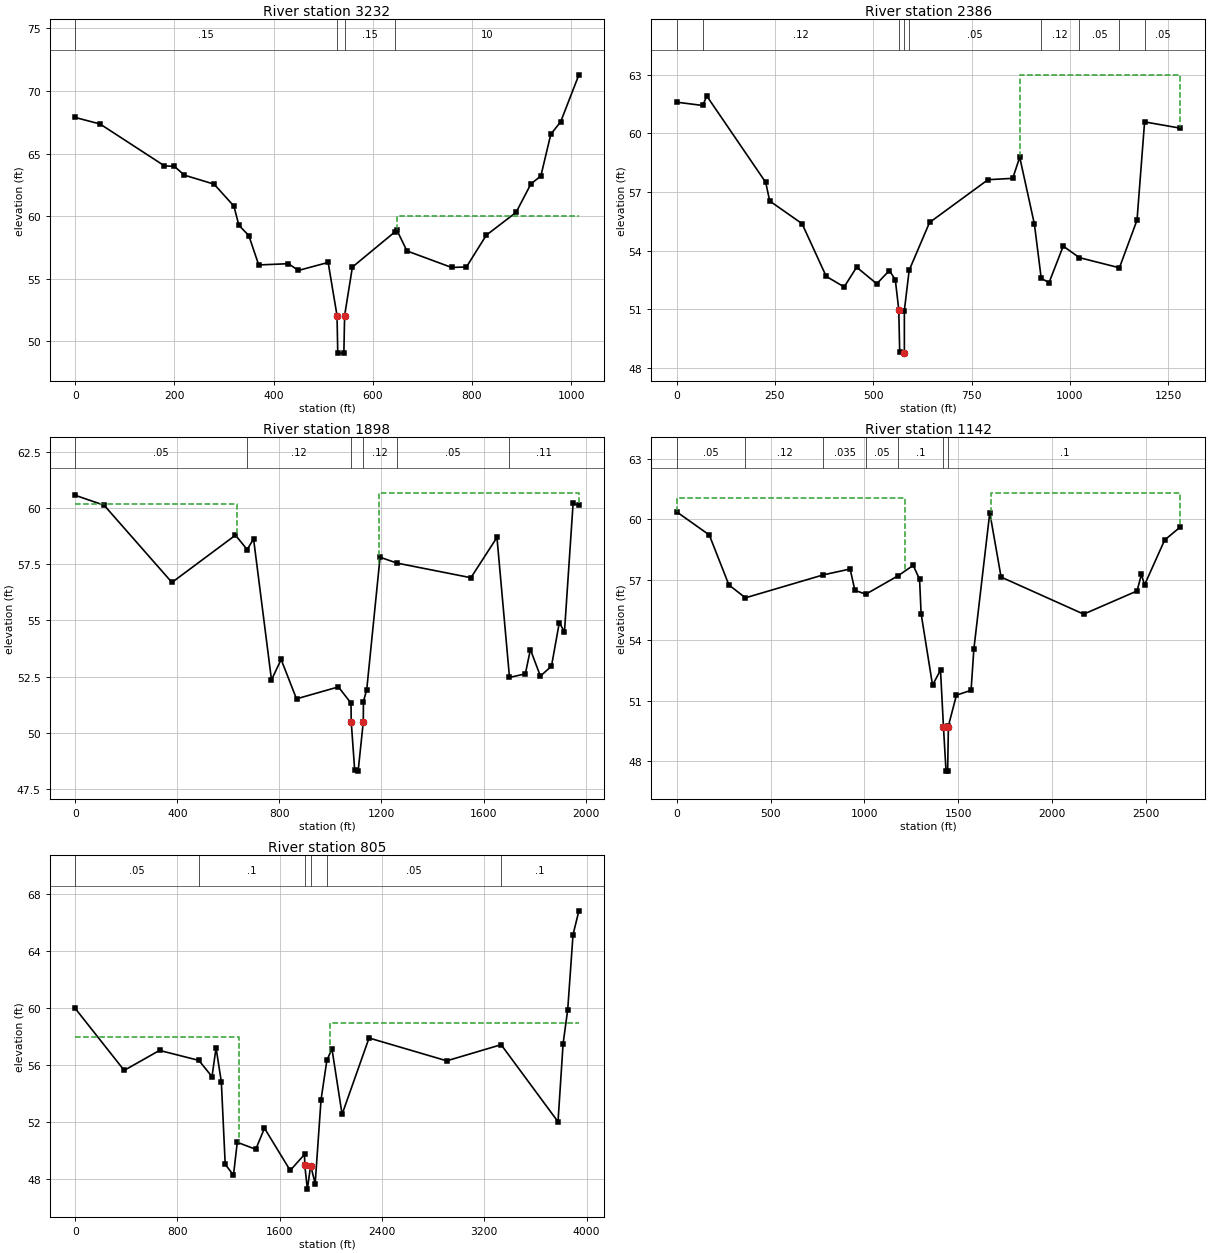
Type RM Length L Ch R = 1 ,3232    ,630.98,845.58,909.73
XS GIS Cut Line= 3
2354886.62512207 666254.859497072355140.20831299665779.401123047
2355266.98422579665319.825096463
#Sta/Elev= 30
       0   67.88      50   67.36     180   64.01     200   63.97     220   63.27
     280   62.55     320   60.79     330   59.26     350   58.44     370   56.09
     430   56.19     450   55.65     510   56.29   527.9   52.04   529.4   49.04
   541.7   49.04   543.2   52.04   558.9   55.92   645.4   58.76   648.9   58.85
   668.9   57.21   758.9   55.89   788.9   55.93   828.9   58.47   888.9   60.29
   918.9   62.57   938.9    63.2   958.9   66.53   978.9   67.54  1015.6   71.29
#Mann= 4 ,-1 , 0
       0     .15       0   527.9    .048       0   543.2     .15       0
   645.4      10       0
#XS Ineff= 2 , 0
       0                   648.9       0      60
Permanent Ineff=
       F       F
Bank Sta=527.9,543.2
XS Rating Curve= 0 ,0
Exp/Cntr=0.3,0.1

Type RM Length L Ch R = 1 ,2386    ,717.8,488.27,419.89
XS GIS Cut Line= 4
2354921.10290527666584.4199218752355560.02087402666471.835083008
2355615.13372803666275.5421142582355675.27148438665852.265319824
#Sta/Elev= 30
       0    61.6   66.68   61.43   76.65   61.92   226.7   57.49  236.65   56.54
   318.9   55.38  380.39   52.68  426.01   52.14  457.69   53.15  508.89    52.3
  540.88   52.98  555.95   52.51  564.75   50.98  567.12   48.81  578.98   48.75
  578.98   50.93  591.17   52.99  643.01   55.44  791.59   57.63  854.39    57.7
  872.22   58.78  909.48   55.36  926.84   52.58  946.77   52.36  982.75   54.23
 1023.68   53.64 1125.59   53.12 1170.34   55.56 1189.58   60.59 1280.17   60.27
#Mann= 9 ,-1 , 0
       0     .05       0   66.68     .12       0  564.75     .05       0
  578.98     .12       0  591.17     .05       0  926.84     .12       0
 1023.68     .05       0 1125.59     .12       0 1189.58     .05       0
#XS Ineff= 2 , 0
       0                  872.22       0      63
Permanent Ineff=
       F       F
Bank Sta=564.75,578.98
XS Rating Curve= 0 ,0
Exp/Cntr=0.3,0.1

Type RM Length L Ch R = 1 ,1898    ,792.9,755.71,689.49
XS GIS Cut Line= 4
2355365.49249268667846.4036865232355626.54949951667244.882873535
2355816.11431885666740.6406860352355737.72210693 665965.60168457
#Sta/Elev= 30
       0   60.56  113.08   60.12  378.92   56.69   627.9   58.79  673.55   58.15
  698.84   58.62  769.02   52.36  806.73   53.27  866.99   51.52 1031.09   52.05
 1080.52   51.33 1081.36   50.51 1094.92   48.36 1108.47   48.31 1128.81   50.51
 1129.14    51.4 1142.17   51.93 1194.42   57.81 1260.23   57.55 1550.39    56.9
 1652.38   58.69 1701.52   52.47  1763.6   52.63 1783.45   53.71 1822.53   52.53
 1865.98   52.97 1896.77   54.91 1916.85   54.49 1950.76   60.21 1973.42   60.11
#Mann= 6 ,-1 , 0
       0     .05       0  673.55     .12       0 1080.52     .05       0
 1128.81     .12       0 1260.23     .05       0 1701.52     .11       0
#XS Ineff= 2 , 0
       0  632.62   60.16 1191.76       0   60.67
Permanent Ineff=
       F       F
Bank Sta=1081.36,1128.81
XS Rating Curve= 0 ,0
Exp/Cntr=0.3,0.1

Type RM Length L Ch R = 1 ,1142    ,351.54,337.16,355.31
XS GIS Cut Line= 5
2355562.19891357667936.8314819342356467.80249023667441.415283203
2356498.54730225667078.0659179692356464.42547607666789.927490234
2356153.53948975665845.895080566
#Sta/Elev= 30
       0   60.37   174.1   59.22  278.51   56.74  366.53    56.1  781.51   57.24
  923.85   57.53   949.2   56.47 1007.45   56.28  1178.5   57.19 1259.62   57.71
 1293.51   57.02 1301.62   55.32 1362.51   51.77 1404.95   52.51 1420.58   49.71
  1434.3    47.5 1442.88   47.51  1446.9   49.68 1447.45   49.76 1489.67   51.27
 1567.62   51.51  1582.4   53.55 1667.22   60.33 1727.36   57.13 2167.05   55.29
 2451.03   56.44 2474.42   57.26    2491   56.74 2598.17   58.97 2680.96   59.61
#Mann= 7 ,-1 , 0
       0     .05       0  366.53     .12       0  781.51    .035       0
 1007.45     .05       0  1178.5      .1       0 1420.58     .05       0
 1447.45      .1       0
#XS Ineff= 2 , 0
       0 1217.74   61.07 1674.73       0   61.31
Permanent Ineff=
       F       F
Bank Sta=1420.58,1446.9
XS Rating Curve= 0 ,0
Exp/Cntr=0.3,0.1

Type RM Length L Ch R = 1 ,805     ,642.69,726.18,645.68
XS GIS Cut Line= 4
 2355665.9005127667977.5748901372356839.46411133667498.569274902
  2356799.546875666468.7072753912355841.53588867665135.475280762
#Sta/Elev= 30
       0   59.95   383.1   55.61  659.42   57.01   967.1   56.31 1069.94   55.17
  1101.7   57.19 1142.91   54.81 1173.14   49.03 1237.98   48.27 1267.56   50.57
 1412.35   50.08 1480.36   51.56 1681.71    48.6 1793.58   49.72 1795.58   48.96
 1815.92   47.29 1841.55   48.94 1877.03   47.68 1922.82   53.55 1968.35   56.31
 2008.29   57.12 2087.47   52.53 2298.44   57.88 2906.37   56.28 3331.67   57.41
 3776.63   52.01 3816.46   57.49 3852.48   59.86 3894.05   65.12 3939.93   66.79
#Mann= 6 ,-1 , 0
       0     .05       0   967.1      .1       0 1793.58     .05       0
 1841.55      .1       0 1968.35     .05       0 3331.67      .1       0
#XS Ineff= 2 , 0
       0 1283.15   57.94 1992.75       0    58.9
Permanent Ineff=
       F       F
Bank Sta=1795.58,1841.55
XS Rating Curve= 0 ,0
Exp/Cntr=0.3,0.1
Stream Node=Water_Branch    ,Lower           , 0 , 0 ,Upstream end
Stream Node=Water_Branch    ,Lower           , 0 , 1 ,Downstream end

Chan Stop Cuts=-1
Use User Specified Reach Order=0