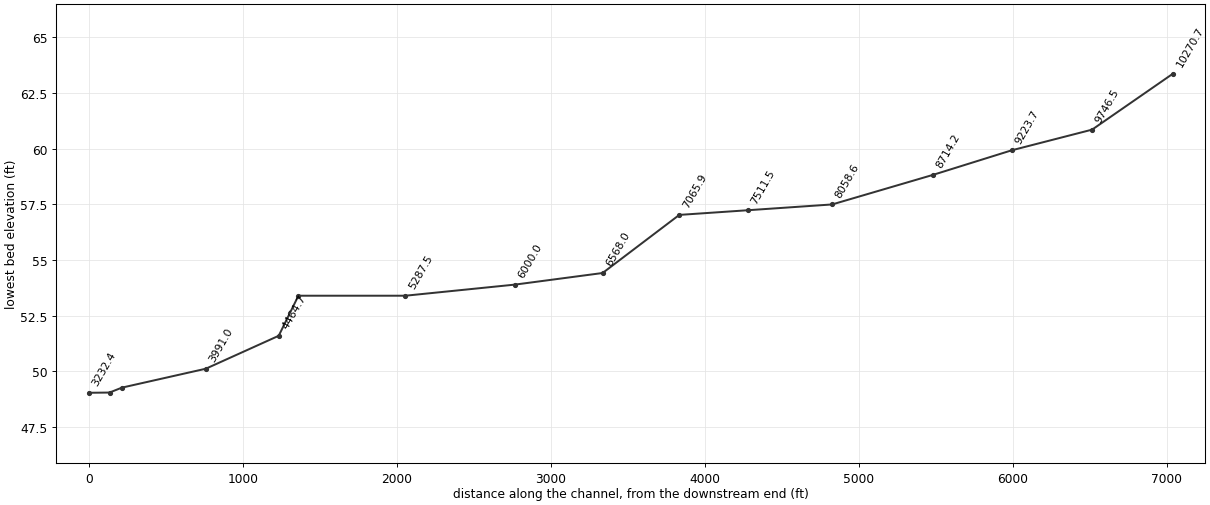
--- lds_watery_bch_upper.prj (project) ---

Proj Title=Watery Branch
Current Plan=p01
Default Exp/Contr=0.3,0.1
English Units
Geom File=g01
Flow File=f01
Flow File=f02
Plan File=p01
Plan File=p02
Y Axis Title=Elevation
X Axis Title(PF)=Main Channel Distance
X Axis Title(XS)=Station
BEGIN DESCRIPTION:
NEUSE RIVER BASIN
Little Contentnea Creek Sub-basin
WATERY BRANCH
(Flood Hazard, Floodway) Model
Prepared by: Andrew J. Bonner   Date: 11/26/2002
Watershed Concepts
3333 Regency Pkwy
Cary, North Carolina 27511
END DESCRIPTION:
DSS Export Rating Curves= 0
DSS Export Rating Curve Sorted= 0
DSS Export Volume Flow Curves= 0
DXF Filename=..\..\..\..\..\..\..\HYDRA\GREENE\Watery_Branch\UPPER\Watery_Branch_021220.
DXF OffsetX= 0
DXF OffsetY= 0
DXF ScaleX= 1
DXF ScaleY= 10

--- lds_watery_bch_upper.p01 (plan) ---

Plan Title=100 Year Single
Program Version=4.00
Short Identifier=Plan01
Geom File=g01
Flow File=f01
Subcritical Flow
K Sum by GR= 0
Std Step Tol= 0.01
Critical Tol= 0.01
Num of Std Step Trials= 20
Max Error Tol= 0.3
Flow Tol Ratio= 0.001
Split Flow NTrial= 30
Split Flow Tol= 0.02
Split Flow Ratio= 0.02
Log Output Level= 0
Friction Slope Method= 1
Unsteady Friction Slope Method= 2
Unsteady Bridges Friction Slope Method= 1
Parabolic Critical Depth
Global Vel Dist= 0 , 0 , 0
Global Log Level= 0
CheckData=True
Encroach Param=-1 ,10,10, 2
Encroach River=Watery Branch
Encroach Reach=Reach - 1
Encroach Node=10270.7
       4      .7
Encroach Node=9746.5
       4      .7
Encroach Node=9223.7
       4      .7
Encroach Node=8714.2
       4      .7
Encroach Node=8058.6
       4      .7
Encroach Node=7511.5
       4      .7
Encroach Node=7065.9
       4      .7
Encroach Node=6568.0
       4      .7
Encroach Node=6000.0
       4      .7
Encroach Node=5287.5
       4      .7
Encroach Node=4592.7
       1    4977    5023
Encroach Node=4464.7
       1    4977    5023
Encroach Node=3991.0
       4      .7
Encroach Node=3446.0
       4      .7
Encroach Node=3366.0
       4      .7
Encroach Node=3232.4
       1 4889.32  5017.7
Computation Interval=1HOUR
Output Interval=1HOUR
Run HTab= 0
Run UNet= 0
Run PostProcess= 0
Run WQNet= 0
UNET Theta= 1
UNET Theta Warmup= 1
UNET ZTol= 0.02
UNET ZSATol= 0.1
UNET MxIter= 20
UNET MaxInSteps= 20
UNET DtIC= 0
UNET DtMin= 0
UNET MaxCRTS= 20
UNET WFStab= 2
UNET SFStab= 1
UNET WFX= 1
UNET SFX= 1
UNET DSS MLevel= 4
UNET DZMax Abort= 100
UNET Convert EG Bridges=-1
UNET Use Existing IB Tables=-1
UNET Froude Reduction=False
UNET Froude Limit= 1
UNET Froude Power= 10
UNET Time Slicing=0,0, 5
Instantaneous Interval=1HOUR
Write IC File= 0
Echo Input=False
Echo Output=False
Write Detailed= 0
Detailed Automatic Start=False, 10
WQ ULTIMATE=-1
WQ Max Comp Step=1HOUR
WQ Output Interval=15MIN
WQ Output Selected Increments= 0
WQ Output face flow=0
WQ Output face velocity=0
WQ Output face area=0
WQ Output face dispersion=0
WQ Output cell volume=0
WQ Output cell surface area=0
WQ Output cell continuity=0
WQ Output face conc=0
WQ Output face dconc_dx=0
WQ Output face courant=0
WQ Output face peclet=0
WQ Output face adv mass=0
WQ Output face disp mass=0
WQ Output cell mass=0
WQ Output cell source sink temp=0
WQ Output cell source sink nsm=0
WQ Output MaxMinRange=-1
WQ Daily Max Min Mean=-1
WQ Daily Range=0
WQ Daily Time=0
WQ Create Restart=0
WQ Fixed Restart=0
WQ System Summary=False
Sorting and Armoring Iterations= 10
XS Update Threshold= 0.02
Hydraulics Update Threshold= 0.02
Energy Slope Method= 1
Volume Change Method= 0
XS Weighting Method= 0
Number of US Weighted Cross Sections= 1
Number of DS Weighted Cross Sections= 1
Upstream XS Weight=0.25
Main XS Weight=0.5
Downstream XS Weight=0.25
Number of DS XS's Weighted with US Boundary= 1
Upstream Boundary Weight= 1
Weight of XSs Associated with US Boundary= 0
Number of US XS's Weighted with DS Boundary= 1
Downstream Boundary Weight= 0.5
Weight of XSs Associated with DS Boundary= 0.5
Sediment Output Level= 4
Mass or Volume Output= 0
Output Increment Type= 1
Profile and TS Output Increment= 10
XS Output Flag= 0
XS Output Increment= 10
Disregard all LS=0
Disregard all Conn=0
Disregard all Breaches=0
Disregard all Pumps=0

--- lds_watery_bch_upper.p02 (plan) ---

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Plan Title=MultiProfile
Short Identifier=MultiProfile
Geom File=g01
Flow File=f02

--- lds_watery_bch_upper.f01 (steady flow) ---

Flow Title= 100 Year Single
Program Version=4.00
Number of Profiles= 2
Profile Names=100-Year,AFW
River Rch & RM=Watery Branch,Reach - 1       ,10270.7
    1900    1900
River Rch & RM=Watery Branch,Reach - 1       ,9746.5
    1968    1968
River Rch & RM=Watery Branch,Reach - 1       ,8714.2
    2218    2218
River Rch & RM=Watery Branch,Reach - 1       ,6000.0
    2286    2286
Boundary for River Rch & Prof#=Watery Branch,Reach - 1       , 1
Up Type= 0
Dn Type= 1
Dn Known WS=58.92
Boundary for River Rch & Prof#=Watery Branch,Reach - 1       , 2
Up Type= 0
Dn Type= 1
Dn Known WS=59.55
DSS Import GetInterval= 0
DSS Import GetPeak= 0
DSS Import FillOption= 0

--- lds_watery_bch_upper.f02 (steady flow) ---

Flow Title=MultiProfile
Program Version=4.00
Number of Profiles= 7
Profile Names=10yr,25yr,50yr,500yr,100yr_10%,100yr_20%,100yr_35%
River Rch & RM=Watery Branch,Reach - 1       ,10270.7
     900    1251    1558    2871    2073    2657    3246
River Rch & RM=Watery Branch,Reach - 1       ,9746.5
     935    1297    1615    2971    2144    2748    3357
River Rch & RM=Watery Branch,Reach - 1       ,8714.2
    1060    1467    1823    3334    2401    3077    3759
River Rch & RM=Watery Branch,Reach - 1       ,6000.0
    1095    1514    1881    3435    2471    3167    3870
Boundary for River Rch & Prof#=Watery Branch,Reach - 1       , 1
Up Type= 0
Dn Type= 1
Dn Known WS=57.35
Boundary for River Rch & Prof#=Watery Branch,Reach - 1       , 2
Up Type= 0
Dn Type= 1
Dn Known WS=58.07
Boundary for River Rch & Prof#=Watery Branch,Reach - 1       , 3
Up Type= 0
Dn Type= 1
Dn Known WS=58.53
Boundary for River Rch & Prof#=Watery Branch,Reach - 1       , 4
Up Type= 0
Dn Type= 1
Dn Known WS=59.79
Boundary for River Rch & Prof#=Watery Branch,Reach - 1       , 5
Up Type= 0
Dn Type= 1
Dn Known WS=59.06
Boundary for River Rch & Prof#=Watery Branch,Reach - 1       , 6
Up Type= 0
Dn Type= 1
Dn Known WS=59.54
Boundary for River Rch & Prof#=Watery Branch,Reach - 1       , 7
Up Type= 0
Dn Type= 1
Dn Known WS=60.09
DSS Import GetInterval= 0
DSS Import GetPeak= 0
DSS Import FillOption= 0

--- lds_watery_bch_upper.g01 (geometry) ---

Geom Title=Geom 01 by CodeH2 for Windows
Program Version=4.00

River Reach=Watery Branch   ,Reach - 1
Reach XY= 30
  0.053810764103   0.05730744216  0.075103933517  0.083221257552
   0.10444071229  0.102978475019  0.136308471822   0.10088338539
  0.164883445473  0.109972820262  0.211783925055   0.14615379284
  0.240722476101  0.151014882871  0.266790071392  0.145696810203
  0.279383207209  0.159986807922  0.308550249573  0.163053613378
  0.329691471599  0.178191790959  0.344699082712  0.178257074193
  0.375236068631  0.194178148402  0.429067618937  0.200898806241
  0.491838452677  0.230914028468  0.508542423513  0.225237400192
  0.546583466078  0.229935282138  0.553173557449  0.223671104757
  0.591736363706  0.238417582935  0.611050659541  0.272543640181
  0.636530705727   0.29841538577  0.665948837453  0.389075217027
  0.666146193691  0.408458311346  0.684429516609  0.444637777388
  0.728054284386  0.464234799843     0.752580191   0.48559597615
  0.823289968159   0.57430484307  0.870957274649  0.596852667697
  0.900031916129  0.601797119396  0.943553873427  0.643301140239

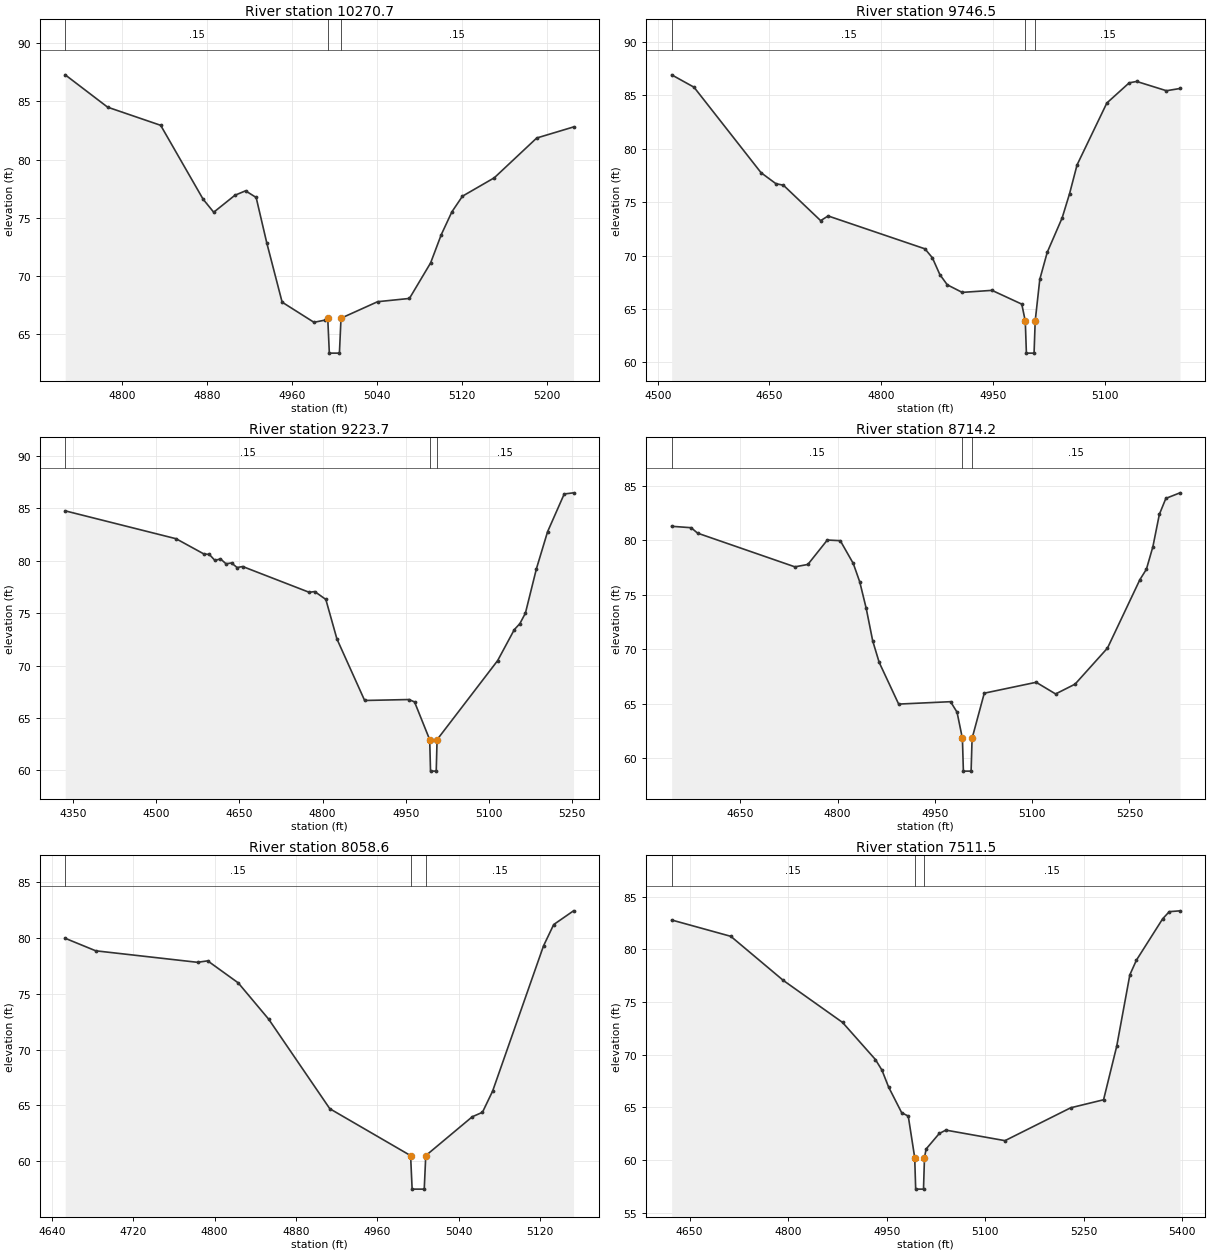
Type RM Length L Ch R = 1 ,10270.7 ,524.2,524.2,524.2
BEGIN DESCRIPTION:
Watery Branch 10.0
END DESCRIPTION:
#Sta/Elev= 25
  4746.2   87.29  4786.2   84.51  4836.2   82.95  4876.2    76.6  4886.2   75.48
  4906.2   76.94  4916.2   77.32  4926.2   76.75  4936.2   72.85  4950.7   67.75
  4980.7   66.02  4990.7    66.2  4993.7   66.37  4995.2   63.37  5004.7   63.37
  5006.2   66.37  5040.7   67.79  5070.7   68.07  5090.7   71.13  5100.7   73.55
  5110.7   75.51  5120.7   76.86  5150.7   78.44  5190.7   81.86  5225.4   82.81
#Mann= 3 , 1 , 0
  4746.2     .15       0  4993.7    .048       0  5006.2     .15       0
Bank Sta=4993.7,5006.2
XS Rating Curve= 0 ,0
Exp/Cntr=0.3,0.1

Type RM Length L Ch R = 1 ,9746.5  ,522.8,522.8,522.8
BEGIN DESCRIPTION:
Watery Branch 9.0
END DESCRIPTION:
#Sta/Elev= 28
  4518.7   86.93  4548.7   85.77  4638.7   77.76  4658.7   76.73  4668.7   76.59
  4718.7   73.27  4728.7   73.71  4858.7   70.63  4868.7   69.79  4878.7   68.22
  4888.7   67.26  4908.7   66.55  4948.7   66.74  4988.7   65.45  4993.4   63.86
  4994.9   60.86  5005.2   60.86  5006.7   63.86  5012.9   67.78  5022.9   70.31
  5042.9   73.53  5052.9   75.81  5062.9   78.49  5102.9   84.29  5132.9   86.18
  5142.9   86.31  5182.9   85.44  5201.1   85.65
#Mann= 3 , 1 , 0
  4518.7     .15       0  4993.4    .048       0  5006.7     .15       0
Bank Sta=4993.4,5006.7
XS Rating Curve= 0 ,0
Exp/Cntr=0.3,0.1

Type RM Length L Ch R = 1 ,9223.7  ,509.5,509.5,509.5
BEGIN DESCRIPTION:
Watery Branch 8.5
END DESCRIPTION:
#Sta/Elev= 29
    4336   84.76    4536    82.1    4586   80.65    4596    80.6    4606   80.03
    4616   80.18    4626   79.71    4636   79.79    4646   79.35    4656   79.45
    4776   76.99    4786   77.06    4806   76.31    4826   72.54    4876   66.67
    4956   66.76    4966   66.53  4993.3   62.93  4994.8   59.93  5005.1   59.93
  5006.6   62.93  5115.9   70.48  5145.9   73.43  5155.9      74  5165.9      75
  5185.9   79.26  5205.9   82.77  5235.9   86.37  5252.7   86.48
#Mann= 3 , 1 , 0
    4336     .15       0  4993.3    .048       0  5006.6     .15       0
Bank Sta=4993.3,5006.6
XS Rating Curve= 0 ,0
Exp/Cntr=0.3,0.1

Type RM Length L Ch R = 1 ,8714.2  ,655.6,655.6,655.6
BEGIN DESCRIPTION:
Watery Branch 8.0
END DESCRIPTION:
#Sta/Elev= 30
  4544.2   81.29  4574.2   81.16  4584.2   80.66  4734.2   77.57  4754.2   77.79
  4784.2   80.03  4804.2   79.97  4824.2   77.88  4834.2   76.19  4844.2   73.75
  4854.2   70.77  4864.2    68.8  4894.2   64.98  4974.2    65.2  4984.2   64.24
  4992.5   61.83    4994   58.83  5005.9   58.83  5007.4   61.83  5026.2   65.98
  5106.2   66.98  5136.2   65.91  5166.2   66.81  5216.2   70.12  5266.2    76.4
  5276.2   77.35  5286.2   79.42  5296.2   82.39  5306.2   83.85    5328   84.36
#Mann= 3 , 1 , 0
  4544.2     .15       0  4992.5    .048       0  5007.4     .15       0
Bank Sta=4992.5,5007.4
XS Rating Curve= 0 ,0
Exp/Cntr=0.3,0.1

Type RM Length L Ch R = 1 ,8058.6  ,547.1,547.1,547.1
BEGIN DESCRIPTION:
Watery Branch 7.0
END DESCRIPTION:
#Sta/Elev= 17
  4653.2   79.96  4683.2   78.84  4783.2   77.81  4793.2   77.94  4823.2   75.97
  4853.2   72.71  4913.2    64.7  4992.6    60.5  4994.1    57.5    5006    57.5
  5007.5    60.5  5053.2   63.98  5063.2   64.38  5073.2   66.28  5123.2   79.28
  5133.2   81.19  5152.7   82.42
#Mann= 3 , 1 , 0
  4653.2     .15       0  4992.6    .048       0  5007.5     .15       0
Bank Sta=4992.6,5007.5
XS Rating Curve= 0 ,0
Exp/Cntr=0.3,0.1

Type RM Length L Ch R = 1 ,7511.5  ,445.6,445.6,445.6
BEGIN DESCRIPTION:
Watery Branch 6.0
END DESCRIPTION:
#Sta/Elev= 25
  4622.8   82.78  4712.8   81.23  4792.8   77.04  4882.8   73.06  4932.8   69.54
  4942.8   68.53  4952.8   66.94  4972.8   64.49  4982.8   64.17  4992.6   60.24
  4994.1   57.24    5006   57.24  5007.5   60.24    5010   61.05    5030   62.52
    5040   62.84    5130   61.84    5230   64.96    5280   65.72    5300    70.8
    5320   77.58    5330   78.97    5370    82.9    5380   83.57  5396.3   83.65
#Mann= 3 , 1 , 0
  4622.8     .15       0  4992.6    .048       0  5007.5     .15       0
Bank Sta=4992.6,5007.5
XS Rating Curve= 0 ,0
Exp/Cntr=0.3,0.1

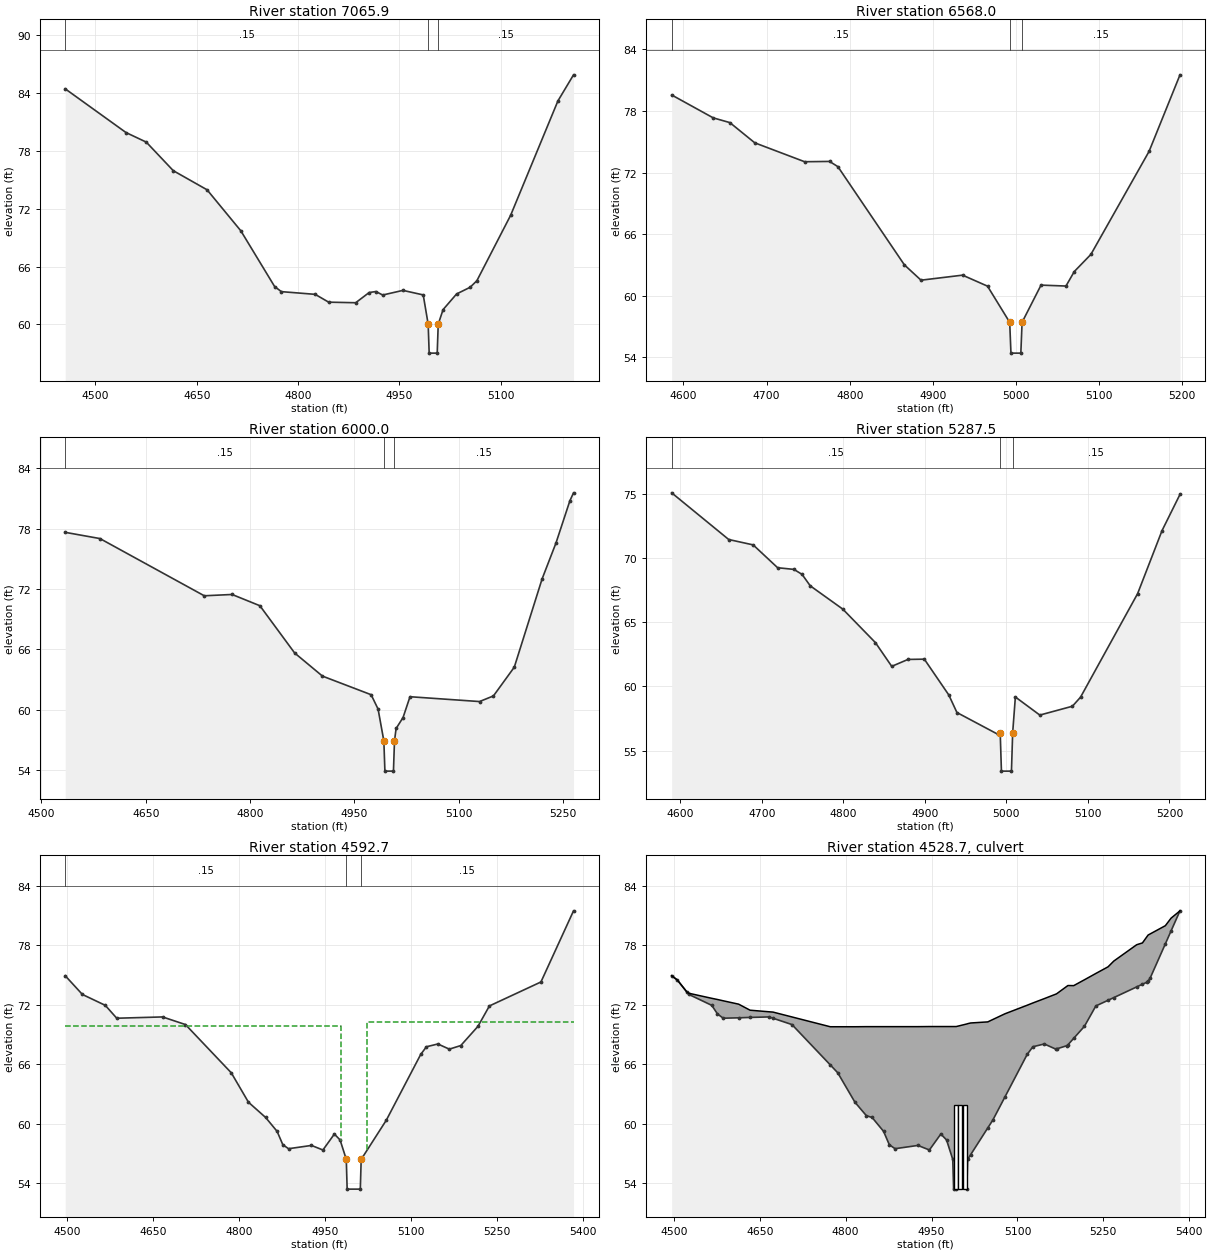
Type RM Length L Ch R = 1 ,7065.9  ,497.9,497.9,497.9
BEGIN DESCRIPTION:
Watery Branch 5.5
END DESCRIPTION:
#Sta/Elev= 27
  4455.2   84.41  4545.2   79.88  4575.2   78.89  4615.2   75.93  4665.2   73.95
  4715.2    69.7  4765.2   63.93  4775.2    63.4  4825.2   63.12  4845.2   62.31
  4885.2   62.25  4905.2   63.31  4915.2   63.41  4925.2   63.05  4955.2   63.53
  4985.2   63.06  4992.5   60.03    4994   57.03  5005.9   57.03  5007.4   60.03
  5014.6   61.54  5034.6   63.16  5054.6   63.85  5064.6   64.53  5114.6   71.31
  5184.6   83.16  5207.7   85.86
#Mann= 3 , 1 , 0
  4455.2     .15       0  4992.5    .048       0  5007.4     .15       0
Bank Sta=4992.5,5007.4
XS Rating Curve= 0 ,0
Exp/Cntr=0.3,0.1

Type RM Length L Ch R = 1 ,6568.0  ,568,568,568
BEGIN DESCRIPTION:
Watery Branch 5.0
END DESCRIPTION:
#Sta/Elev= 21
  4585.8   79.55  4635.8   77.32  4655.8   76.86  4685.8   74.89  4745.8   73.05
  4775.8   73.08  4785.8   72.57  4865.8   63.01  4885.8   61.52  4935.8   62.01
  4965.8   60.94  4992.5   57.42    4994   54.42  5005.9   54.42  5007.4   57.42
  5030.2   61.04  5060.2   60.95  5070.2   62.36  5090.2   64.03  5160.2   74.06
  5197.4   81.51
#Mann= 3 , 1 , 0
  4585.8     .15       0  4992.5    .048       0  5007.4     .15       0
Bank Sta=4992.5,5007.4
XS Rating Curve= 0 ,0
Exp/Cntr=0.3,0.1

Type RM Length L Ch R = 1 ,6000.0  ,712.5,712.5,712.5
BEGIN DESCRIPTION:
Watery Branch 4.0
END DESCRIPTION:
#Sta/Elev= 23
  4534.1   77.65  4584.1   77.03  4734.1   71.34  4774.1   71.47  4814.1   70.35
  4864.1   65.65  4904.1   63.35  4974.1    61.5  4984.1   60.07  4992.4    56.9
  4993.9    53.9  5006.2    53.9  5007.7    56.9    5010   58.14    5020   59.23
    5030    61.3    5130   60.82    5150   61.38    5180   64.24    5220   73.02
    5240    76.6    5260    80.8  5265.2   81.58
#Mann= 3 , 1 , 0
  4534.1     .15       0  4992.4    .048       0  5007.7     .15       0
Bank Sta=4992.4,5007.7
XS Rating Curve= 0 ,0
Exp/Cntr=0.3,0.1

Type RM Length L Ch R = 1 ,5287.5  ,694.8,694.8,694.8
BEGIN DESCRIPTION:
Watery Branch 3.0
END DESCRIPTION:
#Sta/Elev= 26
  4589.3    75.1  4659.3   71.46  4689.3   71.04  4719.3   69.26  4739.3   69.13
  4749.3   68.74  4759.3   67.85  4799.3   66.03  4839.3   63.42  4859.3   61.57
  4879.3   62.11  4899.3   62.13  4929.3   59.34  4939.3   57.97  4989.3   56.28
  4992.4    56.4  4993.9    53.4  5006.2    53.4  5007.7    56.4    5011   59.18
    5041   57.77    5081   58.46    5091   59.17    5161   67.24    5191   72.16
    5213   74.98
#Mann= 3 , 1 , 0
  4589.3     .15       0  4992.4    .048       0  5007.7     .15       0
Bank Sta=4992.4,5007.7
XS Rating Curve= 0 ,0
Exp/Cntr=0.5,0.3

Type RM Length L Ch R = 1 ,4592.7  ,128,128,128
BEGIN DESCRIPTION:
Upstream Section of Bridge/Culvert/Weir
END DESCRIPTION:
#Sta/Elev= 30
  4496.2   74.94  4526.2   73.05  4566.2   71.95  4586.2   70.65  4666.2   70.78
  4706.2   70.01  4786.2   65.14  4816.2   62.17  4846.2   60.63  4866.2   59.23
  4876.2   57.88  4886.2   57.48  4926.2   57.81  4946.2   57.35  4966.2   58.96
  4976.2   58.36    4987    56.4  4988.5    53.4  5011.5    53.4    5013    56.4
  5056.9   60.36  5116.9   66.99  5126.9   67.77  5146.9   68.05  5166.9   67.53
  5186.9   67.89  5216.9   69.83  5236.9   71.89  5326.9   74.31  5383.8   81.49
#Mann= 3 , 1 , 0
  4496.2     .15       0    4987    .048       0    5013     .15       0
#XS Ineff= 2 , 0
       0    4977    69.9    5023       0    70.3
Permanent Ineff=
       F       F
Bank Sta=4987,5013
XS Rating Curve= 0 ,0
Exp/Cntr=0.5,0.3

Type RM Length L Ch R = 2 ,4528.7  ,,,
BEGIN DESCRIPTION:
NC 58-TOR
Structure ID: NC 58
Approximate Survey Structure
END DESCRIPTION:
Bridge Culvert--1,0,-1,-1, 0
Deck Dist Width WeirC Skew NumUp NumDn MinLoCord MaxHiCord MaxSubmerge Is_Ogee
10,108,3,0, 53, 53, , , 0.95, 0, 1,1,,
  4496.2  4506.2  4523.1  4526.2  4566.2  4576.2  4586.2  4613.1  4633.1  4666.2
  4673.1  4706.2  4773.1  4786.2  4816.2  4836.2  4846.2  4866.2  4876.2  4886.2
  4926.2  4946.2  4966.2  4976.2    4987  4988.5  4993.1  5011.5    5013  5018.2
  5048.2  5056.9  5078.2  5116.9  5126.9  5146.9  5166.9  5168.2  5186.9  5188.2
  5198.2  5216.9  5236.9  5258.2  5268.2  5308.2  5318.2  5326.9  5328.2  5331.4
  5358.2  5368.2  5383.8
   74.94    74.5   73.27   73.17   72.66   72.54   72.41   72.07   71.46    71.3
   71.27   70.78   69.79   69.79   69.79    69.8    69.8    69.8    69.8    69.8
    69.8   69.81   69.81   69.81   69.81   69.81   69.81   70.07    70.1   70.17
   70.28   70.52    71.1   71.96   72.19   72.63   73.08   73.11    73.9   73.95
   73.94   74.53   75.17   75.84   76.42   78.07   78.25   78.95   79.05   79.15
   79.99   80.75   81.49
   74.94    74.5   73.27   73.05   71.95   71.08   70.65   70.69   70.73   70.78
   70.65   70.01   65.94   65.14   62.17   60.81   60.63   59.23   57.88   57.48
   57.81   57.35   58.96   58.36    56.4    53.4    53.4    53.4    56.4   56.87
   59.58   60.36   62.71   66.99   67.77   68.05   67.53   67.55   67.89   67.97
   68.62   69.83   71.89   72.46   72.73   73.81   74.08   74.31   74.41   74.66
   78.15   79.46   81.49
  4496.2  4506.2  4523.1  4526.2  4566.2  4576.2  4586.2  4613.1  4633.1  4666.2
  4673.1  4706.2  4773.1  4786.2  4816.2  4836.2  4846.2  4866.2  4876.2  4886.2
  4926.2  4946.2  4966.2  4976.2    4987  4988.5  4993.1  5011.5    5013  5018.2
  5048.2  5056.9  5078.2  5116.9  5126.9  5146.9  5166.9  5168.2  5186.9  5188.2
  5198.2  5216.9  5236.9  5258.2  5268.2  5308.2  5318.2  5326.9  5328.2  5331.4
  5358.2  5368.2  5383.8
   74.79   74.35   73.21   73.17   72.66   72.54   72.41   72.07   71.46    71.3
   71.27   70.78   69.79   69.79   69.79    69.8    69.8    69.8    69.8    69.8
    69.8   69.81   69.81   69.81   69.81   69.81   69.81   70.07    70.1   70.17
   70.28   70.52    71.1   71.96   72.19   72.63   73.08   73.11    73.9   73.95
   73.94   74.53   75.17   75.84   76.42   78.07   78.25   78.95   79.05   79.15
   79.99   80.75   81.34
   74.64    74.2   72.97   72.75   71.65   70.78   70.35   70.39   70.43   70.48
   70.35   69.71   65.64   64.84   61.87   60.51   60.33   58.93   57.58   57.18
   57.51   57.05   58.66   58.06    56.1    53.1    53.1    53.1    56.1   56.57
   59.28   60.06   62.41   66.69   67.47   67.75   67.23   67.25   67.59   67.67
   68.32   69.53   71.59   72.16   72.43   73.51   73.78   74.01   74.11   74.36
   77.85   79.16   81.19
BR Coef= 1 , 0 , 0 ,1.25, 0 ,,,0.8,-1,2,0,
WSPro=,,,, 1 ,,,, 0 ,,,, 0 ,,,,-1 ,-1 ,-1 , 0 , 0 , 0 , 0 , 0
Culvert=2,8.5,7,108,0.015,0.4,1,8,1,53.4,4992.03,53.1,4992.03,Culvert #1  , 0 ,10
Culvert Bottom n=0.015
Culvert=2,8.5,7,108,0.015,0.4,1,8,1,53.4,5000.03,53.1,5000.03,Culvert #2  , 0 ,10
Culvert Bottom n=0.015
Culvert=2,8.5,7,108,0.015,0.4,1,8,1,53.4,5008.03,53.1,5008.03,Culvert #3  , 0 ,10
Culvert Bottom n=0.015
BR U #Sta/Elev= 53
  4496.2   74.94  4506.2    74.5  4523.1   73.27  4526.2   73.05  4566.2   71.95
  4576.2   71.08  4586.2   70.65  4613.1   70.69  4633.1   70.73  4666.2   70.78
  4673.1   70.65  4706.2   70.01  4773.1   65.94  4786.2   65.14  4816.2   62.17
  4836.2   60.81  4846.2   60.63  4866.2   59.23  4876.2   57.88  4886.2   57.48
  4926.2   57.81  4946.2   57.35  4966.2   58.96  4976.2   58.36    4987    56.4
  4988.5    53.4  4993.1    53.4  5011.5    53.4    5013    56.4  5018.2   56.87
  5048.2   59.58  5056.9   60.36  5078.2   62.71  5116.9   66.99  5126.9   67.77
  5146.9   68.05  5166.9   67.53  5168.2   67.55  5186.9   67.89  5188.2   67.97
  5198.2   68.62  5216.9   69.83  5236.9   71.89  5258.2   72.46  5268.2   72.73
  5308.2   73.81  5318.2   74.08  5326.9   74.31  5328.2   74.41  5331.4   74.66
  5358.2   78.15  5368.2   79.46  5383.8   81.49
BR U #Mann= 3
  4496.2     .15    4987    .048    5013     .15
BR U Banks=4987,5013
BR D #Sta/Elev= 53
  4496.2   74.64  4506.2    74.2  4523.1   72.97  4526.2   72.75  4566.2   71.65
  4576.2   70.78  4586.2   70.35  4613.1   70.39  4633.1   70.43  4666.2   70.48
  4673.1   70.35  4706.2   69.71  4773.1   65.64  4786.2   64.84  4816.2   61.87
  4836.2   60.51  4846.2   60.33  4866.2   58.93  4876.2   57.58  4886.2   57.18
  4926.2   57.51  4946.2   57.05  4966.2   58.66  4976.2   58.06    4987    56.1
  4988.5    53.1  4993.1    53.1  5011.5    53.1    5013    56.1  5018.2   56.57
  5048.2   59.28  5056.9   60.06  5078.2   62.41  5116.9   66.69  5126.9   67.47
  5146.9   67.75  5166.9   67.23  5168.2   67.25  5186.9   67.59  5188.2   67.67
  5198.2   68.32  5216.9   69.53  5236.9   71.59  5258.2   72.16  5268.2   72.43
  5308.2   73.51  5318.2   73.78  5326.9   74.01  5328.2   74.11  5331.4   74.36
  5358.2   77.85  5368.2   79.16  5383.8   81.19
BR D #Mann= 3
  4496.2     .15    4987    .048    5013     .15
BR D Banks=4987,5013
BC Design=,, 0 ,, 0 ,,,,,,
BC HTab HWMax=81.49
BC Use User HTab Curves=0
BC User HTab FreeFlow(D)= 0

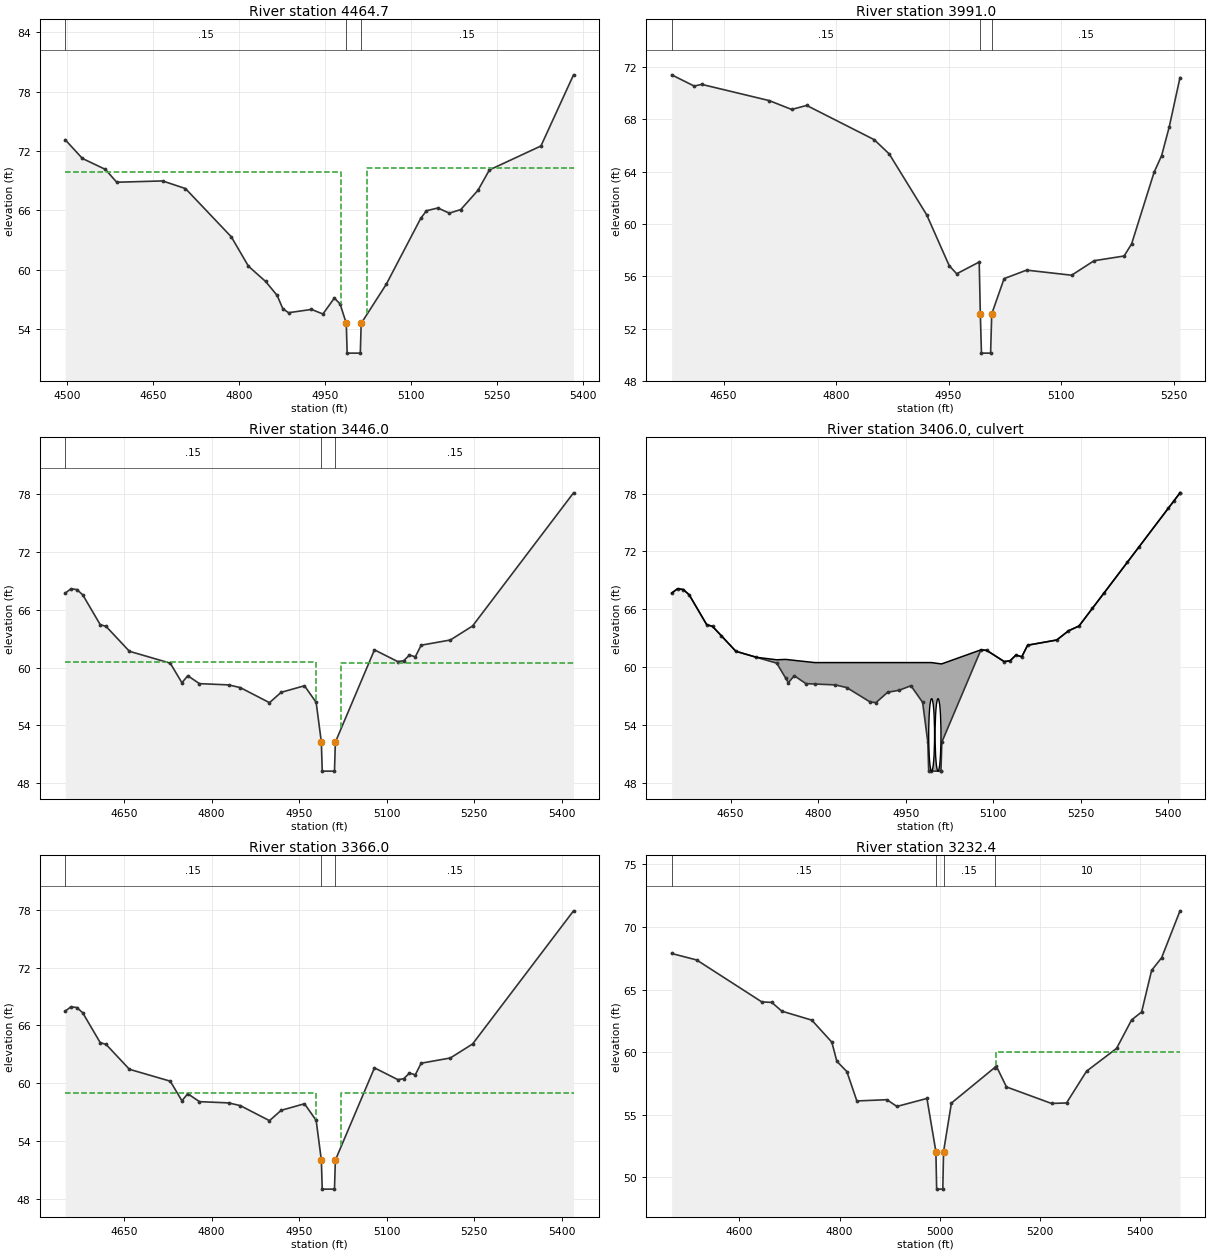
Type RM Length L Ch R = 1 ,4464.7  ,473.7,473.7,473.7
BEGIN DESCRIPTION:
Downstream Section of Bridge/Culvert/Weir
END DESCRIPTION:
#Sta/Elev= 30
  4496.2   73.14  4526.2   71.25  4566.2   70.15  4586.2   68.85  4666.2   68.98
  4706.2   68.21  4786.2   63.34  4816.2   60.37  4846.2   58.83  4866.2   57.43
  4876.2   56.08  4886.2   55.68  4926.2   56.01  4946.2   55.55  4966.2   57.16
  4976.2   56.56    4987    54.6  4988.5    51.6  5011.5    51.6    5013    54.6
  5056.9   58.56  5116.9   65.19  5126.9   65.97  5146.9   66.25  5166.9   65.73
  5186.9   66.09  5216.9   68.03  5236.9   70.09  5326.9   72.51  5383.8   79.69
#Mann= 3 , 1 , 0
  4496.2     .15       0    4987    .048       0    5013     .15       0
#XS Ineff= 2 , 0
       0    4977    69.9    5023       0    70.3
Permanent Ineff=
       F       F
Bank Sta=4987,5013
XS Rating Curve= 0 ,0
Exp/Cntr=0.5,0.3

Type RM Length L Ch R = 1 ,3991.0  ,545,545,545
BEGIN DESCRIPTION:
Watery Branch 2.0
END DESCRIPTION:
#Sta/Elev= 26
  4580.9   71.41  4610.9   70.55  4620.9   70.68  4710.9   69.44  4740.9   68.76
  4760.9   69.07  4850.9   66.45  4870.9   65.36  4920.9    60.7  4950.9   56.81
  4960.9   56.19  4990.9   57.09  4992.4   53.12  4993.9   50.12  5006.1   50.12
  5007.6   53.12  5024.1   55.82  5054.1   56.47  5114.1   56.08  5144.1   57.19
  5184.1   57.55  5194.1   58.48  5224.1   63.96  5234.1   65.23  5244.1   67.39
  5258.6    71.2
#Mann= 3 , 1 , 0
  4580.9     .15       0  4992.4    .048       0  5007.6     .15       0
Bank Sta=4992.4,5007.6
XS Rating Curve= 0 ,0
Exp/Cntr=0.5,0.3

Type RM Length L Ch R = 1 ,3446.0  ,80,80,80
BEGIN DESCRIPTION:
Upstream Section of Bridge/Culvert/Weir
END DESCRIPTION:
#Sta/Elev= 30
  4549.1    67.7  4559.1   68.16  4569.1   68.07  4579.1   67.53  4609.1   64.44
  4619.1   64.26  4659.1   61.68  4729.1   60.45  4749.1   58.42  4759.1   59.15
  4779.1   58.33  4829.1    58.2  4849.1   57.92  4899.1   56.36  4919.1   57.43
  4959.1   58.11  4979.1   56.39    4988   52.27  4989.5   49.27  5010.5   49.27
    5012   52.27    5079   61.83    5119   60.61    5129    60.7    5139   61.29
    5149   61.11    5159   62.31    5209   62.85  5247.1    64.3  5420.1   78.09
#Mann= 3 , 1 , 0
  4549.1     .15       0    4988    .048       0    5012     .15       0
#XS Ineff= 2 , 0
       0    4978    60.6    5022       0    60.5
Permanent Ineff=
       F       F
Bank Sta=4988,5012
XS Rating Curve= 0 ,0
Exp/Cntr=0.5,0.3

Type RM Length L Ch R = 2 ,3406.0  ,,,
BEGIN DESCRIPTION:
Unnamed Rd-TOR
Structure ID: WB - Unnamed Rd
Approximate Survey Structure
END DESCRIPTION:
Bridge Culvert--1,0,-1,-1, 0
Deck Dist Width WeirC Skew NumUp NumDn MinLoCord MaxHiCord MaxSubmerge Is_Ogee
10,60,3,0, 47, 47, , , 0.95, 0, 1,1,,
  4549.1  4559.1  4569.1  4579.1  4609.1  4619.1  4634.2  4659.1  4694.2  4729.1
  4744.2  4749.1  4759.1  4779.1  4794.2  4829.1  4849.1  4889.1  4899.1  4919.1
  4939.1  4959.1  4979.1    4988  4989.5  4994.2    5010  5010.5    5012    5079
    5089    5119    5129    5139    5149    5159    5209    5229  5247.1    5270
    5290    5330    5350    5400    5410    5420  5420.1
   67.68   68.14   68.05   67.51   64.42   64.24   63.27   61.66   61.04   60.78
   60.82   60.79   60.72   60.59   60.49   60.49   60.49   60.49   60.49   60.49
   60.49   60.49   60.49   60.49   60.49   60.49   60.36   60.36   60.36   61.81
   61.75   60.59   60.68   61.27   61.09   62.29   62.83   63.78   64.28   66.11
    67.7   70.89   72.48   76.47   77.26   78.06   78.07
   67.68   68.14   68.05   67.51   64.42   64.24   63.27   61.66   61.04   60.43
    58.9    58.4   59.13   58.31   58.27   58.18    57.9   56.41   56.34   57.41
   57.63   58.09   56.37   52.25   49.25   49.25   49.25   49.25   52.25   61.81
   61.75   60.59   60.68   61.27   61.09   62.29   62.83   63.78   64.28   66.11
    67.7   70.89   72.48   76.47   77.26   78.06   78.07
  4549.1  4559.1  4569.1  4579.1  4609.1  4619.1  4634.2  4659.1  4694.2  4729.1
  4744.2  4749.1  4759.1  4779.1  4794.2  4829.1  4849.1  4889.1  4899.1  4919.1
  4939.1  4959.1  4979.1    4988  4989.5  4994.2    5010  5010.5    5012    5079
    5089    5119    5129    5139    5149    5159    5209    5229  5247.1    5270
    5290    5330    5350    5400    5410    5420  5420.1
   67.58   68.04   67.95   67.41   64.32   64.14   63.18   61.57   60.95   60.78
   60.82   60.79   60.72   60.59   60.49   60.49   60.49   60.49   60.49   60.49
   60.49   60.49   60.49   60.49   60.49   60.49   60.36   60.36   60.36   61.72
   61.66    60.5   60.59   61.18      61    62.2   62.74   63.69   64.19   66.02
   67.61    70.8   72.39   76.38   77.17   77.96   77.97
   67.48   67.94   67.85   67.31   64.22   64.04   63.07   61.46   60.84   60.23
    58.7    58.2   58.93   58.11   58.07   57.98    57.7   56.21   56.14   57.21
   57.43   57.89   56.17   52.05   49.05   49.05   49.05   49.05   52.05   61.61
   61.55   60.39   60.48   61.07   60.89   62.09   62.63   63.58   64.08   65.91
    67.5   70.69   72.28   76.27   77.06   77.86   77.87
BR Coef= 1 , 0 , 0 ,1.25, 0 ,,,0.8,-1,2,0,
WSPro=,,,, 1 ,,,, 0 ,,,, 0 ,,,,-1 ,-1 ,-1 , 0 , 0 , 0 , 0 , 0
Culvert=3,7.5,10,60,0.024,0.9,1,34,3,49.25,4994.52,49.05,4994.52,Culvert #1  , 0 ,10
Culvert Bottom n=0.024
Culvert=3,7.5,10,60,0.024,0.9,1,34,3,49.25,5005.52,49.05,5005.52,Culvert #2  , 0 ,10
Culvert Bottom n=0.024
BR U #Sta/Elev= 47
  4549.1   67.68  4559.1   68.14  4569.1   68.05  4579.1   67.51  4609.1   64.42
  4619.1   64.24  4634.2   63.27  4659.1   61.66  4694.2   61.04  4729.1   60.43
  4744.2    58.9  4749.1    58.4  4759.1   59.13  4779.1   58.31  4794.2   58.27
  4829.1   58.18  4849.1    57.9  4889.1   56.41  4899.1   56.34  4919.1   57.41
  4939.1   57.63  4959.1   58.09  4979.1   56.37    4988   52.25  4989.5   49.25
  4994.2   49.25    5010   49.25  5010.5   49.25    5012   52.25    5079   61.81
    5089   61.75    5119   60.59    5129   60.68    5139   61.27    5149   61.09
    5159   62.29    5209   62.83    5229   63.78  5247.1   64.28    5270   66.11
    5290    67.7    5330   70.89    5350   72.48    5400   76.47    5410   77.26
    5420   78.06  5420.1   78.07
BR U #Mann= 3
  4549.1     .15    4988    .048    5012     .15
BR U Banks=4988,5012
BR D #Sta/Elev= 47
  4549.1   67.48  4559.1   67.94  4569.1   67.85  4579.1   67.31  4609.1   64.22
  4619.1   64.04  4634.2   63.07  4659.1   61.46  4694.2   60.84  4729.1   60.23
  4744.2    58.7  4749.1    58.2  4759.1   58.93  4779.1   58.11  4794.2   58.07
  4829.1   57.98  4849.1    57.7  4889.1   56.21  4899.1   56.14  4919.1   57.21
  4939.1   57.43  4959.1   57.89  4979.1   56.17    4988   52.05  4989.5   49.05
  4994.2   49.05    5010   49.05  5010.5   49.05    5012   52.05    5079   61.61
    5089   61.55    5119   60.39    5129   60.48    5139   61.07    5149   60.89
    5159   62.09    5209   62.63    5229   63.58  5247.1   64.08    5270   65.91
    5290    67.5    5330   70.69    5350   72.28    5400   76.27    5410   77.06
    5420   77.86  5420.1   77.87
BR D #Mann= 3
  4549.1     .15    4988    .048    5012     .15
BR D Banks=4988,5012
BC Design=,, 0 ,, 0 ,,,,,,
BC HTab HWMax=78.09
BC Use User HTab Curves=0
BC User HTab FreeFlow(D)= 0

Type RM Length L Ch R = 1 ,3366.0  ,133.6,133.6,133.6
BEGIN DESCRIPTION:
Downstream Section of Bridge/Culvert/Weir
END DESCRIPTION:
#Sta/Elev= 30
  4549.1   67.48  4559.1   67.94  4569.1   67.85  4579.1   67.31  4609.1   64.22
  4619.1   64.04  4659.1   61.46  4729.1   60.23  4749.1    58.2  4759.1   58.93
  4779.1   58.11  4829.1   57.98  4849.1    57.7  4899.1   56.14  4919.1   57.21
  4959.1   57.89  4979.1   56.17    4988   52.05  4989.5   49.05  5010.5   49.05
    5012   52.05    5079   61.61    5119   60.39    5129   60.48    5139   61.07
    5149   60.89    5159   62.09    5209   62.63  5247.1   64.08  5420.1   77.87
#Mann= 3 ,-1 , 0
  4549.1     .15       0    4988    .048       0    5012     .15       0
#XS Ineff= 2 , 0
       0    4978      59    5022       0      59
Permanent Ineff=
       F       F
Bank Sta=4988,5012
XS Rating Curve= 0 ,0
Exp/Cntr=0.5,0.3

Type RM Length L Ch R = 1 ,3232.4  ,0,0,0
BEGIN DESCRIPTION:
Watery Branch 1.0
END DESCRIPTION:
#Sta/Elev= 30
  4464.5   67.88  4514.5   67.36  4644.5   64.01  4664.5   63.97  4684.5   63.27
  4744.5   62.55  4784.5   60.79  4794.5   59.26  4814.5   58.44  4834.5   56.09
  4894.5   56.19  4914.5   55.65  4974.5   56.29  4992.4   52.04  4993.9   49.04
  5006.2   49.04  5007.7   52.04  5023.4   55.92  5109.9   58.76  5113.4   58.85
  5133.4   57.21  5223.4   55.89  5253.4   55.93  5293.4   58.47  5353.4   60.29
  5383.4   62.57  5403.4    63.2  5423.4   66.53  5443.4   67.54  5480.1   71.29
#Mann= 4 ,-1 , 0
  4464.5     .15       0  4992.4    .048       0  5007.7     .15       0
  5109.9      10       0
#XS Ineff= 2 , 0
       0                  5113.4       0      60
Permanent Ineff=
       F       F
Bank Sta=4992.4,5007.7
XS Rating Curve= 0 ,0
Exp/Cntr=0.3,0.1

Chan Stop Cuts=-1
Use User Specified Reach Order=0