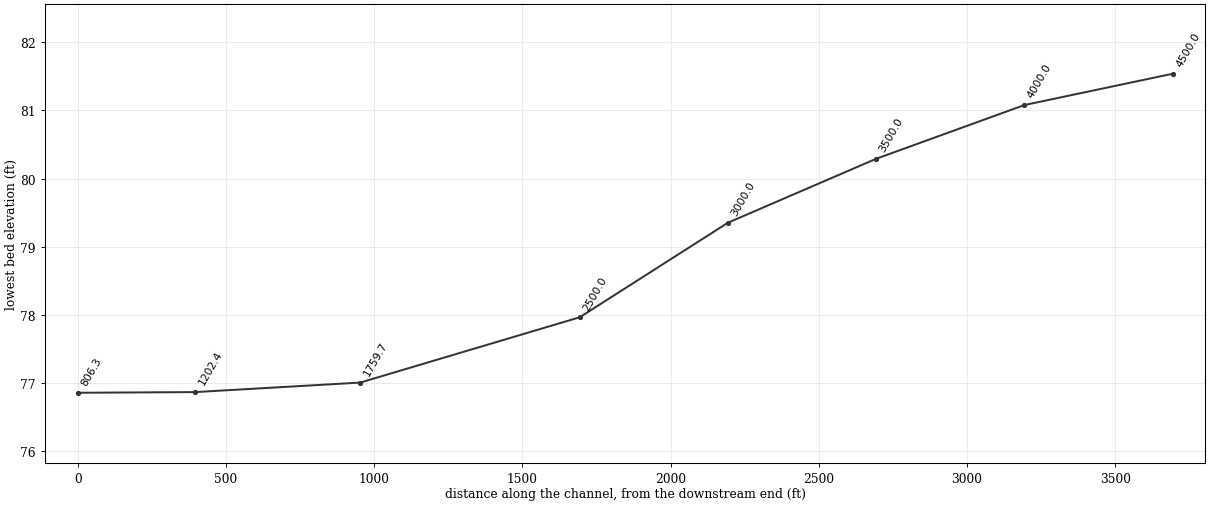
--- 020522_trib_to_white_swamp.prj (project) ---

Proj Title=Trib to White Swamp
Current Plan=p02
Default Exp/Contr=0.3,0.1
English Units
Geom File=g01
Flow File=f01
Flow File=f02
Plan File=p01
Plan File=p02
Y Axis Title=Elevation
X Axis Title(PF)=Main Channel Distance
X Axis Title(XS)=Station
BEGIN DESCRIPTION:
NCFPM-Tar Pam Basin
END DESCRIPTION:
DSS Export Rating Curves= 0
DSS Export Rating Curve Sorted= 0
DSS Export Volume Flow Curves= 0
DXF OffsetX= 0
DXF OffsetY= 0
DXF ScaleX= 1
DXF ScaleY= 10

--- 020522_trib_to_white_swamp.p02 (plan) ---

Plan Title=Multi_Profile
Program Version=4.00
Short Identifier=Multi_Profile
Geom File=g01
Flow File=f02
Subcritical Flow
K Sum by GR= 0
Std Step Tol= 0.01
Critical Tol= 0.01
Num of Std Step Trials= 20
Max Error Tol= 0.3
Flow Tol Ratio= 0.001
Split Flow NTrial= 30
Split Flow Tol= 0.02
Split Flow Ratio= 0.02
Log Output Level= 0
Friction Slope Method= 1
Unsteady Friction Slope Method= 2
Unsteady Bridges Friction Slope Method= 1
Parabolic Critical Depth
Global Vel Dist= 0 , 0 , 0
Global Log Level= 0
CheckData=True
Encroach Param=-1 ,0,0, 2
Computation Interval=1HOUR
Output Interval=1HOUR
Run HTab= 0
Run UNet= 0
Run PostProcess= 0
Run WQNet= 0
UNET Theta= 1
UNET Theta Warmup= 1
UNET ZTol= 0.02
UNET ZSATol= 0.1
UNET MxIter= 20
UNET MaxInSteps= 20
UNET DtIC= 0
UNET DtMin= 0
UNET MaxCRTS= 20
UNET WFStab= 2
UNET SFStab= 1
UNET WFX= 1
UNET SFX= 1
UNET DSS MLevel= 4
UNET DZMax Abort= 100
UNET Convert EG Bridges=-1
UNET Use Existing IB Tables=-1
UNET Froude Reduction=False
UNET Froude Limit= 1
UNET Froude Power= 10
UNET Time Slicing=0,0, 5
Instantaneous Interval=1HOUR
Write IC File= 0
Echo Input=False
Echo Output=False
Write Detailed= 0
Detailed Automatic Start=False, 10
WQ ULTIMATE=-1
WQ Max Comp Step=1HOUR
WQ Output Interval=15MIN
WQ Output Selected Increments= 0
WQ Output face flow=0
WQ Output face velocity=0
WQ Output face area=0
WQ Output face dispersion=0
WQ Output cell volume=0
WQ Output cell surface area=0
WQ Output cell continuity=0
WQ Output face conc=0
WQ Output face dconc_dx=0
WQ Output face courant=0
WQ Output face peclet=0
WQ Output face adv mass=0
WQ Output face disp mass=0
WQ Output cell mass=0
WQ Output cell source sink temp=0
WQ Output cell source sink nsm=0
WQ Output MaxMinRange=-1
WQ Daily Max Min Mean=-1
WQ Daily Range=0
WQ Daily Time=0
WQ Create Restart=0
WQ Fixed Restart=0
WQ System Summary=False
Sorting and Armoring Iterations= 10
XS Update Threshold= 0.02
Hydraulics Update Threshold= 0.02
Energy Slope Method= 1
Volume Change Method= 0
XS Weighting Method= 0
Number of US Weighted Cross Sections= 1
Number of DS Weighted Cross Sections= 1
Upstream XS Weight=0.25
Main XS Weight=0.5
Downstream XS Weight=0.25
Number of DS XS's Weighted with US Boundary= 1
Upstream Boundary Weight= 1
Weight of XSs Associated with US Boundary= 0
Number of US XS's Weighted with DS Boundary= 1
Downstream Boundary Weight= 0.5
Weight of XSs Associated with DS Boundary= 0.5
Sediment Output Level= 4
Mass or Volume Output= 0
Output Increment Type= 1
Profile and TS Output Increment= 10
XS Output Flag= 0
XS Output Increment= 10
Disregard all LS=0
Disregard all Conn=0
Disregard all Breaches=0
Disregard all Pumps=0

--- 020522_trib_to_white_swamp.p01 (plan) ---

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Plan Title=Trib to White Swamp
Version=Version 3.0.1  Mar 2001
Short Identifier=Base Plan
Geom File=g01
Flow File=f01
Encroach River=Main Stem
Encroach Reach=Reach - 1
Encroach Node=4500.0
       4      .7
Encroach Node=4000.0
       4      .7
Encroach Node=3500.0
       4      .7
Encroach Node=3000.0
       4      .7
Encroach Node=2500.0
       4      .7
Encroach Node=1759.7
       4      .7
Encroach Node=1202.4
       4      .7
Encroach Node=806.3
       4      .7
Write Velocity= 0

--- 020522_trib_to_white_swamp.f02 (steady flow) ---

Flow Title=Multi_Profile
Program Version=4.00
Number of Profiles= 7
Profile Names=10yr,25yr,50yr,500yr,100yr-10%,100yr-20%,100yr-35%
River Rch & RM=Main Stem,Reach - 1       ,4500.0
     402     584     750    1503    1626    2084    2546
Boundary for River Rch & Prof#=Main Stem,Reach - 1       , 1
Up Type= 0
Dn Type= 3
Dn Slope=0.0008
Boundary for River Rch & Prof#=Main Stem,Reach - 1       , 2
Up Type= 0
Dn Type= 3
Dn Slope=0.0008
Boundary for River Rch & Prof#=Main Stem,Reach - 1       , 3
Up Type= 0
Dn Type= 3
Dn Slope=0.0008
Boundary for River Rch & Prof#=Main Stem,Reach - 1       , 4
Up Type= 0
Dn Type= 3
Dn Slope=0.0008
Boundary for River Rch & Prof#=Main Stem,Reach - 1       , 5
Up Type= 0
Dn Type= 3
Dn Slope=0.0008
Boundary for River Rch & Prof#=Main Stem,Reach - 1       , 6
Up Type= 0
Dn Type= 3
Dn Slope=0.0008
Boundary for River Rch & Prof#=Main Stem,Reach - 1       , 7
Up Type= 0
Dn Type= 3
Dn Slope=0.0008
DSS Import GetInterval= 0
DSS Import GetPeak= 0
DSS Import FillOption= 0

--- 020522_trib_to_white_swamp.f01 (steady flow) ---

Flow Title=Trib to White Swamp
Version=Version 3.0.1  Mar 2001
Number of Profiles= 2
Profile Names=100-YEAR,AFW
River Rch & RM=Main Stem,Reach - 1       ,4500.0
     941     941
Boundary for River Rch & Prof#=Main Stem,Reach - 1       , 1
Up Type= 0
Dn Type= 3
Dn Slope=.0008
DSS Import GetInterval= 0
DSS Import GetPeak= 0
DSS Import FillOption= 0

--- 020522_trib_to_white_swamp.g01 (geometry) ---

Geom Title=Geom 01 by CodeH2 for Windows

River Reach=Main Stem,Reach - 1
Reach XY= 2
              .5             .95              .5             .05

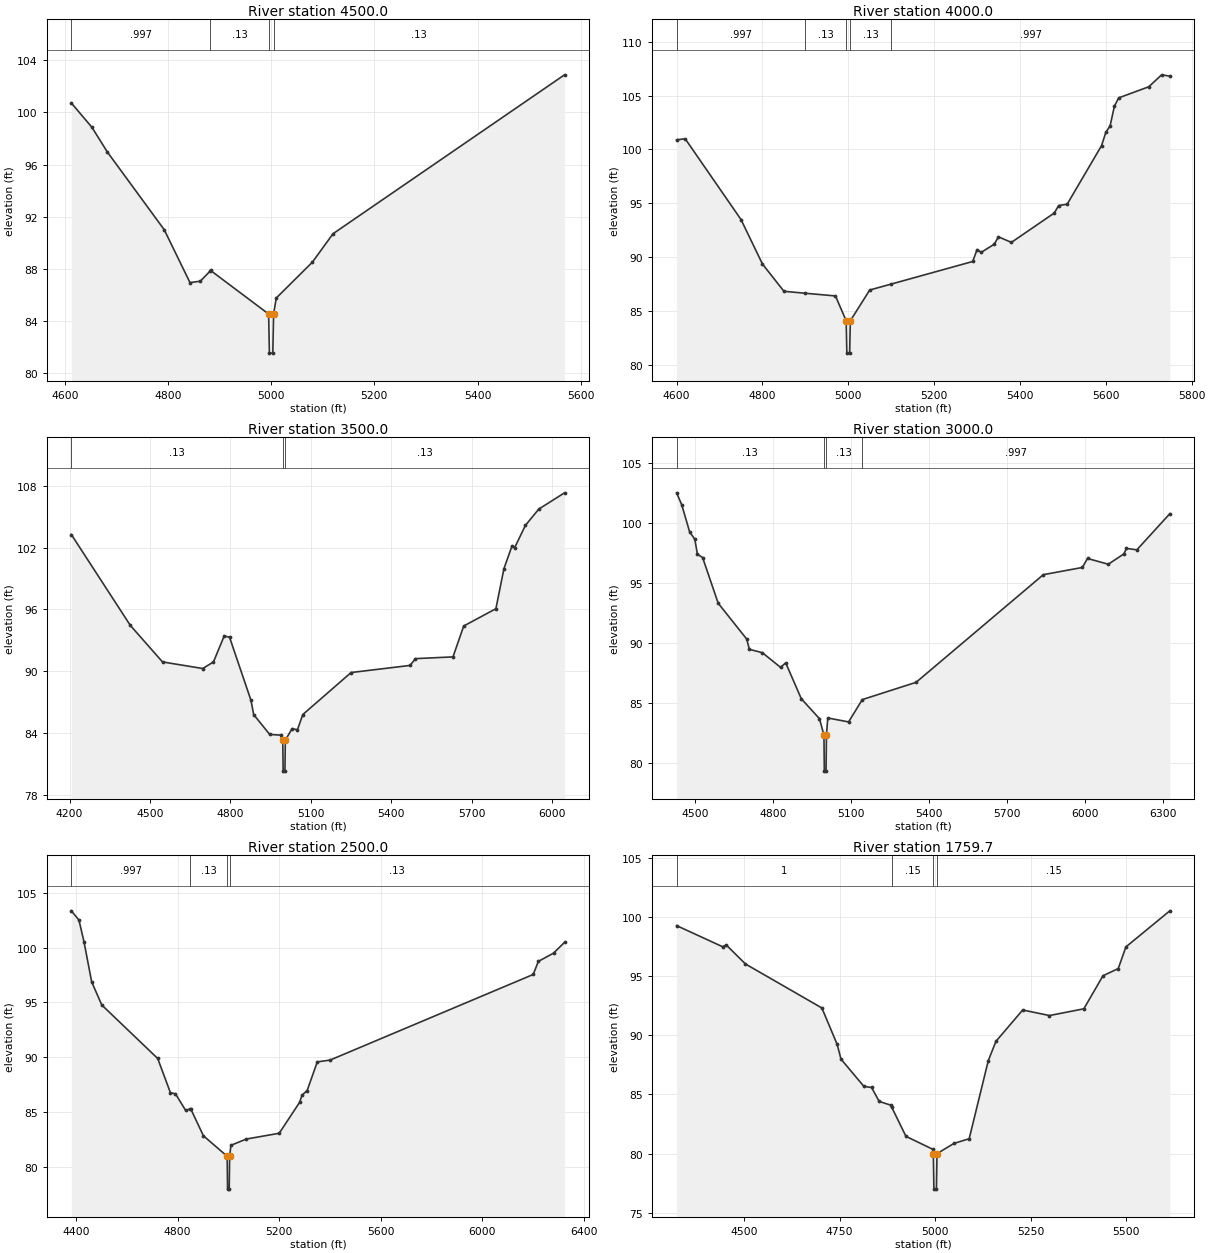
Type RM Length L Ch R = 1 ,4500.0,500,500,500
BEGIN DESCRIPTION:
Trib to White Swamp 9.0
END DESCRIPTION:
#Sta/Elev= 16
  4612.8  100.73  4652.8   98.86  4682.8   96.96  4792.8   91.01  4842.8   86.95
  4862.8   87.06  4881.9   87.84  4882.8   87.88  4995.2   84.54  4996.7   81.54
  5003.3   81.54  5004.8   84.54    5010   85.77    5080   88.52    5120    90.7
  5568.6  102.89
#Mann= 4 , 1 , 0
 4612.80   0.997       0  4881.9    0.13       0  4995.2   0.043       0
  5004.8    0.13       0
Bank Sta=4995.20,5004.80
Exp/Cntr=0.3,0.1

Type RM Length L Ch R = 1 ,4000.0,500,500,500
BEGIN DESCRIPTION:
Trib to White Swamp 8.0
END DESCRIPTION:
#Sta/Elev= 30
  4600.2  100.89  4620.2  100.98  4750.2   93.48  4800.2   89.35  4850.2   86.82
  4899.9   86.64  4970.2   86.39  4995.2   84.08  4996.7   81.08  5003.3   81.08
  5004.8   84.08    5050   86.94  5099.9   87.49    5290   89.59    5300   90.69
    5310   90.44    5340   91.19    5350   91.88    5380   91.36    5480   94.09
    5490   94.78    5510   94.91    5590  100.34    5600  101.57    5610  102.18
    5620  104.01    5630  104.78    5700  105.81    5730  106.92  5749.1   106.8
#Mann= 5 , 1 , 0
 4600.20   0.997       0  4899.9    0.13       0  4995.2   0.043       0
  5004.8    0.13       0  5099.9   0.997       0
Bank Sta=4995.20,5004.80
Exp/Cntr=0.3,0.1

Type RM Length L Ch R = 1 ,3500.0,500,500,500
BEGIN DESCRIPTION:
Trib to White Swamp 7.0
END DESCRIPTION:
#Sta/Elev= 30
  4206.8  103.28  4426.8   94.45  4546.8    90.9  4696.8   90.26  4736.8    90.9
  4776.8   93.42  4796.8    93.3  4876.8   87.16  4886.8   85.78  4946.8   83.85
  4986.8   83.79  4995.2   83.29  4996.7   80.29  5003.3   80.29  5004.8   83.29
    5030   84.42    5050   84.31    5070   85.79    5250   89.87    5470   90.56
    5490   91.22    5630   91.39    5670   94.39    5790   96.07    5820   99.96
    5850  102.17    5860     102    5900  104.17    5950  105.75  6045.8  107.33
#Mann= 3 , 1 , 0
 4206.80    0.13       0  4995.2   0.043       0  5004.8    0.13       0
Bank Sta=4995.20,5004.80
Exp/Cntr=0.3,0.1

Type RM Length L Ch R = 1 ,3000.0,500,500,500
BEGIN DESCRIPTION:
Trib to White Swamp 6.0
END DESCRIPTION:
#Sta/Elev= 30
    4428  102.54    4448  101.52    4478   99.29    4498   98.67    4508   97.42
    4528   97.15    4588   93.34    4698   90.35    4708    89.5    4758   89.22
    4828      88    4848   88.37    4908   85.38    4978   83.72  4995.2   82.35
  4996.7   79.35  5003.3   79.35  5004.8   82.35    5010   83.78    5090   83.45
  5142.9   85.31    5350   86.75    5840   95.72    5990   96.32    6010   97.07
    6090   96.59    6150   97.45    6160   97.91    6200   97.79  6326.9   100.8
#Mann= 4 , 1 , 0
 4428.00    0.13       0  4995.2   0.043       0  5004.8    0.13       0
  5142.9   0.997       0
Bank Sta=4995.20,5004.80
Exp/Cntr=0.3,0.1

Type RM Length L Ch R = 1 ,2500.0,740.3,740.3,740.3
BEGIN DESCRIPTION:
Trib to White Swamp 5.0
END DESCRIPTION:
#Sta/Elev= 28
  4381.7  103.37  4411.7  102.53  4431.7  100.53  4461.7   96.89  4501.7   94.77
  4721.7   89.89  4771.7   86.77  4791.7   86.66  4831.7   85.15  4849.9   85.28
  4851.7   85.29  4901.7   82.83  4995.2   80.96  4996.7   77.96  5003.3   77.96
  5004.8   80.96    5010   81.96    5070   82.53    5200   83.06    5280   85.87
    5290   86.54    5310   86.96    5350   89.58    5400   89.74    6200   97.56
    6220   98.75    6280   99.51  6323.1  100.49
#Mann= 4 , 1 , 0
 4381.70   0.997       0  4849.9    0.13       0  4995.2   0.043       0
  5004.8    0.13       0
Bank Sta=4995.20,5004.80
Exp/Cntr=0.3,0.1

Type RM Length L Ch R = 1 ,1759.7,557.3,557.3,557.3
BEGIN DESCRIPTION:
Trib to White Swamp 4.0
END DESCRIPTION:
#Sta/Elev= 29
  4323.6   99.27  4443.6   97.49  4453.6   97.63  4503.6   96.03  4703.6   92.31
  4743.6   89.23  4753.6   87.99  4813.6   85.68  4833.6   85.59  4853.6   84.41
  4883.6    84.1  4885.9   83.95  4923.6   81.46  4993.6   80.37  4995.2      80
  4996.7      77  5003.3      77  5004.8      80    5049   80.86    5089   81.26
    5139   87.86    5159   89.49    5229   92.14    5299   91.67    5389   92.24
    5439   95.03    5479   95.64    5499   97.47  5613.9  100.52
#Mann= 4 , 1 , 0
 4323.60       1       0  4885.9    0.15       0  4995.2   0.044       0
  5004.8    0.15       0
Bank Sta=4995.20,5004.80
Exp/Cntr=0.3,0.1

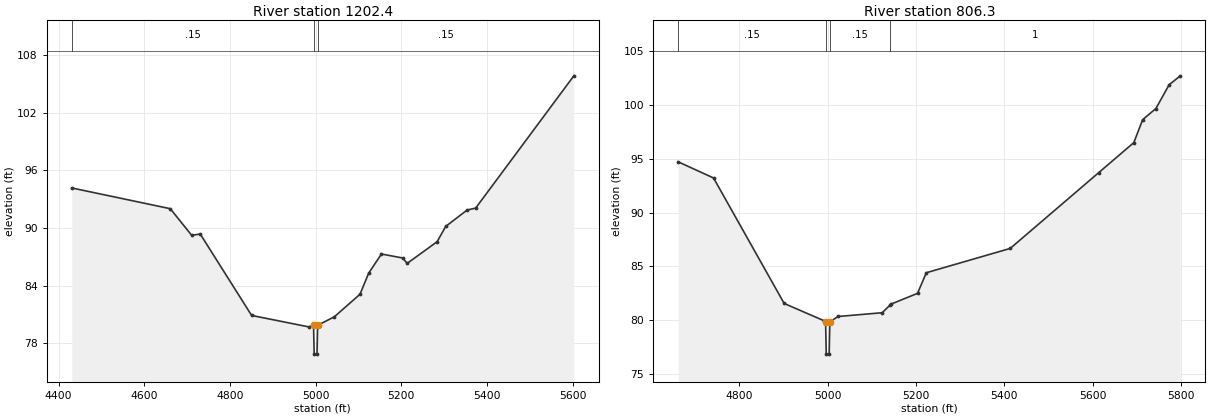
Type RM Length L Ch R = 1 ,1202.4,396.1,396.1,396.1
BEGIN DESCRIPTION:
Trib to White Swamp 2.0
END DESCRIPTION:
#Sta/Elev= 22
  4430.6   94.17  4660.6   92.01  4710.6   89.24  4730.6   89.37  4850.6   80.89
  4983.8    79.7  4993.8    79.8  4995.2   79.86  4996.7   76.86  5003.3   76.86
  5004.8   79.86  5043.8   80.75  5103.8    83.1  5123.8   85.28  5153.8   87.29
  5203.8   86.87  5213.8   86.31  5283.8   88.57  5303.8   90.16  5353.8   91.87
  5373.8   92.07  5603.1  105.85
#Mann= 3 , 1 , 0
 4430.60    0.15       0  4995.2   0.044       0  5004.8    0.15       0
Bank Sta=4995.20,5004.80
Exp/Cntr=0.3,0.1

Type RM Length L Ch R = 1 ,806.3,0,0,0
BEGIN DESCRIPTION:
Trib to White Swamp 1.0
END DESCRIPTION:
#Sta/Elev= 21
  4661.4   94.73  4741.4   93.23  4901.4   81.56  4991.4   79.96  4995.2   79.85
  4996.7   76.85  5003.3   76.85  5004.8   79.85  5023.4   80.35  5123.4    80.7
  5141.9   81.44  5143.4    81.5  5203.4    82.5  5223.4   84.42  5413.4   86.68
  5613.4   93.71  5693.4   96.52  5713.4   98.65  5743.4   99.69  5773.4   101.9
  5798.7  102.73
#Mann= 4 , 1 , 0
 4661.40    0.15       0  4995.2   0.044       0  5004.8    0.15       0
  5141.9       1       0
Bank Sta=4995.20,5004.80
Exp/Cntr=0.3,0.1

Chan Stop Cuts=-1