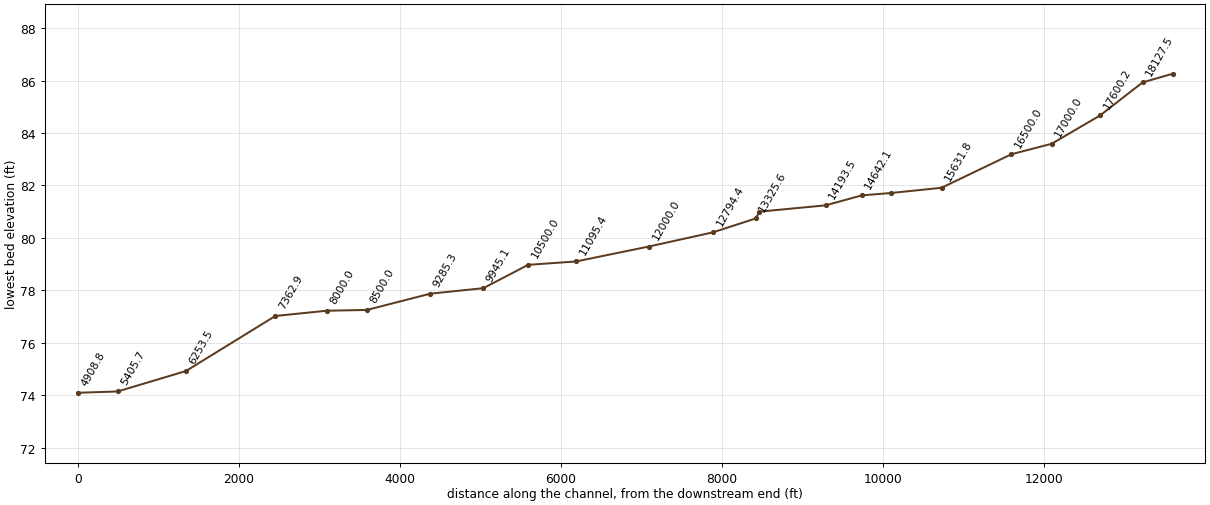
--- 020522_white_swamp.prj (project) ---

Proj Title=White Swamp
Current Plan=p02
Default Exp/Contr=0.3,0.1
English Units
Geom File=g01
Flow File=f01
Flow File=f02
Plan File=p01
Plan File=p02
Y Axis Title=Elevation
X Axis Title(PF)=Main Channel Distance
X Axis Title(XS)=Station
BEGIN DESCRIPTION:
NCFPM-Tar Pam Basin
END DESCRIPTION:
DSS Export Rating Curves= 0
DSS Export Rating Curve Sorted= 0
DSS Export Volume Flow Curves= 0
DXF OffsetX= 0
DXF OffsetY= 0
DXF ScaleX= 1
DXF ScaleY= 10

--- 020522_white_swamp.p02 (plan) ---

Plan Title=Multi_Profile
Program Version=4.00
Short Identifier=Multi_Profile
Geom File=g01
Flow File=f02
Subcritical Flow
K Sum by GR= 0
Std Step Tol= 0.01
Critical Tol= 0.01
Num of Std Step Trials= 20
Max Error Tol= 0.3
Flow Tol Ratio= 0.001
Split Flow NTrial= 30
Split Flow Tol= 0.02
Split Flow Ratio= 0.02
Log Output Level= 0
Friction Slope Method= 1
Unsteady Friction Slope Method= 2
Unsteady Bridges Friction Slope Method= 1
Parabolic Critical Depth
Global Vel Dist= 0 , 0 , 0
Global Log Level= 0
CheckData=True
Encroach Param=-1 ,0,0, 2
Computation Interval=1HOUR
Output Interval=1HOUR
Run HTab= 0
Run UNet= 0
Run PostProcess= 0
Run WQNet= 0
UNET Theta= 1
UNET Theta Warmup= 1
UNET ZTol= 0.02
UNET ZSATol= 0.1
UNET MxIter= 20
UNET MaxInSteps= 20
UNET DtIC= 0
UNET DtMin= 0
UNET MaxCRTS= 20
UNET WFStab= 2
UNET SFStab= 1
UNET WFX= 1
UNET SFX= 1
UNET DSS MLevel= 4
UNET DZMax Abort= 100
UNET Convert EG Bridges=-1
UNET Use Existing IB Tables=-1
UNET Froude Reduction=False
UNET Froude Limit= 1
UNET Froude Power= 10
UNET Time Slicing=0,0, 5
Instantaneous Interval=1HOUR
Write IC File= 0
Echo Input=False
Echo Output=False
Write Detailed= 0
Detailed Automatic Start=False, 10
WQ ULTIMATE=-1
WQ Max Comp Step=1HOUR
WQ Output Interval=15MIN
WQ Output Selected Increments= 0
WQ Output face flow=0
WQ Output face velocity=0
WQ Output face area=0
WQ Output face dispersion=0
WQ Output cell volume=0
WQ Output cell surface area=0
WQ Output cell continuity=0
WQ Output face conc=0
WQ Output face dconc_dx=0
WQ Output face courant=0
WQ Output face peclet=0
WQ Output face adv mass=0
WQ Output face disp mass=0
WQ Output cell mass=0
WQ Output cell source sink temp=0
WQ Output cell source sink nsm=0
WQ Output MaxMinRange=-1
WQ Daily Max Min Mean=-1
WQ Daily Range=0
WQ Daily Time=0
WQ Create Restart=0
WQ Fixed Restart=0
WQ System Summary=False
Sorting and Armoring Iterations= 10
XS Update Threshold= 0.02
Hydraulics Update Threshold= 0.02
Energy Slope Method= 1
Volume Change Method= 0
XS Weighting Method= 0
Number of US Weighted Cross Sections= 1
Number of DS Weighted Cross Sections= 1
Upstream XS Weight=0.25
Main XS Weight=0.5
Downstream XS Weight=0.25
Number of DS XS's Weighted with US Boundary= 1
Upstream Boundary Weight= 1
Weight of XSs Associated with US Boundary= 0
Number of US XS's Weighted with DS Boundary= 1
Downstream Boundary Weight= 0.5
Weight of XSs Associated with DS Boundary= 0.5
Sediment Output Level= 4
Mass or Volume Output= 0
Output Increment Type= 1
Profile and TS Output Increment= 10
XS Output Flag= 0
XS Output Increment= 10
Disregard all LS=0
Disregard all Conn=0
Disregard all Breaches=0
Disregard all Pumps=0

--- 020522_white_swamp.p01 (plan) ---

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Plan Title=White Swamp
Version=Version 3.0.1  Mar 2001
Short Identifier=Base Plan
Geom File=g01
Flow File=f01
Encroach River=Main Stem
Encroach Reach=Reach - 1
Encroach Node=18500.0
       1    4945    5078
Encroach Node=18127.5
       4      .7
Encroach Node=17600.2
       4      .7
Encroach Node=17000.0
       4      .7
Encroach Node=16500.0
       4      .7
Encroach Node=15631.8
       4      .7
Encroach Node=15000.0
       4      .7
Encroach Node=14642.1
       4      .7
Encroach Node=14193.5
       4      .7
Encroach Node=13372.6
       1    4944    5230
Encroach Node=13349.1
       1    4944    5230
Encroach Node=13325.6
       1    4944    5230
Encroach Node=12794.4
       1    4828    5064
Encroach Node=12000.0
       4      .7
Encroach Node=11095.4
       4      .7
Encroach Node=10500.0
       4      .7
Encroach Node=9945.1
       4      .7
Encroach Node=9285.3
       4      .7
Encroach Node=8500.0
       4      .7
Encroach Node=8000.0
       4      .7
Encroach Node=7362.9
       4      .7
Encroach Node=6253.5
       4      .7
Encroach Node=5405.7
       4      .7
Encroach Node=4908.8
       1    4727    5068
Encroach Node=3600.6
       1    4958    5041
Encroach Node=3579.1
       1    4958    5041
Encroach Node=3557.6
       1    4958    5041
Encroach Node=3142.6
       4      .7
Encroach Node=2500.0
       4      .7
Encroach Node=1756.1
       1    4877    5268
Encroach Node=1000.0
       4      .7
Write Velocity= 0

--- 020522_white_swamp.f02 (steady flow) ---

Flow Title=Multi_Profile
Program Version=4.00
Number of Profiles= 7
Profile Names=10yr,25yr,50yr,500yr,100yr-10%,100yr-20%,100yr-35%
River Rch & RM=Main Stem,Reach - 1       ,18500.0
     477     689     881    1747    1893    2426    2965
River Rch & RM=Main Stem,Reach - 1       ,15631.8
     782    1110    1404    2695    2940    3768    4604
River Rch & RM=Main Stem,Reach - 1       ,13325.6
     819    1162    1467    2808    3066    3929    4800
River Rch & RM=Main Stem,Reach - 1       ,6253.5
     975    1373    1728    3270    3577    4585    5602
River Rch & RM=Main Stem,Reach - 1       ,3600.6
    1550    2148    2674    4911    5405    6927    8464
Boundary for River Rch & Prof#=Main Stem,Reach - 1       , 1
Up Type= 0
Dn Type= 3
Dn Slope=0.0007
Boundary for River Rch & Prof#=Main Stem,Reach - 1       , 2
Up Type= 0
Dn Type= 3
Dn Slope=0.0007
Boundary for River Rch & Prof#=Main Stem,Reach - 1       , 3
Up Type= 0
Dn Type= 3
Dn Slope=0.0007
Boundary for River Rch & Prof#=Main Stem,Reach - 1       , 4
Up Type= 0
Dn Type= 3
Dn Slope=0.0007
Boundary for River Rch & Prof#=Main Stem,Reach - 1       , 5
Up Type= 0
Dn Type= 3
Dn Slope=0.0007
Boundary for River Rch & Prof#=Main Stem,Reach - 1       , 6
Up Type= 0
Dn Type= 3
Dn Slope=0.0007
Boundary for River Rch & Prof#=Main Stem,Reach - 1       , 7
Up Type= 0
Dn Type= 3
Dn Slope=0.0007
DSS Import GetInterval= 0
DSS Import GetPeak= 0
DSS Import FillOption= 0

--- 020522_white_swamp.f01 (steady flow) ---

Flow Title=White Swamp
Version=Version 3.0.1  Mar 2001
Number of Profiles= 2
Profile Names=100-YEAR,AFW
River Rch & RM=Main Stem,Reach - 1       ,18500.0
    1102    1102
River Rch & RM=Main Stem,Reach - 1       ,15631.8
    1737    1737
River Rch & RM=Main Stem,Reach - 1       ,13325.6
    1814    1814
River Rch & RM=Main Stem,Reach - 1       ,6253.5
    2128    2128
River Rch & RM=Main Stem,Reach - 1       ,3600.6
    3262    3262
Boundary for River Rch & Prof#=Main Stem,Reach - 1       , 1
Up Type= 0
Dn Type= 3
Dn Slope=.0007
DSS Import GetInterval= 0
DSS Import GetPeak= 0
DSS Import FillOption= 0

--- 020522_white_swamp.g01 (geometry) ---

Geom Title=Geom 01 by CodeH2 for Windows

River Reach=Main Stem,Reach - 1
Reach XY= 2
              .5             .95              .5             .05

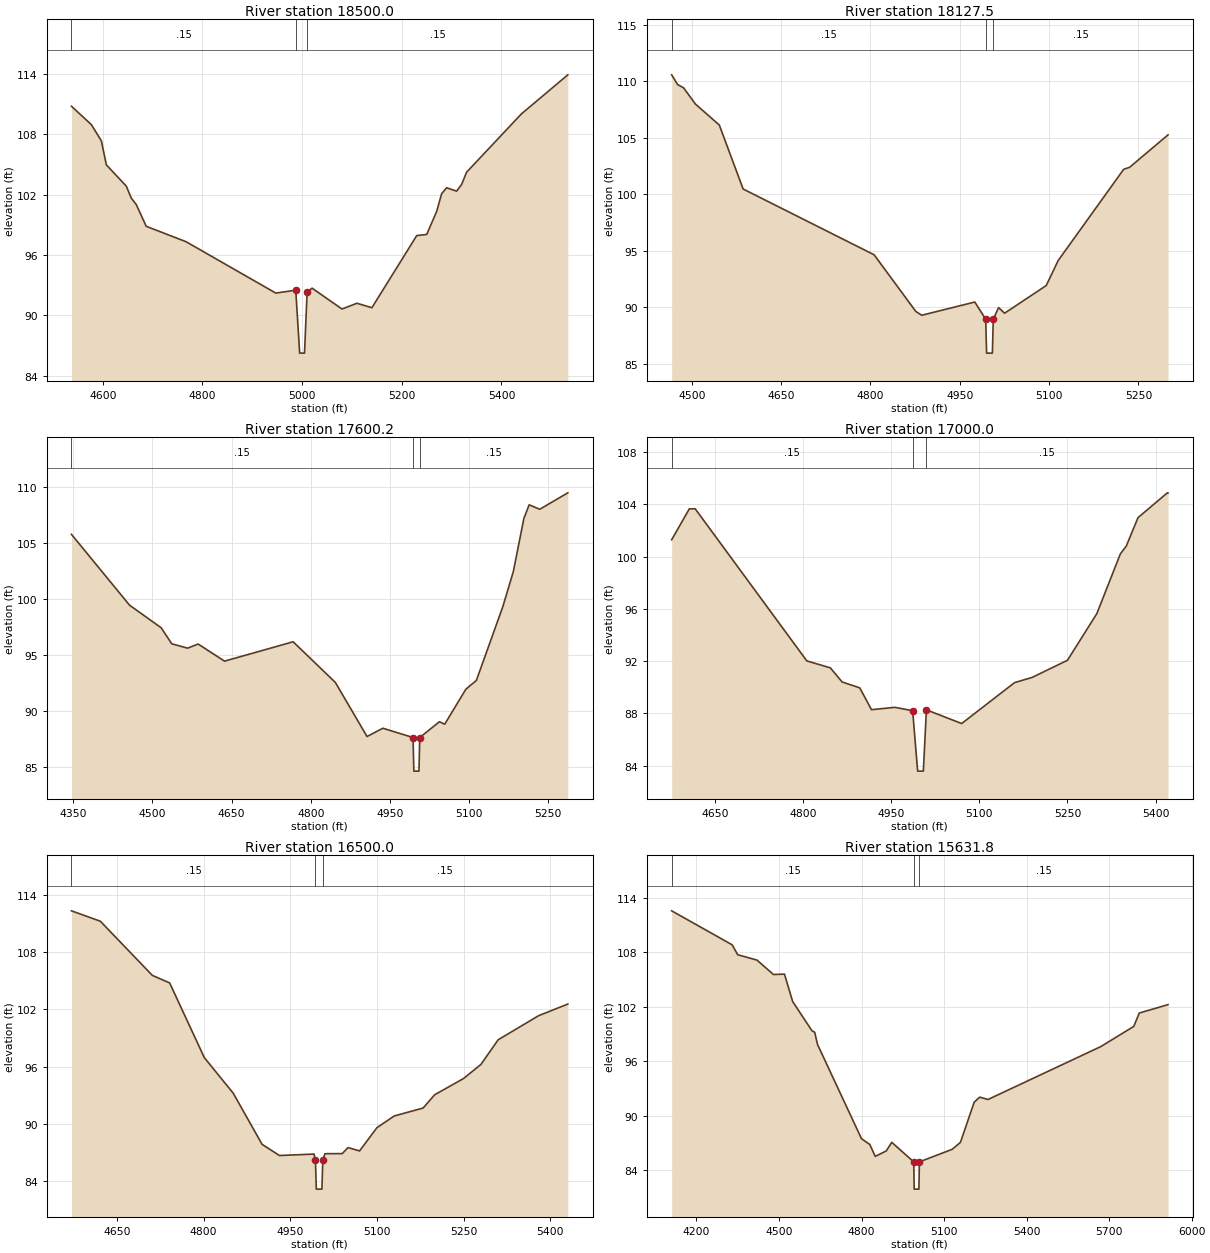
Type RM Length L Ch R = 1 ,18500.0,372.5,372.5,372.5
BEGIN DESCRIPTION:
White Swamp 36.0
END DESCRIPTION:
#Sta/Elev= 28
  4537.2  110.77  4577.2  108.94  4597.2  107.33  4607.2  104.95  4647.2  102.84
  4657.2  101.65  4667.2  101.01  4687.2   98.85  4767.2   97.32  4947.2   92.22
  4987.2   92.51  4995.1   86.26  5004.8   86.26    5010    92.3    5020   92.71
    5080   90.64    5110   91.21    5140   90.77    5230   97.93    5250   98.04
    5270  100.33    5280  102.09    5290  102.68    5310  102.34    5320     103
    5330  104.22    5440  110.01  5533.2  113.89
#Mann= 3 , 1 , 0
 4537.20    0.15       0  4987.2   0.044       0    5010    0.15       0
Bank Sta=4987.20,5010.00
Exp/Cntr=0.3,0.1

Type RM Length L Ch R = 1 ,18127.5,527.3,527.3,527.3
BEGIN DESCRIPTION:
White Swamp 35.0
END DESCRIPTION:
#Sta/Elev= 21
  4466.2  110.55  4476.2  109.69  4486.2   109.4  4506.2  107.96  4546.2  106.11
  4586.2  100.45  4806.2   94.63  4876.2   89.62  4886.2   89.28  4975.3   90.45
  4993.6   88.93  4995.1   85.93  5004.8   85.93  5006.3   88.93  5015.3   89.96
  5025.3   89.46  5095.3   91.91  5115.3   94.12  5225.3  102.19  5235.3  102.37
  5299.8  105.24
#Mann= 3 , 1 , 0
 4466.20    0.15       0  4993.6   0.044       0  5006.3    0.15       0
Bank Sta=4993.60,5006.30
Exp/Cntr=0.3,0.1

Type RM Length L Ch R = 1 ,17600.2,600.2,600.2,600.2
BEGIN DESCRIPTION:
White Swamp 34.0
END DESCRIPTION:
#Sta/Elev= 26
  4346.5  105.81  4456.5   99.49  4516.5   97.47  4536.5   96.04  4566.5   95.65
  4586.5   96.02  4636.5   94.49  4766.5   96.22  4846.5   92.59  4906.5   87.76
  4936.5    88.5  4993.6   87.67  4993.7   87.67  4995.2   84.67  5004.9   84.67
  5006.4   87.67  5043.7   89.08  5053.7   88.86  5093.7   91.98  5113.7   92.77
  5163.7   99.34  5183.7  102.49  5203.7  107.23  5213.7  108.45  5233.7  108.05
    5287  109.52
#Mann= 3 , 1 , 0
 4346.50    0.15       0  4993.6   0.044       0  5006.4    0.15       0
Bank Sta=4993.60,5006.40
Exp/Cntr=0.3,0.1

Type RM Length L Ch R = 1 ,17000.0,500,500,500
BEGIN DESCRIPTION:
White Swamp 33.0
END DESCRIPTION:
#Sta/Elev= 23
  4576.6  101.29  4606.6  103.65  4616.6  103.66  4806.6   92.02  4846.6   91.49
  4866.6   90.41  4896.6   89.96  4916.6   88.29  4956.6   88.47  4986.6   88.21
  4995.1   83.59  5004.8   83.59    5010   88.28    5070   87.23    5160   90.36
    5190   90.76    5250   92.07    5300   95.64    5340  100.21    5350   100.8
    5370  102.98    5420  104.88  5421.1  104.86
#Mann= 3 , 1 , 0
 4576.60    0.15       0  4986.6   0.044       0    5010    0.15       0
Bank Sta=4986.60,5010.00
Exp/Cntr=0.3,0.1

Type RM Length L Ch R = 1 ,16500.0,868.2,868.2,868.2
BEGIN DESCRIPTION:
White Swamp 32.0
END DESCRIPTION:
#Sta/Elev= 26
  4571.2  112.33  4621.2  111.24  4711.2  105.57  4741.2  104.78  4801.2   96.96
  4851.2   93.24  4901.2   87.88  4931.2   86.71  4991.2   86.86  4993.6   86.19
  4995.1   83.19  5004.8   83.19  5006.3   86.19    5010    86.9    5040   86.91
    5050   87.54    5070   87.19    5100   89.62    5130   90.85    5180   91.68
    5200   93.07    5250   94.77    5280   96.24    5310   98.83    5380  101.35
  5430.6  102.57
#Mann= 3 , 1 , 0
 4571.20    0.15       0  4993.6   0.044       0  5006.3    0.15       0
Bank Sta=4993.60,5006.30
Exp/Cntr=0.3,0.1

Type RM Length L Ch R = 1 ,15631.8,631.8,631.8,631.8
BEGIN DESCRIPTION:
White Swamp 30.0
END DESCRIPTION:
#Sta/Elev= 29
  4109.9  112.59  4329.9  108.84  4349.9  107.75  4419.9  107.16  4479.9  105.57
  4519.9  105.61  4549.9  102.58  4619.9   99.37  4629.9    99.2  4639.9   97.87
  4799.9   87.47  4829.9   86.84  4849.9   85.52  4889.9   86.12  4909.9   87.07
  4989.8   84.91  4989.9   84.91  4991.4   81.91  5008.7   81.91  5010.2   84.91
  5129.6    86.3  5159.6   87.07  5209.6    91.5  5229.6   92.05  5259.6   91.79
  5669.6   97.62  5789.6   99.85  5809.6  101.32  5914.1  102.25
#Mann= 3 , 1 , 0
 4109.90    0.15       0  4989.8   0.044       0  5010.2    0.15       0
Bank Sta=4989.80,5010.20
Exp/Cntr=0.3,0.1

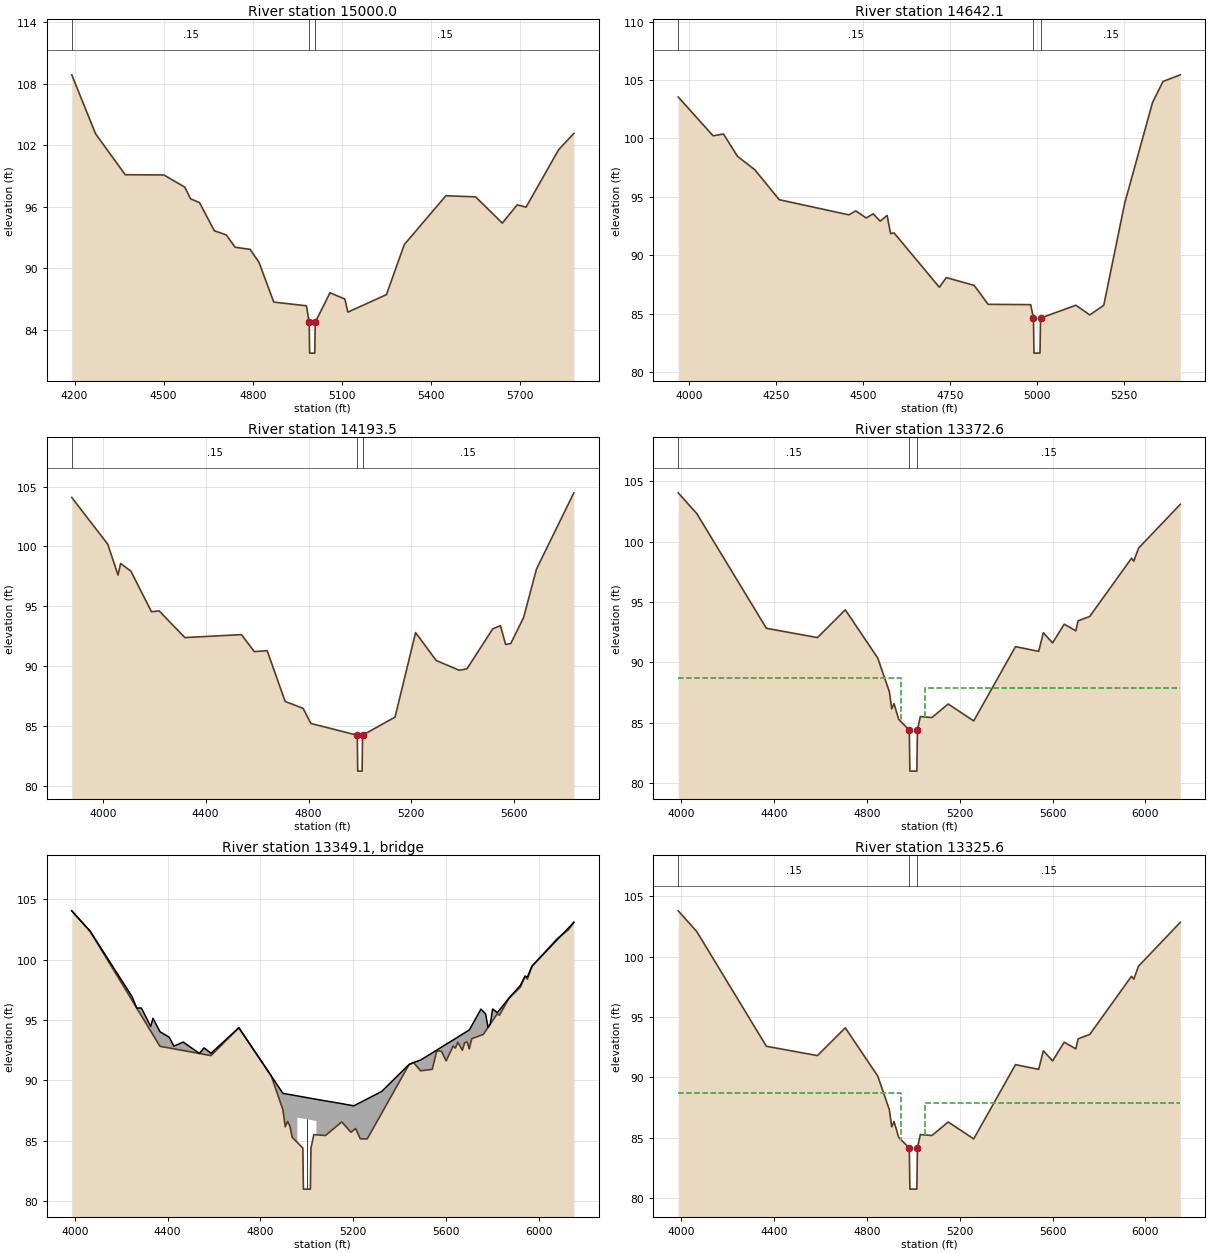
Type RM Length L Ch R = 1 ,15000.0,357.9,357.9,357.9
BEGIN DESCRIPTION:
White Swamp 29.0
END DESCRIPTION:
#Sta/Elev= 30
  4190.7  108.87  4270.7  103.12  4370.7   99.12  4500.7    99.1  4570.7   97.92
  4590.7   96.77  4620.7    96.4  4670.7   93.65  4710.7   93.25  4740.7   92.04
  4790.7   91.84  4820.7   90.59  4870.7   86.69  4980.7   86.33  4989.9   84.71
  4991.4   81.71  5008.7   81.71  5010.2   84.71    5060    87.6    5110   86.99
    5120   85.71    5250   87.42    5310    92.3    5450   97.07    5550   96.96
    5640    94.4    5690   96.18    5720   95.96    5830  101.58  5880.8  103.15
#Mann= 3 , 1 , 0
 4190.70    0.15       0  4989.9   0.044       0  5010.2    0.15       0
Bank Sta=4989.90,5010.20
Exp/Cntr=0.3,0.1

Type RM Length L Ch R = 1 ,14642.1,448.6,448.6,448.6
BEGIN DESCRIPTION:
White Swamp 28.0
END DESCRIPTION:
#Sta/Elev= 30
  3969.6  103.55  4069.6  100.23  4099.6  100.38  4139.6   98.48  4189.6   97.32
  4259.6   94.76  4459.6   93.46  4479.6    93.8  4509.6   93.19  4529.6   93.55
  4549.6   92.92  4569.6   93.41  4579.6   91.86  4589.6   91.91  4719.6   87.26
  4739.6   88.09  4819.6   87.42  4859.6    85.8  4981.9   85.77  4989.9   84.62
  4991.4   81.62  5008.7   81.62  5010.2   84.62  5111.9   85.72  5151.9   84.89
  5191.9   85.72  5251.9   94.45  5331.9  103.08  5361.9  104.88  5411.7  105.45
#Mann= 3 , 1 , 0
 3969.60    0.15       0  4989.9   0.044       0  5010.2    0.15       0
Bank Sta=4989.90,5010.20
Exp/Cntr=0.3,0.1

Type RM Length L Ch R = 1 ,14193.5,820.9,820.9,820.9
BEGIN DESCRIPTION:
White Swamp 27.0
END DESCRIPTION:
#Sta/Elev= 30
  3879.1  104.09  4019.1  100.19  4059.1   97.61  4069.1   98.58  4109.1   97.94
  4189.1   94.55  4219.1   94.62  4319.1   92.39  4539.1   92.64  4589.1   91.22
  4639.1    91.3  4709.1   87.06  4779.1   86.48  4809.1   85.22  4989.8   84.24
  4991.3   81.24  5008.6   81.24  5010.1   84.24  5136.6   85.75  5216.6   92.81
  5296.6   90.48  5386.6   89.66  5416.6   89.79  5516.6   93.12  5546.6   93.39
  5566.6   91.82  5586.6   91.89  5636.6   94.06  5686.6    98.1  5832.1  104.48
#Mann= 3 , 1 , 0
 3879.10    0.15       0  4989.8   0.044       0  5010.1    0.15       0
Bank Sta=4989.80,5010.10
Exp/Cntr=0.3,0.1

Type RM Length L Ch R = 1 ,13372.6,47,47,47
BEGIN DESCRIPTION:
Upstream Section of Bridge/Culvert/Weir
END DESCRIPTION:
#Sta/Elev= 30
  3986.8  104.05  4066.8  102.33  4366.7   92.83  4586.7   92.06  4706.7   94.36
  4846.7   90.36  4896.7   87.57  4906.7   86.16  4916.7    86.6  4936.7   85.29
  4982.5    84.4    4985      81    5015      81  5017.5    84.4    5030   85.52
    5080   85.44    5150   86.56    5260   85.16    5440   91.31    5540   90.92
    5560   92.46    5600   91.62    5650   93.17    5700   92.62    5710   93.45
    5760   93.81    5940   98.63    5950   98.39    5970   99.46  6150.3   103.1
#Mann= 3 , 1 , 0
 3986.80    0.15       0  4982.5   0.044       0  5017.5    0.15       0
#XS Ineff= 2 , 0
       0    4948   88.74    5051       0   87.91
Bank Sta=4982.50,5017.50
Exp/Cntr=0.5,0.3

Type RM Length L Ch R = 3 ,13349.1,,,
BEGIN DESCRIPTION:
Cattail Road1-TOR
Structure ID: Cattail Rd-Bridge
Approximate Survey Structure
END DESCRIPTION:
Bridge Culvert--1,0,-1,-1, 0
Deck Dist Width WeirC Skew NumUp NumDn MinLoCord MaxHiCord MaxSubmerge Is_Ogee
10,27,2.6,, 60, 60,,,0.95,0,1,1,,
  3986.8  4066.8  4246.8  4266.8  4286.8  4326.8  4336.8  4366.7  4406.8  4426.8
  4466.8  4536.8  4556.8  4586.7  4706.7  4846.7  4896.7  4906.7  4916.7  4936.7
 4958.91    4959 5040.89    5041    5080    5150    5190  5202.4    5210    5230
    5260  5322.4    5440    5460    5490    5540    5560    5580    5600    5630
    5640    5650    5670    5680    5690    5700    5710  5750.2  5770.2  5780.2
  5790.2  5800.2  5820.2    5830    5870    5920    5940    5950    5970  6150.3
  104.05  102.34   96.94      96      96   94.48   95.15   94.04   93.58   92.84
   93.18   92.24    92.7   92.25   94.37   90.37   88.93    88.9   88.86    88.8
   88.72   88.72   88.44   88.44   88.31   88.08   87.94    87.9   87.98   88.17
   88.47   89.09   91.32   91.49   91.69   92.28   92.52   92.76      93   93.35
   93.47   93.59   93.83   93.95   94.07   94.19   94.53   95.91   95.51   94.39
   94.68   95.92   95.62   95.84    96.8   97.88   98.64   98.56   99.47   103.1
  104.05  102.33   96.63   95.99   95.36   94.09   93.78   92.83   92.69   92.62
   92.48   92.23   92.16   92.06   94.36   90.36   87.57   86.16    86.6   85.29
   84.86   86.92   86.64    85.5   85.44   86.56   85.71    85.9   86.02   85.17
   85.16   87.29   91.31   91.48    90.8   90.92   92.46   92.41   91.62   92.84
   92.68   93.17    92.5   93.13   93.19   92.62   93.45   93.74    94.1   94.38
   94.67   94.95   95.51   95.41   96.79   97.73   98.63   98.39   99.46   103.1
  3986.8  4066.8  4246.8  4266.8  4286.8  4326.8  4336.8  4366.7  4406.8  4426.8
  4466.8  4536.8  4556.8  4586.7  4706.7  4846.7  4896.7  4906.7  4916.7  4936.7
 4958.91    4959 5040.89    5041    5080    5150    5190  5202.4    5210    5230
    5260  5322.4    5440    5460    5490    5540    5560    5580    5600    5630
    5640    5650    5670    5680    5690    5700    5710  5750.2  5770.2  5780.2
  5790.2  5800.2  5820.2    5830    5870    5920    5940    5950    5970  6150.3
  104.05  102.34   96.94      96      96   94.48   95.15   94.04   93.58   92.84
   93.18   92.24    92.7   92.25   94.37   90.37   88.93    88.9   88.86    88.8
   88.72   88.72   88.44   88.44   88.31   88.08   87.94    87.9   87.98   88.17
   88.47   89.09   91.32   91.49   91.69   92.28   92.52   92.76      93   93.35
   93.47   93.59   93.83   93.95   94.07   94.19   94.53   95.91   95.51   94.39
   94.68   95.92   95.62   95.84    96.8   97.88   98.64   98.56   99.47   103.1
   103.8  102.08   96.38   95.74   95.11   93.84   93.53   92.58   92.44   92.37
   92.23   91.98   91.91   91.81   94.11   90.11   87.32   85.91   86.35   85.04
   84.61   86.67   86.39   85.25   85.19   86.31   85.46   85.65   85.77   84.92
   84.91   87.04   91.06   91.23   90.55   90.67   92.21   92.16   91.37   92.59
   92.43   92.92   92.25   92.88   92.94   92.37    93.2   93.49   93.85   94.13
   94.42    94.7   95.26   95.16   96.54   97.48   98.38   98.14   99.21  102.85
Pier Skew, UpSta & Num, DnSta & Num=,5000.0, 2 ,5000.0, 2 , 0 , 0 , 0 ,,
       1       1
      80   87.78
       1       1
   79.75   87.53
Abutment Skew #Up #Dn=, 2 , 2
 4958.80 4960.00
   86.92   84.84
 4958.80 4960.00
   86.67   84.59
Abutment Skew #Up #Dn=, 2 , 2
 5040.00 5041.09
   85.50   86.64
 5040.00 5041.09
   85.25   86.39
BR Coef= 1 , 1 , 0 ,1.25, 0 ,,,0.8,0,2,0,
Wspro=,,,, 1 ,,,, 0 ,,,, 0 ,,,,-1 ,-1 ,-1 , 0 , 0 , 0 , 0 , 0
BC Design=,, 0 ,, 0 ,,,,,,
BR U #Sta/Elev= 106
  3986.8  104.05  4016.8   103.4  4026.8  103.19  4056.8  102.54  4066.7  102.33
  4066.8  102.33  4076.8  102.01  4096.8  101.38  4106.8  101.06  4116.8  100.74
  4136.8  100.11  4146.8   99.79  4156.8   99.48  4186.8   98.53  4216.8   97.58
  4226.8   97.26  4246.8   96.63  4266.8   95.99  4286.8   95.36  4326.8   94.09
  4336.8   93.78  4366.7   92.83  4376.8   92.79  4406.8   92.69  4426.8   92.62
  4466.8   92.48  4486.8   92.41  4526.8   92.27  4536.8   92.23  4556.8   92.16
  4586.7   92.06  4616.8   92.64  4636.8   93.02  4686.8   93.98  4696.8   94.17
  4706.7   94.36  4712.4    94.2  4732.4   93.63  4762.4   92.77  4772.4   92.48
  4792.4   91.91  4802.4   91.63  4812.4   91.34  4842.4   90.48  4846.7   90.36
  4852.4   90.04  4896.7   87.57  4906.7   86.16  4916.7    86.6  4926.7   86.22
  4936.7   85.29 4958.91   84.86    4959   84.86    4960   84.84  4982.5    84.4
    4985      81    5015      81  5017.5    84.4    5030   85.52    5040    85.5
 5040.89    85.5    5041    85.5    5080   85.44    5150   86.56    5190   85.71
  5202.4    85.9    5210   86.02    5230   85.17    5260   85.16  5322.4   87.29
  5380.2   89.27  5410.2   90.29    5440   91.31    5460   91.48  5480.2   91.02
    5490    90.8    5540   90.92    5560   92.46    5580   92.41    5600   91.62
    5630   92.84    5640   92.68    5650   93.17    5670    92.5    5680   93.13
    5690   93.19    5700   92.62  5700.2   92.64    5710   93.45  5750.2   93.74
    5760   93.81  5770.2    94.1  5780.2   94.38  5790.2   94.67  5800.2   94.95
    5820   95.51  5820.2   95.51    5830   95.41    5870   96.79    5920   97.73
    5940   98.63    5950   98.39    5970   99.46    6080  101.77  6127.4  102.48
  6150.3   103.1
BR U #Mann= 3
 3986.80    0.15  4982.5   0.044  5017.5    0.15
BR U Banks=4982.50,5017.50
BR D #Sta/Elev= 106
  3986.8   103.8  4016.8  103.15  4026.8  102.94  4056.8  102.29  4066.7  102.08
  4066.8  102.08  4076.8  101.76  4096.8  101.13  4106.8  100.81  4116.8  100.49
  4136.8   99.86  4146.8   99.54  4156.8   99.23  4186.8   98.28  4216.8   97.33
  4226.8   97.01  4246.8   96.38  4266.8   95.74  4286.8   95.11  4326.8   93.84
  4336.8   93.53  4366.7   92.58  4376.8   92.54  4406.8   92.44  4426.8   92.37
  4466.8   92.23  4486.8   92.16  4526.8   92.02  4536.8   91.98  4556.8   91.91
  4586.7   91.81  4616.8   92.39  4636.8   92.77  4686.8   93.73  4696.8   93.92
  4706.7   94.11  4712.4   93.95  4732.4   93.38  4762.4   92.52  4772.4   92.23
  4792.4   91.66  4802.4   91.38  4812.4   91.09  4842.4   90.23  4846.7   90.11
  4852.4   89.79  4896.7   87.32  4906.7   85.91  4916.7   86.35  4926.7   85.97
  4936.7   85.04 4958.91   84.61    4959   84.61    4960   84.59  4982.5   84.15
    4985   80.75    5015   80.75  5017.5   84.15    5030   85.27    5040   85.25
 5040.89   85.25    5041   85.25    5080   85.19    5150   86.31    5190   85.46
  5202.4   85.65    5210   85.77    5230   84.92    5260   84.91  5322.4   87.04
  5380.2   89.02  5410.2   90.04    5440   91.06    5460   91.23  5480.2   90.77
    5490   90.55    5540   90.67    5560   92.21    5580   92.16    5600   91.37
    5630   92.59    5640   92.43    5650   92.92    5670   92.25    5680   92.88
    5690   92.94    5700   92.37  5700.2   92.39    5710    93.2  5750.2   93.49
    5760   93.56  5770.2   93.85  5780.2   94.13  5790.2   94.42  5800.2    94.7
    5820   95.26  5820.2   95.26    5830   95.16    5870   96.54    5920   97.48
    5940   98.38    5950   98.14    5970   99.21    6080  101.52  6127.4  102.23
  6150.3  102.85
BR D #Mann= 3
 3986.80    0.15  4982.5   0.044  5017.5    0.15
BR D Banks=4982.50,5017.50

Type RM Length L Ch R = 1 ,13325.6,531.2,531.2,531.2
BEGIN DESCRIPTION:
Downstream Section of Bridge/Culvert/Weir
END DESCRIPTION:
#Sta/Elev= 30
  3986.8  103.79  4066.8  102.07  4366.7   92.57  4586.7    91.8  4706.7    94.1
  4846.7    90.1  4896.7   87.31  4906.7    85.9  4916.7   86.34  4936.7   85.03
  4982.5   84.14    4985   80.74    5015   80.74  5017.5   84.14    5030   85.26
    5080   85.18    5150    86.3    5260    84.9    5440   91.05    5540   90.66
    5560    92.2    5600   91.36    5650   92.91    5700   92.36    5710   93.19
    5760   93.55    5940   98.37    5950   98.13    5970    99.2  6150.3  102.84
#Mann= 3 , 1 , 0
 3986.80    0.15       0  4982.5   0.044       0  5017.5    0.15       0
#XS Ineff= 2 , 0
       0    4948   88.74    5051       0   87.91
Bank Sta=4982.50,5017.50
Exp/Cntr=0.5,0.3

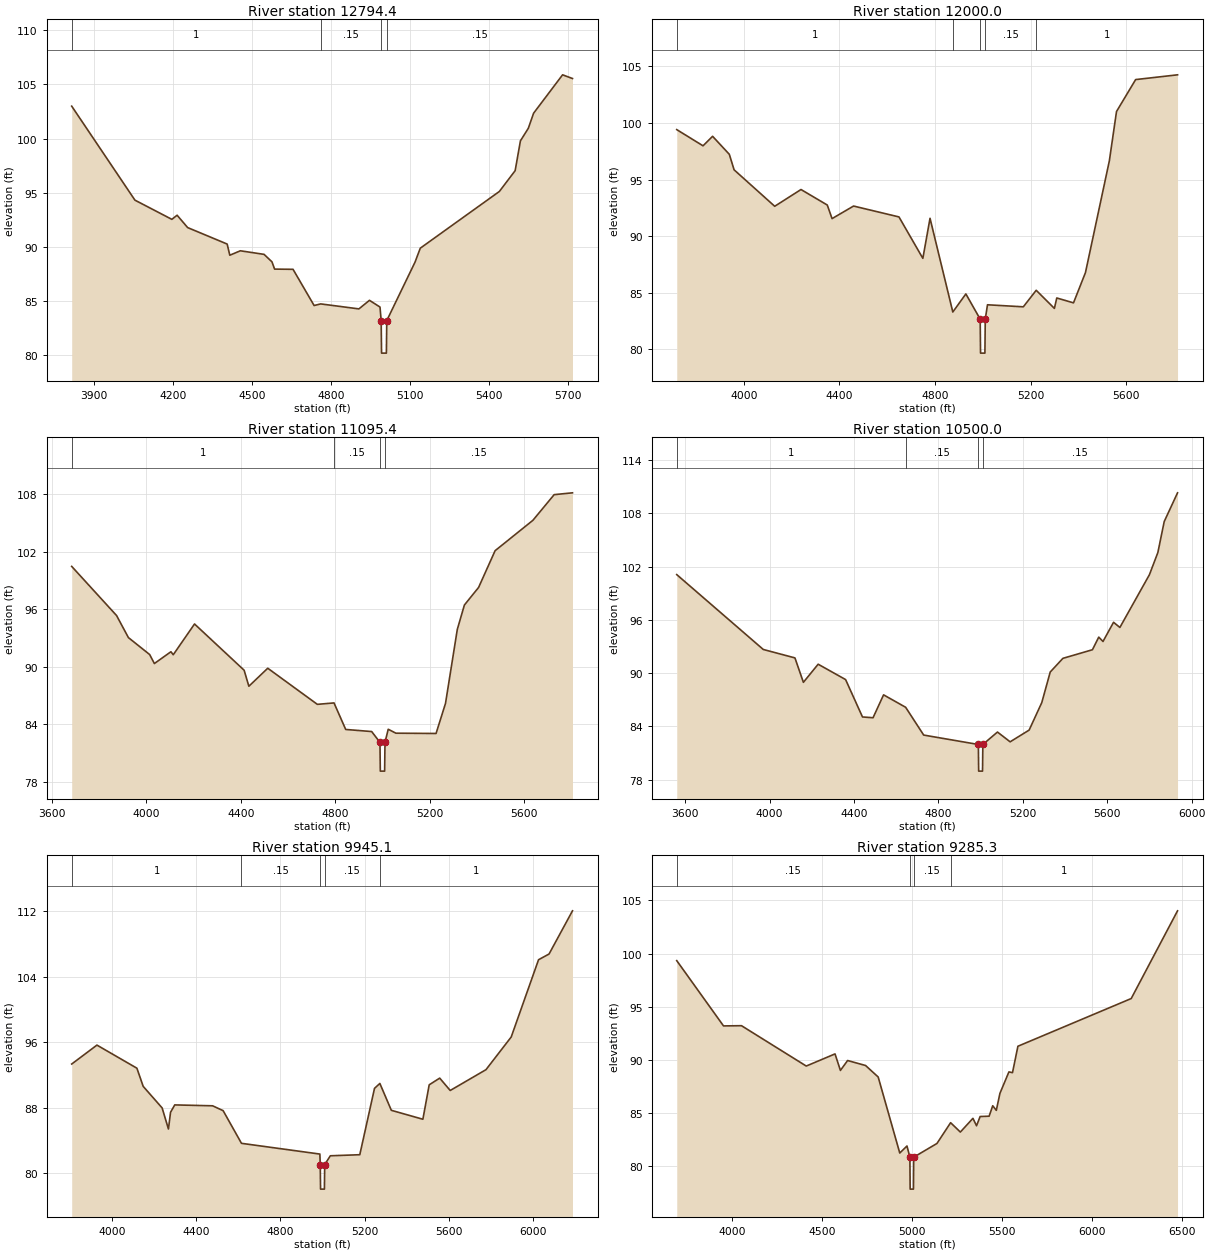
Type RM Length L Ch R = 1 ,12794.4,794.4,794.4,794.4
BEGIN DESCRIPTION:
White Swamp 24.0
END DESCRIPTION:
#Sta/Elev= 30
    3815  102.99    4055   94.32    4195   92.55    4215   92.93    4255   91.79
    4405   90.27    4415   89.24    4455   89.65    4545   89.32    4575   88.63
    4585   87.96    4655   87.94    4735    84.6  4759.9   84.75    4905   84.29
    4945   85.08    4985   84.46  4989.4   83.21  4990.9   80.21  5009.2   80.21
  5010.7   83.21  5117.9    88.6  5137.9   89.89  5437.9   95.12  5497.9   97.04
  5517.9   99.79  5547.9  100.95  5567.9  102.34  5677.9  105.88  5715.5  105.54
#Mann= 4 , 1 , 0
 3815.00       1       0  4759.9    0.15       0  4989.4   0.044       0
  5010.7    0.15       0
Bank Sta=4989.40,5010.70
Exp/Cntr=0.3,0.1

Type RM Length L Ch R = 1 ,12000.0,904.6,904.6,904.6
BEGIN DESCRIPTION:
White Swamp 23.0
END DESCRIPTION:
#Sta/Elev= 30
  3719.5   99.41  3829.5   97.98  3869.5   98.82  3939.5   97.23  3959.5   95.86
  4129.5   92.64  4239.5   94.12  4349.5   92.75  4369.5   91.55  4459.5   92.66
  4649.5    91.7  4749.5   88.04  4779.5   91.58  4874.9    83.3  4929.5    84.9
  4989.4   82.67  4990.9   79.67  5009.2   79.67  5010.7   82.67    5020   83.94
    5170   83.76  5223.9   85.22    5300   83.62    5310   84.54    5380   84.11
    5430   86.78    5530   96.65    5560  101.01    5640  103.83  5815.4  104.25
#Mann= 5 , 1 , 0
 3719.50       1       0  4874.9    0.15       0  4989.4   0.044       0
  5010.7    0.15       0  5223.9       1       0
Bank Sta=4989.40,5010.70
Exp/Cntr=0.3,0.1

Type RM Length L Ch R = 1 ,11095.4,595.4,595.4,595.4
BEGIN DESCRIPTION:
White Swamp 21.0
END DESCRIPTION:
#Sta/Elev= 30
  3684.4  100.47  3874.4   95.34  3924.4   93.04  4014.4   91.27  4034.4   90.33
  4104.4   91.56  4114.4   91.25  4204.4   94.46  4414.4   89.63  4434.4   87.96
  4514.4   89.84  4724.4   86.07  4794.9   86.22  4844.4   83.45  4954.4   83.23
  4989.4    82.1  4990.9    79.1  5009.2    79.1  5010.7    82.1  5024.4   83.47
  5056.9   83.06  5226.9   83.03  5266.9   86.17  5316.9    93.9  5346.9   96.44
  5406.9   98.27  5476.9  102.11  5636.9  105.28  5726.9  107.96  5804.5  108.15
#Mann= 4 , 1 , 0
 3684.40       1       0  4794.9    0.15       0  4989.4   0.044       0
  5010.7    0.15       0
Bank Sta=4989.40,5010.70
Exp/Cntr=0.3,0.1

Type RM Length L Ch R = 1 ,10500.0,554.9,554.9,554.9
BEGIN DESCRIPTION:
White Swamp 20.0
END DESCRIPTION:
#Sta/Elev= 30
  3560.4   101.1  3970.4   92.67  4120.4   91.72  4160.4   88.97  4230.4   91.01
  4360.4   89.28  4440.4   85.07  4490.4   84.98  4540.4   87.56  4644.9   86.16
  4730.4   83.03  4989.4   81.97  4990.9   78.97  5009.2   78.97  5010.7   81.97
    5080   83.37    5140   82.27    5230   83.59    5290   86.69    5330   90.13
    5390   91.67    5530   92.64    5560   94.06    5580   93.57    5630   95.73
    5660   95.15    5800  101.09    5840  103.59    5870  107.07  5933.2  110.31
#Mann= 4 , 1 , 0
 3560.40       1       0  4644.9    0.15       0  4989.4   0.044       0
  5010.7    0.15       0
Bank Sta=4989.40,5010.70
Exp/Cntr=0.3,0.1

Type RM Length L Ch R = 1 ,9945.1,659.8,659.8,659.8
BEGIN DESCRIPTION:
White Swamp 19.0
END DESCRIPTION:
#Sta/Elev= 30
  3807.6   93.35  3927.6   95.66  4117.6   92.84  4147.6   90.62  4237.6   87.99
  4267.6   85.42  4277.6   87.46  4297.6   88.36  4477.6   88.25  4527.6   87.66
  4614.9   83.67  4987.6   82.36  4989.4   81.08  4990.9   78.08  5009.2   78.08
  5010.7   81.08  5037.5   82.15  5177.5   82.28  5247.5   90.38  5272.9   90.98
  5327.5    87.7  5477.5   86.61  5507.5   90.81  5557.5   91.63  5607.5   90.12
  5777.5   92.66  5897.5   96.65  6027.5  106.08  6077.5  106.78  6188.9  112.05
#Mann= 5 , 1 , 0
 3807.60       1       0  4614.9    0.15       0  4989.4   0.044       0
  5010.7    0.15       0  5272.9       1       0
Bank Sta=4989.40,5010.70
Exp/Cntr=0.3,0.1

Type RM Length L Ch R = 1 ,9285.3,785.3,785.3,785.3
BEGIN DESCRIPTION:
White Swamp 17.0
END DESCRIPTION:
#Sta/Elev= 30
  3693.2   99.33  3953.2    93.2  4053.2   93.22  4413.2   89.43  4573.2   90.57
  4603.2   89.02  4643.2   89.95  4743.2   89.48  4813.2    88.4  4933.2   81.26
  4973.2   81.92  4989.4   80.87  4990.9   77.87  5009.2   77.87  5010.7   80.87
    5140   82.16  5215.9   84.11    5270   83.23    5340   84.52    5360   83.82
    5380   84.69    5430   84.72    5450    85.7    5470   85.27    5490   86.86
    5540   88.88    5560   88.81    5590   91.29    6220   95.77  6477.6  104.01
#Mann= 4 , 1 , 0
 3693.20    0.15       0  4989.4   0.044       0  5010.7    0.15       0
  5215.9       1       0
Bank Sta=4989.40,5010.70
Exp/Cntr=0.3,0.1

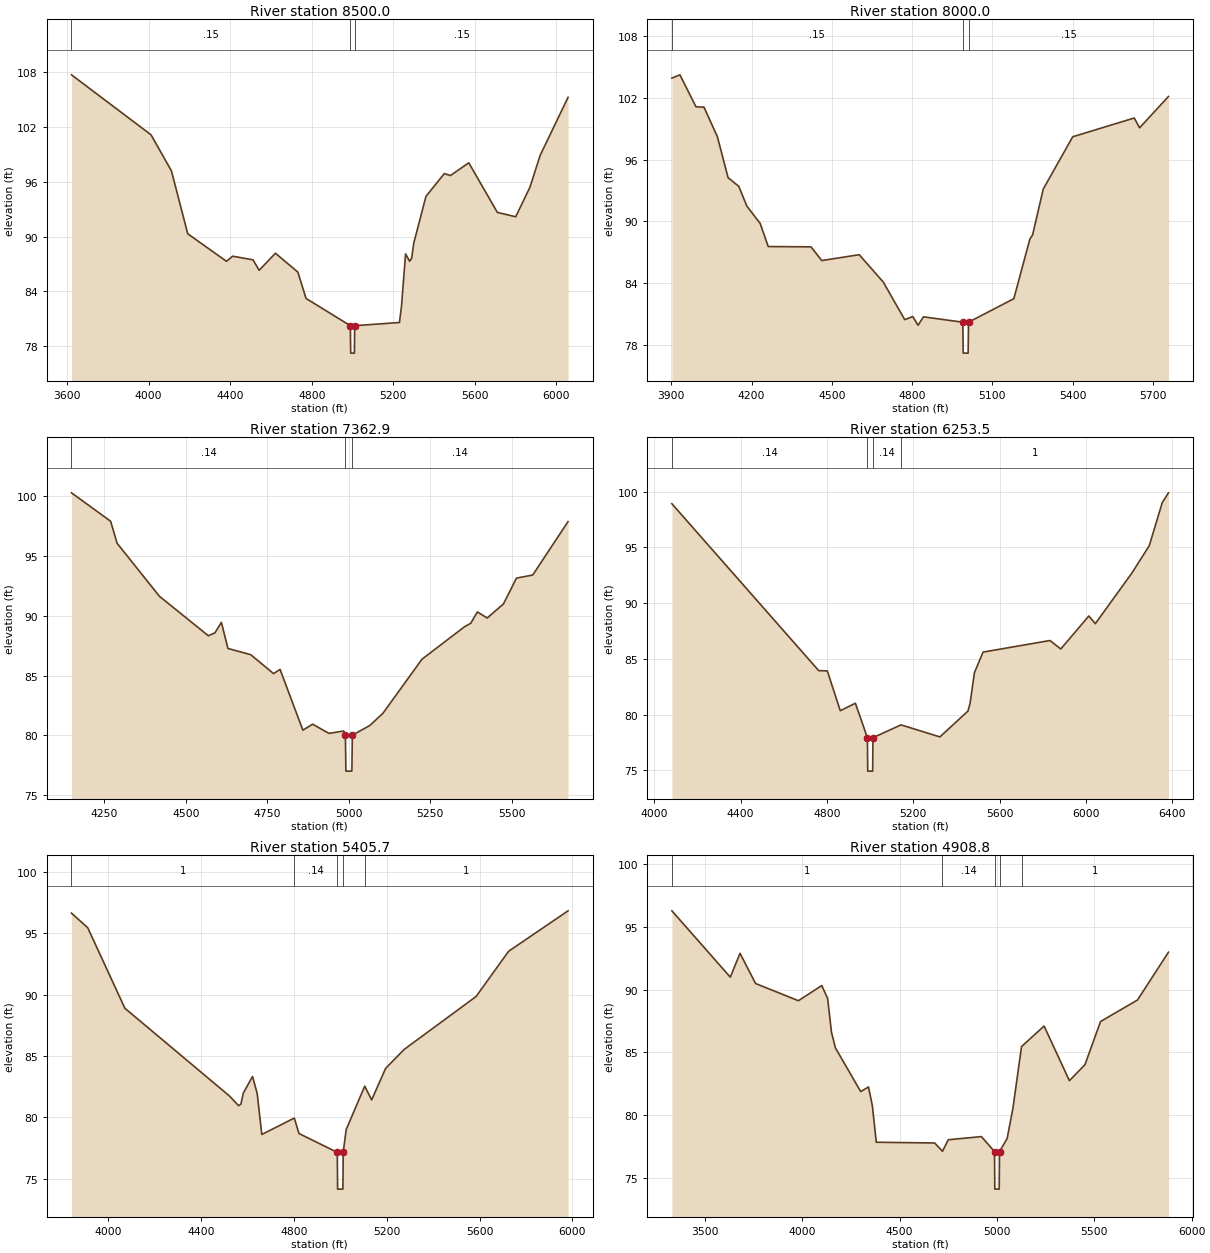
Type RM Length L Ch R = 1 ,8500.0,500,500,500
BEGIN DESCRIPTION:
White Swamp 16.0
END DESCRIPTION:
#Sta/Elev= 30
    3622  107.68    4012  101.12    4112   97.18    4192    90.3    4382   87.29
    4412   87.85    4512   87.45    4542   86.31    4622   88.17    4732   86.11
    4772   83.23  4989.3   80.25  4990.8   77.25  5009.1   77.25  5010.6   80.25
    5230    80.6    5240   82.38    5260    88.1    5280   87.29    5290   87.64
    5300   89.26    5360   94.39    5450   96.88    5480   96.67    5570   98.06
    5710   92.64    5800   92.16    5870    95.4    5920   98.88  6056.7  105.22
#Mann= 3 , 1 , 0
 3622.00    0.15       0  4989.3   0.044       0  5010.6    0.15       0
Bank Sta=4989.30,5010.60
Exp/Cntr=0.3,0.1

Type RM Length L Ch R = 1 ,8000.0,637.1,637.1,637.1
BEGIN DESCRIPTION:
White Swamp 15.0
END DESCRIPTION:
#Sta/Elev= 30
  3902.2   103.9  3932.2  104.22  3992.2  101.12  4022.2  101.08  4072.2   98.22
  4112.2   94.24  4152.2    93.4  4182.2   91.49  4232.2    89.8  4262.2   87.56
  4422.2   87.53  4462.2    86.2  4602.2   86.77  4692.2   84.11  4772.2   80.47
  4802.2   80.77  4822.2   79.92  4842.2   80.74  4989.3   80.22  4990.8   77.22
  5009.2   77.22  5010.7   80.22    5180    82.5    5240   88.29    5250   88.68
    5290   93.14    5400   98.21    5630  100.03    5650   99.08  5757.8  102.12
#Mann= 3 , 1 , 0
 3902.20    0.15       0  4989.3   0.044       0  5010.7    0.15       0
Bank Sta=4989.30,5010.70
Exp/Cntr=0.3,0.1

Type RM Length L Ch R = 1 ,7362.9,1109.4,1109.4,1109.4
BEGIN DESCRIPTION:
White Swamp 14.0
END DESCRIPTION:
#Sta/Elev= 30
  4148.9  100.25  4268.9   97.88  4288.9   96.04  4418.9   91.61  4568.9   88.32
  4588.9   88.56  4608.9   89.44  4628.9   87.26  4698.9   86.74  4768.9   85.16
  4788.9   85.51  4858.9   80.44  4888.9   80.94  4938.9   80.17  4984.3   80.37
  4989.4   80.02  4990.9   77.02  5009.2   77.02  5010.7   80.02  5064.3   80.83
  5104.3   81.84  5224.3   86.36  5354.3   89.06  5374.3   89.37  5394.3   90.31
  5424.3    89.8  5474.3   90.97  5514.3   93.13  5564.3   93.39  5672.6   97.85
#Mann= 3 , 1 , 0
 4148.90    0.14       0  4989.4   0.043       0  5010.7    0.14       0
Bank Sta=4989.40,5010.70
Exp/Cntr=0.3,0.1

Type RM Length L Ch R = 1 ,6253.5,847.8,847.8,847.8
BEGIN DESCRIPTION:
White Swamp 11.0
END DESCRIPTION:
#Sta/Elev= 24
  4081.5   98.91  4761.5   83.94  4801.5   83.91  4861.5   80.34  4931.5   81.01
  4987.2   77.92  4988.7   74.92  5011.4   74.92  5012.9   77.92  5142.9   79.07
    5143   79.07    5323   77.99    5453   80.31    5463   81.02    5483   83.76
    5523    85.6    5833   86.64    5883   85.88    6013   88.84    6043   88.15
    6213   92.71    6293   95.15    6353   99.01  6381.8   99.89
#Mann= 4 , 1 , 0
 4081.50    0.14       0  4987.2   0.043       0  5012.9    0.14       0
  5142.9       1       0
Bank Sta=4987.20,5012.90
Exp/Cntr=0.3,0.1

Type RM Length L Ch R = 1 ,5405.7,496.9,496.9,496.9
BEGIN DESCRIPTION:
White Swamp 10.0
END DESCRIPTION:
#Sta/Elev= 26
    3842   96.66    3912   95.47    4072    88.9    4522   81.75    4562   80.95
    4572   81.08    4582   81.97    4622   83.33    4642   81.95    4662    78.6
  4799.9   79.92    4802   79.94    4822   78.68  4987.1   77.14  4988.6   74.14
  5011.3   74.14  5012.8   77.14  5025.3   78.99  5105.3   82.54  5105.9   82.52
  5135.3   81.42  5195.3   83.99  5275.3   85.54  5585.3   89.86  5725.3   93.55
  5981.4   96.85
#Mann= 5 , 1 , 0
 3842.00       1       0  4799.9    0.14       0  4987.1   0.043       0
  5012.8    0.14       0  5105.9       1       0
Bank Sta=4987.10,5012.80
Exp/Cntr=0.3,0.1

Type RM Length L Ch R = 1 ,4908.8,1308.2,1308.2,1308.2
BEGIN DESCRIPTION:
White Swamp 8.0
END DESCRIPTION:
#Sta/Elev= 30
  3329.8   96.29  3629.8      91  3679.8    92.9  3759.8   90.49  3979.8   89.12
  4099.8   90.33  4129.8    89.3  4149.8   86.59  4169.8   85.36  4299.8   81.87
  4339.8   82.24  4359.8   80.73  4379.8   77.83  4679.8   77.77  4719.9   77.11
  4749.8   78.03  4919.8   78.28  4987.2   77.09  4988.7   74.09  5011.4   74.09
  5012.9   77.09  5051.9   78.12  5081.9   80.55  5125.9   85.46  5241.9    87.1
  5371.9   82.74  5451.9   84.02  5531.9   87.46  5721.9   89.18  5880.8   92.99
#Mann= 5 , 1 , 0
 3329.80       1       0  4719.9    0.14       0  4987.2   0.043       0
  5012.9    0.14       0  5125.9       1       0
Bank Sta=4987.20,5012.90
Exp/Cntr=0.3,0.1