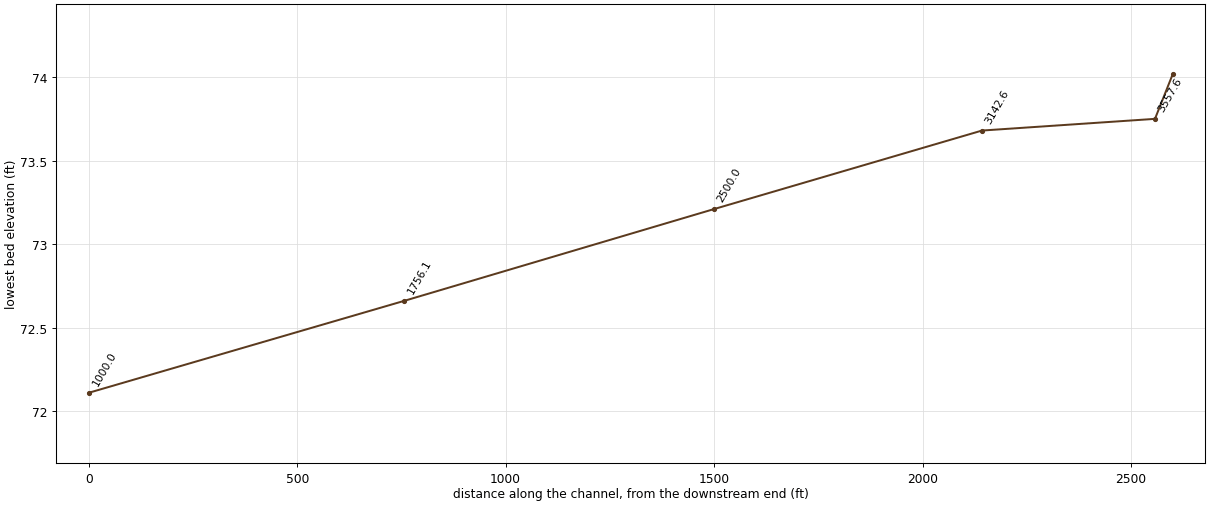
HEC-RAS study 020522_white_swamp.prj: White Swamp

--- 020522_white_swamp.g01 (geometry) --- (continued)

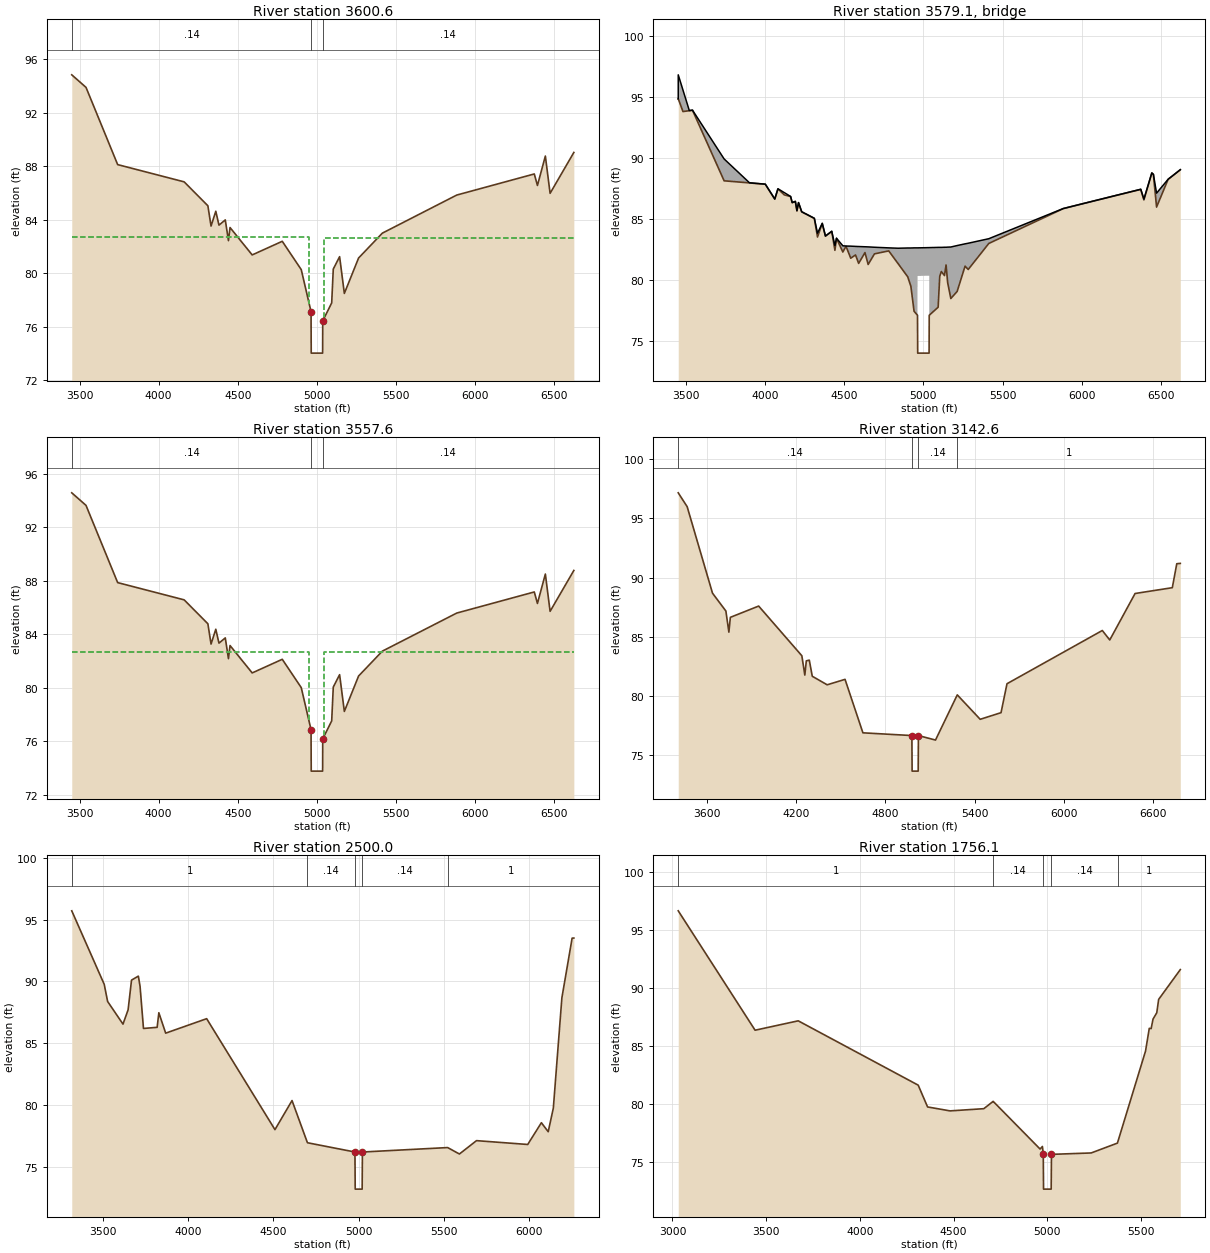
Type RM Length L Ch R = 1 ,3600.6,43,43,43
BEGIN DESCRIPTION:
Upstream Section of Bridge/Culvert/Weir
END DESCRIPTION:
#Sta/Elev= 30
    3451   94.85    3541   93.91    3741   88.13    4161   86.84    4311   85.05
    4331   83.53    4361   84.64    4381    83.6    4421   83.99    4441   82.44
    4451   83.42    4591   81.37    4781   82.39    4901   80.27  4962.8   77.12
    4964   74.02    5036   74.02  5036.7   76.43  5093.3   77.78  5103.3   80.31
  5143.3   81.24  5173.3   78.49  5263.3   81.14  5413.3      83  5883.3   85.85
  6373.3   87.43  6393.3   86.57  6443.3   88.77  6473.3   85.98  6623.3   89.04
#Mann= 3 , 1 , 0
 3451.00    0.14       0  4962.8   0.043       0  5036.7    0.14       0
#XS Ineff= 2 , 0
       0    4952   82.68    5047       0   82.64
Bank Sta=4962.80,5036.70
Exp/Cntr=0.5,0.3

Type RM Length L Ch R = 3 ,3579.1,,,
BEGIN DESCRIPTION:
Bridgerville Road-TOR
Structure ID: Bridgersville Rd-Bridge
Approximate Survey Structure
END DESCRIPTION:
Bridge Culvert--1,0,-1,-1, 0
Deck Dist Width WeirC Skew NumUp NumDn MinLoCord MaxHiCord MaxSubmerge Is_Ogee
10,23,2.6,, 60, 60,,,0.95,0,1,1,,
    3451  3451.1    3481  3521.1    3541    3741  3901.1    4001    4061    4081
    4161    4171    4191    4201    4211    4231    4311    4331    4361    4381
    4421    4441    4451    4491    4511    4541    4571    4591    4631    4651
    4691    4781  4840.7    4901    4921    4941 4962.91    4963 5036.79  5036.9
    5037  5093.3  5103.3  5113.3  5133.3  5143.3  5153.3  5173.3  5213.3  5263.3
  5283.3  5413.3  5883.3  6373.3  6393.3  6443.3  6453.3  6473.3  6546.3  6623.3
   94.83   96.79   95.54   93.86    93.9    89.9   87.95   87.84   86.62   87.46
   86.83   86.33   86.43   85.66   86.33   85.58   85.04   83.82   84.63   83.59
   83.98   82.81   83.41   82.79   82.77   82.76   82.74   82.73   82.71    82.7
   82.67   82.62   82.59   82.61   82.61   82.62   82.62   82.62   82.64   82.64
   82.64   82.66   82.66   82.66   82.67   82.67   82.68   82.69   82.81   82.95
      83   83.37   85.84   87.42   86.62   88.76   88.64    87.1   88.24   89.02
   94.83   94.83   93.78   93.85   93.89   88.11   87.94   87.83   86.61   87.45
   86.82   86.32   86.42   85.65   86.32   85.57   85.03   83.51   84.62   83.58
   83.97   82.42    83.4   82.28   82.75   81.77   82.04   81.35   82.23   81.26
   82.13   82.37   81.32   80.25   79.47   77.43   76.82   80.32   80.34    77.1
    77.1   77.76   80.29   80.68   80.35   81.22   79.77   78.47   79.05   81.12
   80.85   82.98   85.83   87.41   86.55   88.75   88.63   85.96   88.23   89.02
    3451  3451.1    3481  3521.1    3541    3741  3901.1    4001    4061    4081
    4161    4171    4191    4201    4211    4231    4311    4331    4361    4381
    4421    4441    4451    4491    4511    4541    4571    4591    4631    4651
    4691    4781  4840.7    4901    4921    4941 4962.91    4963 5036.79  5036.9
    5037  5093.3  5103.3  5113.3  5133.3  5143.3  5153.3  5173.3  5213.3  5263.3
  5283.3  5413.3  5883.3  6373.3  6393.3  6443.3  6453.3  6473.3  6546.3  6623.3
   94.83   96.79   95.54   93.86    93.9    89.9   87.95   87.84   86.62   87.46
   86.83   86.33   86.43   85.66   86.33   85.58   85.04   83.82   84.63   83.59
   83.98   82.81   83.41   82.79   82.77   82.76   82.74   82.73   82.71    82.7
   82.67   82.62   82.59   82.61   82.61   82.62   82.62   82.62   82.64   82.64
   82.64   82.66   82.66   82.66   82.67   82.67   82.68   82.69   82.81   82.95
      83   83.37   85.84   87.42   86.62   88.76   88.64    87.1   88.24   89.02
   94.58   94.58   93.53    93.6   93.64   87.86   87.69   87.58   86.36    87.2
   86.57   86.07   86.17    85.4   86.07   85.32   84.78   83.26   84.37   83.33
   83.72   82.17   83.15   82.03    82.5   81.52   81.79    81.1   81.98   81.01
   81.88   82.12   81.07      80   79.22   77.18   76.57   80.07   80.09   76.85
   76.85   77.51   80.04   80.43    80.1   80.97   79.52   78.22    78.8   80.87
    80.6   82.73   85.58   87.16    86.3    88.5   88.38   85.71   87.98   88.77
BR Coef= 1 , 1 , 0 ,1.25, 0 ,,,0.8,0,2,0,
Wspro=,,,, 1 ,,,, 0 ,,,, 0 ,,,,-1 ,-1 ,-1 , 0 , 0 , 0 , 0 , 0
BC Design=,, 0 ,, 0 ,,,,,,
BR U #Sta/Elev= 83
    3451   94.83  3451.1   94.83    3481   93.78  3491.1    93.8  3521.1   93.85
    3541   93.89    3741   88.11  3901.1   87.94  3941.1   87.89  3951.1   87.88
    4001   87.83    4061   86.61    4081   87.45    4121   86.96    4161   86.82
    4171   86.32    4191   86.42  4191.1   86.41    4201   85.65    4211   86.32
    4231   85.57  4251.1   85.43  4261.1   85.37  4301.1    85.1    4311   85.03
  4311.1   85.02    4331   83.51    4361   84.62    4381   83.58  4411.1   83.87
    4421   83.97    4441   82.42    4451    83.4    4491   82.28    4511   82.75
    4541   81.77    4571   82.04    4591   81.35    4631   82.23    4651   81.26
    4691   82.13    4781   82.37  4840.7   81.32    4901   80.25    4921   79.47
    4941   77.43  4962.8    77.1 4962.91   76.82    4963   76.58  4963.1   76.32
    4964      74    5036      74  5036.7   76.41 5036.79   76.72  5036.9    77.1
    5037    77.1  5093.3   77.76  5103.3   80.29  5113.3   80.68  5133.3   80.35
  5143.3   81.22  5153.3   79.77  5168.5   78.78  5173.3   78.47  5213.3   79.05
  5263.3   81.12  5283.3   80.85  5413.3   82.98  5678.5   84.59  5883.3   85.83
  5922.3   85.96  6232.3   86.96  6252.3   87.02  6352.3   87.34  6362.3   87.37
  6373.3   87.41  6393.3   86.55  6443.3   88.75  6453.3   88.63  6473.3   85.96
  6546.3   88.23  6592.3    88.7  6623.3   89.02
BR U #Mann= 3
 3451.00    0.14  4962.8   0.043  5036.7    0.14
BR U Banks=4962.80,5036.70
BR D #Sta/Elev= 83
    3451   94.58  3451.1   94.58    3481   93.53  3491.1   93.55  3521.1    93.6
    3541   93.64    3741   87.86  3901.1   87.69  3941.1   87.64  3951.1   87.63
    4001   87.58    4061   86.36    4081    87.2    4121   86.71    4161   86.57
    4171   86.07    4191   86.17  4191.1   86.16    4201    85.4    4211   86.07
    4231   85.32  4251.1   85.18  4261.1   85.12  4301.1   84.85    4311   84.78
  4311.1   84.77    4331   83.26    4361   84.37    4381   83.33  4411.1   83.62
    4421   83.72    4441   82.17    4451   83.15    4491   82.03    4511    82.5
    4541   81.52    4571   81.79    4591    81.1    4631   81.98    4651   81.01
    4691   81.88    4781   82.12  4840.7   81.07    4901      80    4921   79.22
    4941   77.18  4962.8   76.85 4962.91   76.57    4963   76.33  4963.1   76.07
    4964   73.75    5036   73.75  5036.7   76.16 5036.79   76.47  5036.9   76.85
    5037   76.85  5093.3   77.51  5103.3   80.04  5113.3   80.43  5133.3    80.1
  5143.3   80.97  5153.3   79.52  5168.5   78.53  5173.3   78.22  5213.3    78.8
  5263.3   80.87  5283.3    80.6  5413.3   82.73  5678.5   84.34  5883.3   85.58
  5922.3   85.71  6232.3   86.71  6252.3   86.77  6352.3   87.09  6362.3   87.12
  6373.3   87.16  6393.3    86.3  6443.3    88.5  6453.3   88.38  6473.3   85.71
  6546.3   87.98  6592.3   88.45  6623.3   88.77
BR D #Mann= 3
 3451.00    0.14  4962.8   0.043  5036.7    0.14
BR D Banks=4962.80,5036.70

Type RM Length L Ch R = 1 ,3557.6,415,415,415
BEGIN DESCRIPTION:
Downstream Section of Bridge/Culvert/Weir
END DESCRIPTION:
#Sta/Elev= 30
    3451   94.58    3541   93.64    3741   87.86    4161   86.57    4311   84.78
    4331   83.26    4361   84.37    4381   83.33    4421   83.72    4441   82.17
    4451   83.15    4591    81.1    4781   82.12    4901      80  4962.8   76.85
    4964   73.75    5036   73.75  5036.7   76.16  5093.3   77.51  5103.3   80.04
  5143.3   80.97  5173.3   78.22  5263.3   80.87  5413.3   82.73  5883.3   85.58
  6373.3   87.16  6393.3    86.3  6443.3    88.5  6473.3   85.71  6623.3   88.77
#Mann= 3 , 1 , 0
 3451.00    0.14       0  4962.8   0.043       0  5036.7    0.14       0
#XS Ineff= 2 , 0
       0    4952   82.68    5047       0   82.64
Bank Sta=4962.80,5036.70
Exp/Cntr=0.5,0.3

Type RM Length L Ch R = 1 ,3142.6,642.6,642.6,642.6
BEGIN DESCRIPTION:
White Swamp 6.0
END DESCRIPTION:
#Sta/Elev= 30
  3409.3   97.15  3469.3   95.98  3639.3   88.69  3729.3   87.18  3749.3    85.4
  3759.3   86.65  3949.3    87.6  4239.3   83.41  4259.3   81.78  4269.3   82.98
  4289.3   83.04  4309.3   81.68  4409.3   80.96  4529.3   81.42  4649.3   76.91
  4978.1   76.68  4979.6   73.68  5020.4   73.68  5021.9   76.68  5136.7    76.3
  5282.9   80.11  5436.7   78.05  5576.7   78.61  5616.7   81.05  6256.7   85.54
  6306.7   84.74  6476.7   88.66  6726.7   89.15  6756.7   91.17  6780.4    91.2
#Mann= 4 , 1 , 0
 3409.30    0.14       0  4978.1   0.043       0  5021.9    0.14       0
  5282.9       1       0
Bank Sta=4978.10,5021.90
Exp/Cntr=0.3,0.1

Type RM Length L Ch R = 1 ,2500.0,743.9,743.9,743.9
BEGIN DESCRIPTION:
White Swamp 4.0
END DESCRIPTION:
#Sta/Elev= 30
  3319.6   95.71  3509.6   89.77  3529.6   88.38  3619.6   86.55  3649.6   87.71
  3669.6   90.11  3709.6   90.43  3719.6    89.6  3739.6    86.2  3819.6   86.29
  3829.6   87.47  3869.6   85.82  4109.6   86.99  4509.6   78.02  4609.6   80.37
  4699.9   76.96  4978.1   76.21  4979.6   73.21  5020.3   73.21  5021.8   76.21
  5520.9   76.57    5590   76.05    5690   77.13    5990   76.82    6070   78.58
    6110   77.85    6140   79.76    6190   88.67    6250    93.5  6260.1   93.51
#Mann= 5 , 1 , 0
 3319.60       1       0  4699.9    0.14       0  4978.1   0.043       0
  5021.8    0.14       0  5520.9       1       0
Bank Sta=4978.10,5021.80
Exp/Cntr=0.3,0.1

Type RM Length L Ch R = 1 ,1756.1,756.1,756.1,756.1
BEGIN DESCRIPTION:
White Swamp 2.0
END DESCRIPTION:
#Sta/Elev= 25
    3031   96.67    3441   86.37    3671   87.18    4311   81.63    4361   79.75
    4481   79.41    4661    79.6  4709.9   80.22    4711   80.23    4961   76.12
  4973.6   76.34  4978.1   75.66  4979.6   72.66  5020.3   72.66  5021.8   75.66
  5233.6   75.78  5373.6   76.63  5378.9   76.91  5523.6   84.57  5543.6   86.53
  5553.6   86.51  5563.6   87.33  5583.6   87.88  5593.6   89.03  5709.1    91.6
#Mann= 5 , 1 , 0
 3031.00       1       0  4709.9    0.14       0  4978.1   0.043       0
  5021.8    0.14       0  5378.9       1       0
Bank Sta=4978.10,5021.80
Exp/Cntr=0.3,0.1

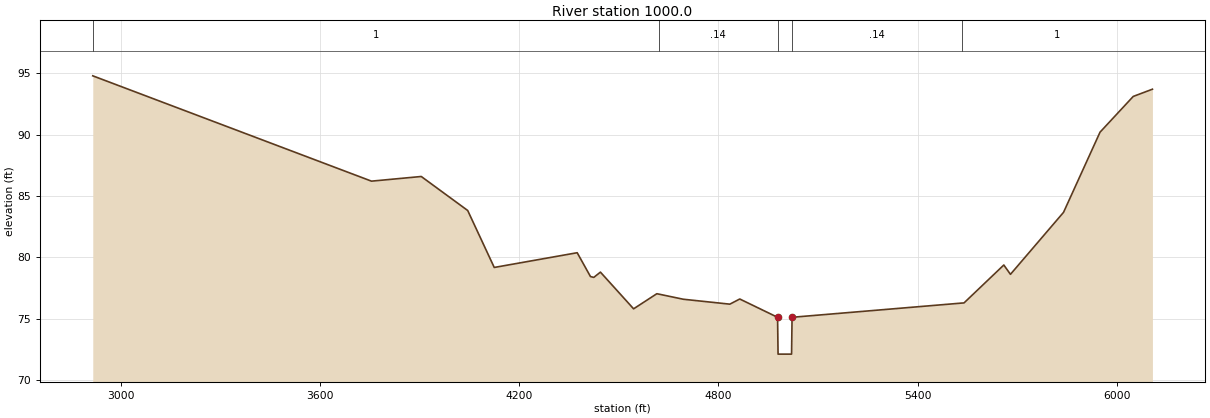
Type RM Length L Ch R = 1 ,1000.0,0,0,0
BEGIN DESCRIPTION:
White Swamp 1.0
END DESCRIPTION:
#Sta/Elev= 27
  2914.2   94.78  3754.2    86.2  3904.2   86.58  4044.2   83.81  4124.2   79.17
  4374.2   80.37  4414.2   78.43  4424.2   78.36  4444.2   78.79  4544.2    75.8
  4614.2   77.03  4619.9      77  4694.2   76.58  4834.2   76.18  4864.2    76.6
  4978.1   75.11  4979.6   72.11  5020.3   72.11  5021.8   75.11  5533.9   76.27
    5540   76.28    5660   79.37    5680   78.61    5840   83.66    5950   90.19
    6050    93.1  6107.9   93.69
#Mann= 5 , 1 , 0
 2914.20       1       0  4619.9    0.14       0  4978.1   0.043       0
  5021.8    0.14       0  5533.9       1       0
Bank Sta=4978.10,5021.80
Exp/Cntr=0.3,0.1

Chan Stop Cuts=-1