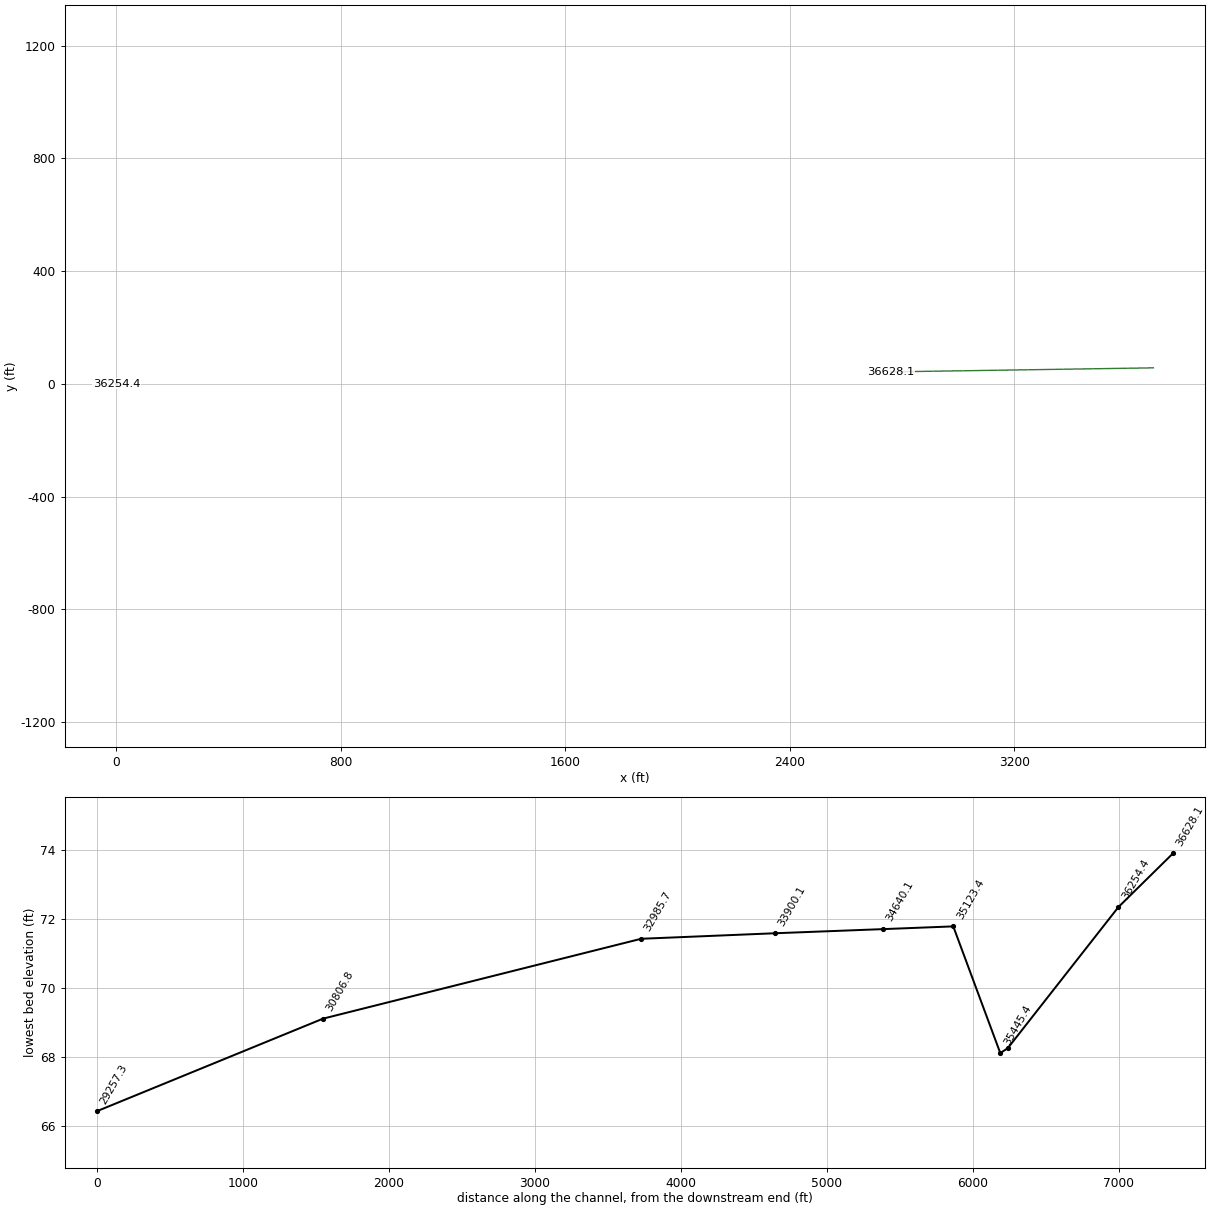
--- Black_Creek_DS_FINAL.prj (project) ---

Proj Title=Black Creek DS
Current Plan=p01
Default Exp/Contr=0.3,0.1
English Units
Geom File=g01
Flow File=f01
Flow File=f02
Plan File=p01
Plan File=p02
Y Axis Title=Elevation
X Axis Title(PF)=Main Channel Distance
X Axis Title(XS)=Station
BEGIN DESCRIPTION:
Model updated with new downstream boundary condition due to tie in with new DTL study performed by G&O
NEUSE RIVER BASIN
Little Contentnea Creek Sub-basin
BLACK CREEK 1
(Flood Hazard, Floodway) Model
Prepared by: Andrew J. Bonner   Date: 11/21/2002
Watershed Concepts
3333 Regency Pkwy
Cary, North Carolina 27511
END DESCRIPTION:
DSS File=dss
DSS Export Rating Curves= 0
DSS Export Rating Curve Sorted= 0
DSS Export Volume Flow Curves= 0
DXF OffsetX= 0
DXF OffsetY= 0
DXF ScaleX= 1
DXF ScaleY= 10

--- Black_Creek_DS_FINAL.p01 (plan) ---

Plan Title=100 Year Single
Program Version=4.00
Short Identifier=Plan01
Geom File=g01
Flow File=f01
Subcritical Flow
K Sum by GR= 0
Std Step Tol= 0.01
Critical Tol= 0.01
Num of Std Step Trials= 20
Max Error Tol= 0.3
Flow Tol Ratio= 0.001
Split Flow NTrial= 30
Split Flow Tol= 0.02
Split Flow Ratio= 0.02
Log Output Level= 0
Friction Slope Method= 1
Unsteady Friction Slope Method= 2
Unsteady Bridges Friction Slope Method= 1
Parabolic Critical Depth
Global Vel Dist= 0 , 0 , 0
Global Log Level= 0
CheckData=True
Encroach Param=-1 ,10,10, 2
Encroach River=Black Ck DS
Encroach Reach=Reach - 1
Encroach Node=36628.1
       1 1063.25 1513.25
Encroach Node=36254.4
       4      .7
Encroach Node=35496.4
       1    4600    5100
Encroach Node=35445.4
       1    4600    5100
Encroach Node=35123.4
       1    4900    5300
Encroach Node=34640.1
       4      .7
Encroach Node=33900.1
       4      .7
Encroach Node=32985.7
       4      .7
Encroach Node=30806.8
       1    4750    5400
Encroach Node=29257.3
       1    4895    5675
Encroach Node=29217.3
       1    4895    5675
Encroach Node=27950.0
       1    4650    5400
Encroach Node=26967.8
       1    4580    5350
Encroach Node=25906.2
       1    4400    5200
Encroach Node=24959.9
       4      .7
Encroach Node=23882.4
       1    4100    5600
Encroach Node=23204.1
       1    3800    5600
Encroach Node=23156.1
       1    3800    5600
Encroach Node=22762.1
       1    4500    5770
Encroach Node=22413.8
       1    4600    5750
Encroach Node=21392.0
       1    4650    5400
Encroach Node=20487.5
       4      .7
Encroach Node=19691.7
       4      .7
Encroach Node=18786.6
       4      .7
Encroach Node=17947.1
       1    4400    5350
Encroach Node=16979.6
       4      .7
Encroach Node=15997.2
       4      .7
Encroach Node=15155.1
       1    4750    5350
Encroach Node=14357.5
       1    4750    5600
Encroach Node=12966.9
       4      .7
Encroach Node=12114.3
       1    4350    5075
Encroach Node=11327.1
       4      .7
Encroach Node=10400.3
       1    4900    6000
Encroach Node=8245.4
       1    4300    5400
Encroach Node=7532.1
       4      .7
Encroach Node=6742.4
       4      .7
Encroach Node=6021.4
       4      .7
Encroach Node=5277.8
       1  239.77 1010.59
Computation Interval=1HOUR
Output Interval=1HOUR
Run HTab= 0
Run UNet= 0
Run PostProcess= 0
Run WQNet= 0
UNET Theta= 1
UNET Theta Warmup= 1
UNET ZTol= 0.02
UNET ZSATol= 0.1
UNET MxIter= 20
UNET MaxInSteps= 20
UNET DtIC= 0
UNET DtMin= 0
UNET MaxCRTS= 20
UNET WFStab= 2
UNET SFStab= 1
UNET WFX= 1
UNET SFX= 1
UNET DSS MLevel= 4
UNET DZMax Abort= 100
UNET Convert EG Bridges=-1
UNET Use Existing IB Tables=-1
UNET Froude Reduction=False
UNET Froude Limit= 1
UNET Froude Power= 10
UNET Time Slicing=0,0, 5
Instantaneous Interval=1HOUR
Write IC File= 0
Echo Input=False
Echo Output=False
Write Detailed= 0
Detailed Automatic Start=False, 10
WQ ULTIMATE=-1
WQ Max Comp Step=1HOUR
WQ Output Interval=15MIN
WQ Output Selected Increments= 0
WQ Output face flow=0
WQ Output face velocity=0
WQ Output face area=0
WQ Output face dispersion=0
WQ Output cell volume=0
WQ Output cell surface area=0
WQ Output cell continuity=0
WQ Output face conc=0
WQ Output face dconc_dx=0
WQ Output face courant=0
WQ Output face peclet=0
WQ Output face adv mass=0
WQ Output face disp mass=0
WQ Output cell mass=0
WQ Output cell source sink temp=0
WQ Output cell source sink nsm=0
WQ Output MaxMinRange=-1
WQ Daily Max Min Mean=-1
WQ Daily Range=0
WQ Daily Time=0
WQ Create Restart=0
WQ Fixed Restart=0
WQ System Summary=False
Sorting and Armoring Iterations= 10
XS Update Threshold= 0.02
Hydraulics Update Threshold= 0.02
Energy Slope Method= 1
Volume Change Method= 0
XS Weighting Method= 0
Number of US Weighted Cross Sections= 1
Number of DS Weighted Cross Sections= 1
Upstream XS Weight=0.25
Main XS Weight=0.5
Downstream XS Weight=0.25
Number of DS XS's Weighted with US Boundary= 1
Upstream Boundary Weight= 1
Weight of XSs Associated with US Boundary= 0
Number of US XS's Weighted with DS Boundary= 1
Downstream Boundary Weight= 0.5
Weight of XSs Associated with DS Boundary= 0.5
Sediment Output Level= 4
Mass or Volume Output= 0
Output Increment Type= 1
Profile and TS Output Increment= 10
XS Output Flag= 0
XS Output Increment= 10
Disregard all LS=0
Disregard all Conn=0
Disregard all Breaches=0
Disregard all Pumps=0

--- Black_Creek_DS_FINAL.p02 (plan) ---

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Plan Title=Multi_Profile
Short Identifier=Multi_Profil
Geom File=g01
Flow File=f02
BEGIN DESCRIPTION:
Multi Profile Run with 10, 25, 50, 500 and future conditions.
END DESCRIPTION:
DSS File=dss

--- Black_Creek_DS_FINAL.f01 (steady flow) ---

Flow Title= 100 Year Single
Program Version=4.00
Number of Profiles= 2
Profile Names=100-Year,AFW
River Rch & RM=Black Ck DS,Reach - 1       ,36628.1
    7429    7429
River Rch & RM=Black Ck DS,Reach - 1       ,30806.8
    7487    7487
River Rch & RM=Black Ck DS,Reach - 1       ,29257.3
   11630   11630
River Rch & RM=Black Ck DS,Reach - 1       ,23882.4
   11695   11695
River Rch & RM=Black Ck DS,Reach - 1       ,21392
   11821   11821
River Rch & RM=Black Ck DS,Reach - 1       ,15997.2
   12035   12035
River Rch & RM=Black Ck DS,Reach - 1       ,12114.3
   12285   12285
River Rch & RM=Black Ck DS,Reach - 1       ,8245.4
   13344   13344
Boundary for River Rch & Prof#=Black Ck DS,Reach - 1       , 1
Up Type= 0
Dn Type= 1
Dn Known WS=67.45
Boundary for River Rch & Prof#=Black Ck DS,Reach - 1       , 2
Up Type= 0
Dn Type= 1
Dn Known WS=68.39
DSS Import GetInterval= 0
DSS Import GetPeak= 0
DSS Import FillOption= 0

--- Black_Creek_DS_FINAL.f02 (steady flow) ---

Flow Title=Multi_Profile
Program Version=4.00
Number of Profiles= 7
Profile Names=10yr,25yr,50yr,500yr,100yr-10%,100yr-20%,100yr-35%
River Rch & RM=Black Ck DS,Reach - 1       ,36628.1
    3816    5109    6228   10746    7560    9690   11800
River Rch & RM=Black Ck DS,Reach - 1       ,30806.8
    3848    5150    6278   10828    7620    9760   11900
River Rch & RM=Black Ck DS,Reach - 1       ,29257.3
    6135    8113    9820   16583   11600   14800   18100
River Rch & RM=Black Ck DS,Reach - 1       ,23882.4
    6171    8160    9876   16674   11600   14900   18200
River Rch & RM=Black Ck DS,Reach - 1       ,21392.0
    6242    8251    9984   16847   11700   15100   18400
River Rch & RM=Black Ck DS,Reach - 1       ,15997.2
    6362    8406   10168   17143   11900   15300   18700
River Rch & RM=Black Ck DS,Reach - 1       ,12114.3
    6502    8586   10382   17488   12200   15600   19100
River Rch & RM=Black Ck DS,Reach - 1       ,8245.4
    7097    9351   11292   18945   13200   16900   20600
Boundary for River Rch & Prof#=Black Ck DS,Reach - 1       , 1
Up Type= 0
Dn Type= 1
Dn Known WS=65.33
Boundary for River Rch & Prof#=Black Ck DS,Reach - 1       , 2
Up Type= 0
Dn Type= 1
Dn Known WS=66.17
Boundary for River Rch & Prof#=Black Ck DS,Reach - 1       , 3
Up Type= 0
Dn Type= 1
Dn Known WS=66.83
Boundary for River Rch & Prof#=Black Ck DS,Reach - 1       , 4
Up Type= 0
Dn Type= 1
Dn Known WS=68.72
Boundary for River Rch & Prof#=Black Ck DS,Reach - 1       , 5
Up Type= 0
Dn Type= 1
Dn Known WS=67.41
Boundary for River Rch & Prof#=Black Ck DS,Reach - 1       , 6
Up Type= 0
Dn Type= 1
Dn Known WS=68.29
Boundary for River Rch & Prof#=Black Ck DS,Reach - 1       , 7
Up Type= 0
Dn Type= 1
Dn Known WS=69.06
DSS Import GetInterval= 0
DSS Import GetPeak= 0
DSS Import FillOption= 0

--- Black_Creek_DS_FINAL.g01 (geometry) ---

Geom Title=Geom 01 by CodeH2 for Windows
Program Version=3.13

River Reach=Black Ck DS     ,Reach - 1
Reach XY= 30
        .0943041        .4528867        .1156398        .3866496
        .1169563        .3206682        .1742718        .3191322
        .1770691        .2860045        .2036151        .2569901
        .2074031        .2309836        .2658583        .2026189
        .3069662        .2019614        .3535004        .1891355
        .3855645        .1605246        .4268903        .1495233
        .4620053        .1135191        .4862304        .1030738
        .5000093        .1057405         .530902        .1350771
        .5560158        .1421893        .6720285        .1541907
        .7046987        .1473008        .7133665        .1593022
        .7360355        .1444118        .7409251        .1286322
        .7691503        .1132972        .7782623         .115964
          .79782        .0857386        .8184892        .0732926
        .8427139        .0850717        .8818294        .1321881
        .9073878        .1410778        .9434124        .1357421

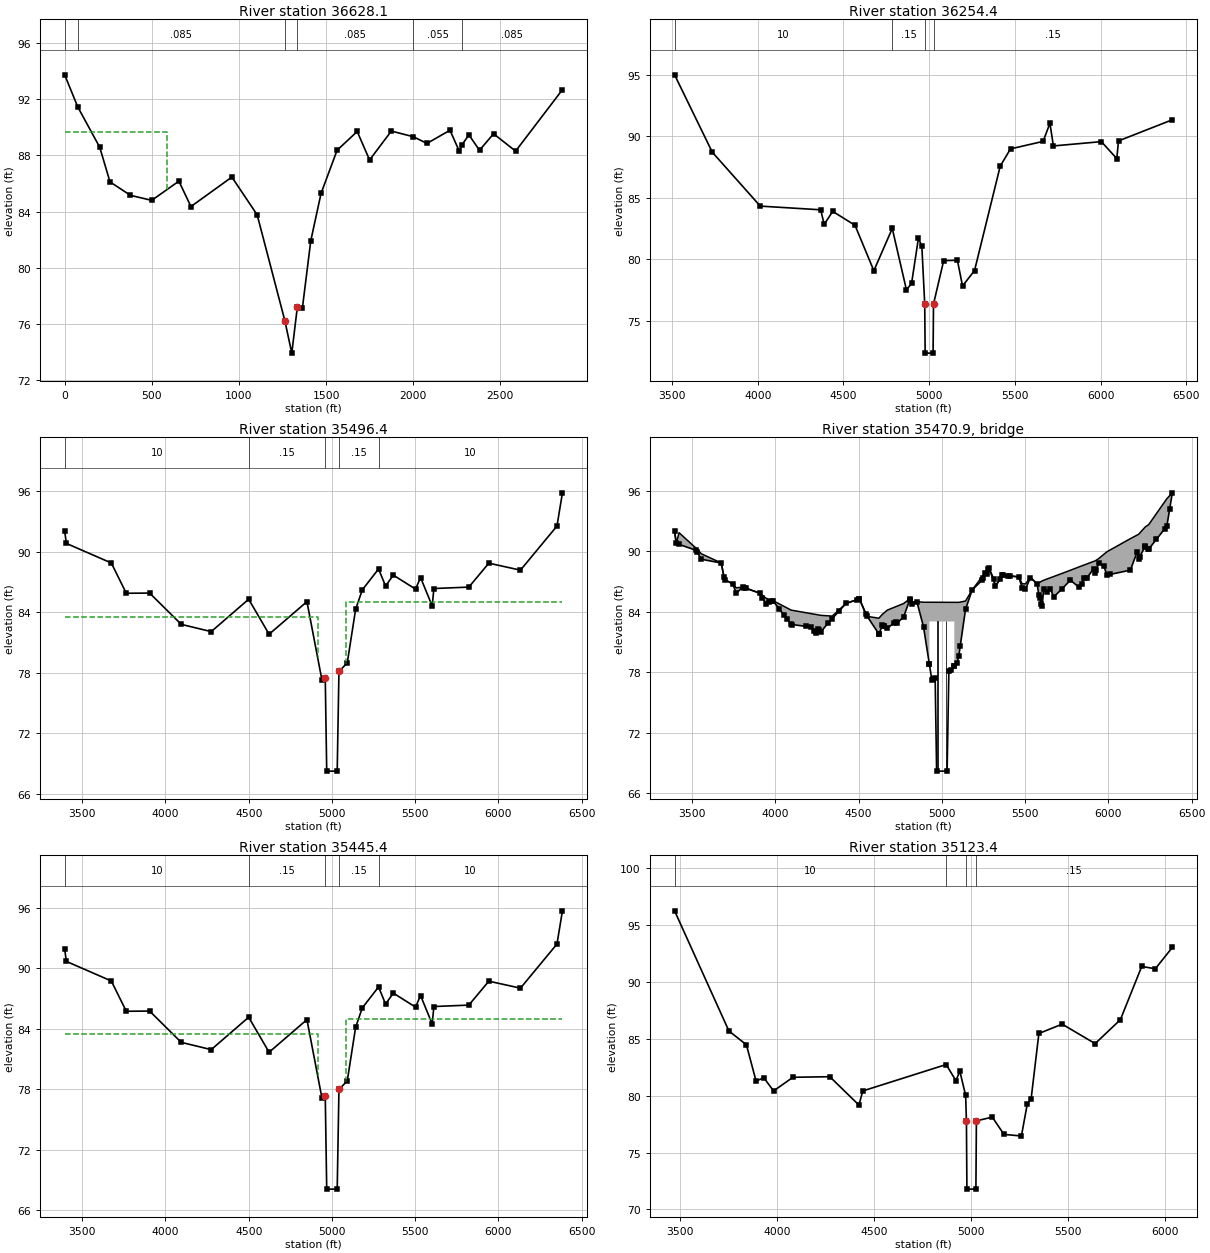
Type RM Length L Ch R = 1 ,36628.1 ,373.7,373.7,373.7
BEGIN DESCRIPTION:
Black Creek DS 38.0 (Tie-in w/new detailed study)
END DESCRIPTION:
XS GIS Cut Line= 2
    3696.3050181      56.9165032    2760.3386063      42.6241054
#Sta/Elev= 30
       0   93.75   75.12   91.46  201.06   88.59  259.93   86.12  377.16   85.16
  499.44    84.8  655.39   86.17  724.49   84.36  959.36   86.46 1104.56   83.77
 1263.23   76.23  1303.2   73.91 1335.39   77.22  1363.9    77.1 1412.07   81.91
 1470.99   85.29 1563.03   88.37 1678.56   89.71  1749.7   87.68 1874.42   89.74
 2000.27   89.34 2078.75   88.86 2211.11    89.8 2264.53    88.3 2278.19   88.73
 2319.58   89.47 2380.46   88.37 2461.06   89.55 2587.57   88.31  2856.3   92.69
#Mann= 6 ,-1 , 0
       0    .045       0   75.12    .085       0 1263.23     .05       0
 1335.39    .085       0 2000.27    .055       0 2278.19    .085       0
#XS Ineff= 2 , 0
       0     586    89.7 1678.56       0   89.71
Permanent Ineff=
       F       F
Bank Sta=1263.23,1335.39
Exp/Cntr=0.3,0.1

Type RM Length L Ch R = 1 ,36254.4 ,758,758,758
BEGIN DESCRIPTION:
Black Creek DS 37.0
END DESCRIPTION:
XS GIS Cut Line= 4
        .1575427         .460344        .1302349        .4514435
          .10254        .4418729             .05        .4229914
#Sta/Elev= 30
  3514.9   95.01  3734.9   88.71  4014.9   84.32  4367.5   84.02  4387.5   82.83
  4437.5   83.89  4567.5   82.76  4677.5   79.06  4784.9    82.5  4867.5   77.51
  4897.5   78.02  4937.5    81.7  4957.5   81.07  4974.3   76.35  4976.8   72.35
  5023.1   72.35  5025.6   76.35  5084.9   79.88  5164.9   79.91  5194.9   77.82
  5264.9   79.07  5414.9   87.58  5474.9   88.98  5664.9   89.59  5704.9   91.07
  5724.9   89.22  6004.9   89.57  6094.9   88.19  6104.9   89.63    6419   91.35
#Mann= 4 , 1 , 0
  3514.9      10       0  4784.9     .15       0  4974.3     .05       0
  5025.6     .15       0
Bank Sta=4974.3,5025.6
Exp/Cntr=0.5,0.3

Type RM Length L Ch R = 1 ,35496.4 ,51,51,51
BEGIN DESCRIPTION:
Upstream Section of Bridge/Culvert/Weir
END DESCRIPTION:
XS GIS Cut Line= 6
        .1589677        .4555734        .1217911        .4182896
        .1171679         .415898        .1090973        .4137742
        .0995161        .4121605        .0559402        .4030334
#Sta/Elev= 30
    3395   92.03    3405   90.81    3675   88.87    3765   85.87    3905   85.89
    4095   82.79    4275   82.07  4499.9   85.28  4622.5   81.81  4849.8   85.04
  4939.8   77.28  4959.8   77.44  4968.5   68.25  5031.5   68.25    5042   78.12
    5092   78.98    5142   84.27    5182    86.2  5279.9   88.28    5322   86.58
  5368.3   87.67    5502   86.28    5532   87.43    5602   84.61    5612   86.34
    5822   86.48    5942   88.85    6132   88.16  6351.2   92.53    6384   95.82
#Mann= 5 , 1 , 0
    3395      10       0  4499.9     .15       0  4959.8     .05       0
    5042     .15       0  5279.9      10       0
#XS Ineff= 2 , 0
       0    4914    83.5    5086       0      85
Permanent Ineff=
       F       F
Bank Sta=4959.8,5042
Exp/Cntr=0.5,0.3

Type RM Length L Ch R = 3 ,35470.9 ,,,
BEGIN DESCRIPTION:
Church Loop Rd-TOR
Structure ID: Church Loop Rd
Approximate Survey Structure
END DESCRIPTION:
Bridge Culvert--1,0,-1,-1, 0
Deck Dist Width WeirC Skew NumUp NumDn MinLoCord MaxHiCord MaxSubmerge Is_Ogee
10,31,2.6,0, 60, 60, , , 0.95, 0, 1,1,,
    3395    3405  3421.9    3525    3555    3675    3695    3745    3765    3805
    3905    3945    3985    4095    4275  4341.9    4425    4505  4551.9  4621.9
  4642.5  4672.5  4769.8  4809.8  4819.8  4849.8  4889.8 4924.91    4925 5074.89
    5075    5102    5142    5182    5282    5322  5368.3    5462    5482    5502
    5532    5572    5602    5612    5652    5672    5772    5822    5912    5922
    5942    5972    5992    6132    6172    6182    6222    6242  6351.2    6384
   91.98   90.76   91.82   90.27   89.74   88.82   87.18   86.74   86.36   86.43
   85.84   85.32    85.1   84.15   83.63   83.56   84.82   85.26   83.53   83.35
   83.73   84.15    84.8   85.29   84.93   84.99   84.93   84.93   84.93   84.92
   84.92   84.92   85.05   86.15   88.35   86.53   87.62   87.44   86.76   86.75
   87.38   86.76   87.04   87.11   87.36   87.48    88.1   88.42   88.98   89.04
   89.26   89.67   89.94   91.23   91.58   91.67    92.4   92.62   95.19   95.77
   91.98   90.76   90.66   90.07   89.19   88.82   87.18   86.74   85.82   86.43
   85.84   84.77   85.09   82.74   82.02   83.32   84.82   85.26   83.53   81.78
   82.67   82.34   83.45   85.29   84.78   84.99    82.5    78.8   83.03   83.02
   78.64   79.63   84.22   86.15   88.35   86.53   87.62   87.44   86.36   86.23
   87.38   86.76   84.56   86.29   86.23   85.46   87.12   86.43   88.26   87.87
    88.8   88.52   87.62   88.11   89.87   89.25   90.49   90.19   92.48   95.77
    3395    3405  3421.9    3525    3555    3675    3695    3745    3765    3805
    3905    3945    3985    4095    4275  4341.9    4425    4505  4551.9  4621.9
  4642.5  4672.5  4769.8  4809.8  4819.8  4849.8  4889.8 4924.91    4925 5074.89
    5075    5102    5142    5182    5282    5322  5368.3    5462    5482    5502
    5532    5572    5602    5612    5652    5672    5772    5822    5912    5922
    5942    5972    5992    6132    6172    6182    6222    6242  6351.2    6384
   91.88   90.66   91.82   90.27   89.74   88.73   87.16   86.65   86.36   86.34
   85.75   85.32    85.1   84.15   83.63   83.56   84.73   85.17   83.44   83.35
   83.73   84.15    84.8    85.2   84.93   84.93   84.93   84.93   84.93   84.92
   84.92   84.92   85.05   86.06   88.26   86.44   87.53   87.35   86.76   86.75
   87.29   86.73   87.04   87.11   87.36   87.48    88.1   88.42   88.98   89.04
   89.26   89.67   89.94   91.23   91.58   91.67    92.4   92.62   95.19   95.67
   91.78   90.56   90.46   89.87   88.99   88.62   86.98   86.54   85.62   86.23
   85.64   84.57   84.89   82.54   81.82   83.12   84.62   85.06   83.33   81.58
   82.47   82.14   83.25   85.09   84.58   84.79    82.3    78.6   82.83   82.82
   78.44   79.43   84.02   85.95   88.15   86.33   87.42   87.24   86.16   86.03
   87.18   86.56   84.36   86.09   86.03   85.26   86.92   86.23   88.06   87.67
    88.6   88.32   87.42   87.91   89.67   89.05   90.29   89.99   92.28   95.57
Pier Skew, UpSta & Num, DnSta & Num=  ,4974, 2 ,4974, 2 , 0 , 0 , 0 ,,
       1       1
    67.2   84.02
       1       1
      67   83.82
Pier Skew, UpSta & Num, DnSta & Num=  ,5026, 2 ,5026, 2 , 0 , 0 , 0 ,,
       1       1
    67.2   84.02
       1       1
      67   83.82
Abutment Skew #Up #Dn= , 2 , 2
  4924.8    4948
   83.03    77.3
  4924.8    4948
   82.83    77.1
Abutment Skew #Up #Dn= , 2 , 2
    5052 5075.09
   78.24   83.02
    5052 5075.09
   78.04   82.82
BR Coef= 1 , 1 , 0 ,1.25, 0 ,,,0.8,0,2,0,
WSPro=,,,, 1 ,,,, 0 ,,,, 0 ,,,,-1 ,-1 ,-1 , 0 , 0 , 0 , 0 , 0
BR U #Sta/Elev= 124
    3395   91.98    3405   90.76  3421.9   90.66    3525   90.07  3531.9   89.87
    3555   89.19    3675   88.82  3691.9   87.43    3695   87.18    3745   86.74
    3765   85.82    3805   86.43  3811.9   86.39  3821.9   86.33    3905   85.84
  3921.9   85.39    3945   84.77  3961.9   84.91  3981.9   85.07    3985   85.09
  4021.9    84.3  4051.9   83.66  4071.9   83.23    4095   82.74  4101.9   82.72
  4181.9   82.54    4215   82.47  4231.9   82.13    4245   81.87    4255   82.31
  4261.9   82.21    4275   82.02    4315   82.83  4341.9   83.32  4381.9   84.04
    4425   84.82  4491.9   85.19  4499.9   85.23    4505   85.26  4542.5   83.77
  4551.9   83.53  4621.9   81.78  4622.5   81.76  4642.5   82.67  4651.9   82.57
  4654.9   82.53  4672.5   82.34  4714.9   82.92  4722.5   83.02  4729.8   82.86
  4769.8   83.45  4807.7   85.19  4809.8   85.29  4819.8   84.78  4849.8   84.99
  4889.8    82.5 4924.91    78.8    4925   78.79  4939.8   77.23    4948    77.3
  4959.8   77.39  4968.5    68.2  5031.5    68.2    5042   78.07    5052   78.24
 5074.89   78.64    5075   78.64    5092   78.93    5102   79.63  5110.5   80.61
    5142   84.22    5182   86.15    5242   87.12  5248.3   87.33    5262   87.79
    5272   87.77  5279.9   88.23    5282   88.35    5312   87.22    5322   86.53
  5348.3   87.25    5362   87.63  5368.3   87.62  5398.3   87.56  5408.3   87.54
    5462   87.44    5482   86.36    5502   86.23    5532   87.38    5572   86.76
    5582   85.65  5588.3   85.31  5598.3   84.76    5602   84.56    5612   86.29
    5632   85.98    5652   86.23    5672   85.46    5722   86.26    5772   87.12
    5822   86.43    5842   86.69    5852   87.33    5872   87.37    5912   88.26
    5922   87.87  5928.3   88.16    5942    88.8    5972   88.52    5992   87.62
  6008.3   87.68    6132   88.11    6172   89.87    6182   89.25  6188.3   89.45
  6218.3   90.38    6222   90.49  6238.3   90.25    6242   90.19  6288.3   91.16
  6338.3   92.21  6351.2   92.48  6368.3    94.2    6384   95.77
BR U #Mann= 5
    3395      10  4499.9     .15  4959.8     .05    5042     .15  5279.9      10
BR U Banks=4959.8,5042
BR D #Sta/Elev= 124
    3395   91.78    3405   90.56  3421.9   90.46    3525   89.87  3531.9   89.67
    3555   88.99    3675   88.62  3691.9   87.23    3695   86.98    3745   86.54
    3765   85.62    3805   86.23  3811.9   86.19  3821.9   86.13    3905   85.64
  3921.9   85.19    3945   84.57  3961.9   84.71  3981.9   84.87    3985   84.89
  4021.9    84.1  4051.9   83.46  4071.9   83.03    4095   82.54  4101.9   82.52
  4181.9   82.34    4215   82.27  4231.9   81.93    4245   81.67    4255   82.11
  4261.9   82.01    4275   81.82    4315   82.63  4341.9   83.12  4381.9   83.84
    4425   84.62  4491.9   84.99  4499.9   85.03    4505   85.06  4542.5   83.57
  4551.9   83.33  4621.9   81.58  4622.5   81.56  4642.5   82.47  4651.9   82.37
  4654.9   82.33  4672.5   82.14  4714.9   82.72  4722.5   82.82  4729.8   82.66
  4769.8   83.25  4807.7   84.99  4809.8   85.09  4819.8   84.58  4849.8   84.79
  4889.8    82.3 4924.91    78.6    4925   78.59  4939.8   77.03    4948    77.1
  4959.8   77.19  4968.5      68  5031.5      68    5042   77.87    5052   78.04
 5074.89   78.44    5075   78.44    5092   78.73    5102   79.43  5110.5   80.41
    5142   84.02    5182   85.95    5242   86.92  5248.3   87.13    5262   87.59
    5272   87.57  5279.9   88.03    5282   88.15    5312   87.02    5322   86.33
  5348.3   87.05    5362   87.43  5368.3   87.42  5398.3   87.36  5408.3   87.34
    5462   87.24    5482   86.16    5502   86.03    5532   87.18    5572   86.56
    5582   85.45  5588.3   85.11  5598.3   84.56    5602   84.36    5612   86.09
    5632   85.78    5652   86.03    5672   85.26    5722   86.06    5772   86.92
    5822   86.23    5842   86.49    5852   87.13    5872   87.17    5912   88.06
    5922   87.67  5928.3   87.96    5942    88.6    5972   88.32    5992   87.42
  6008.3   87.48    6132   87.91    6172   89.67    6182   89.05  6188.3   89.25
  6218.3   90.18    6222   90.29  6238.3   90.05    6242   89.99  6288.3   90.96
  6338.3   92.01  6351.2   92.28  6368.3      94    6384   95.57
BR D #Mann= 5
    3395      10  4499.9     .15  4959.8     .05    5042     .15  5279.9      10
BR D Banks=4959.8,5042
BC Design=,, 0 ,, 0 ,,,,,,
BC HTab HWMax=95.82

Type RM Length L Ch R = 1 ,35445.4 ,322,322,322
BEGIN DESCRIPTION:
Downstream Section of Bridge/Culvert/Weir
END DESCRIPTION:
XS GIS Cut Line= 6
        .1594014        .4536215        .1222248        .4163377
        .1176016        .4139462         .109531        .4118223
        .0999498        .4102087        .0563739        .4010816
#Sta/Elev= 30
    3395   91.89    3405   90.67    3675   88.73    3765   85.73    3905   85.75
    4095   82.65    4275   81.93  4499.9   85.14  4622.5   81.67  4849.8    84.9
  4939.8   77.14  4959.8    77.3  4968.5   68.11  5031.5   68.11    5042   77.98
    5092   78.84    5142   84.13    5182   86.06  5279.9   88.14    5322   86.44
  5368.3   87.53    5502   86.14    5532   87.29    5602   84.47    5612    86.2
    5822   86.34    5942   88.71    6132   88.02  6351.2   92.39    6384   95.68
#Mann= 5 , 1 , 0
    3395      10       0  4499.9     .15       0  4959.8     .05       0
    5042     .15       0  5279.9      10       0
#XS Ineff= 2 , 0
       0    4914    83.5    5086       0      85
Permanent Ineff=
       F       F
Bank Sta=4959.8,5042
Exp/Cntr=0.5,0.3

Type RM Length L Ch R = 1 ,35123.4 ,483.3,483.3,483.3
BEGIN DESCRIPTION:
Black Creek DS 36.0
END DESCRIPTION:
XS GIS Cut Line= 3
         .172461        .4031886        .1126831        .3996722
        .0728312        .3914674
#Sta/Elev= 30
  3470.3   96.25  3750.3   85.69  3840.3   84.48  3890.3   81.29  3930.3   81.58
  3980.3   80.42  4080.3   81.62  4270.3   81.67  4420.3   79.18  4440.3   80.42
  4869.9   82.74  4920.3   81.32  4940.3   82.16  4970.3   80.02  4974.3   77.79
  4976.8   71.79  5023.2   71.79  5025.7   77.79  5107.7   78.12  5167.7    76.6
  5257.7   76.46  5287.7   79.25  5307.7   79.72  5347.7   85.47  5467.7   86.29
  5637.7   84.58  5767.7   86.68  5877.7   91.36  5947.7   91.16  6035.5   93.03
#Mann= 4 , 1 , 0
  3470.3      10       0  4869.9     .15       0  4974.3     .05       0
  5025.7     .15       0
Bank Sta=4974.3,5025.7
Exp/Cntr=0.3,0.1

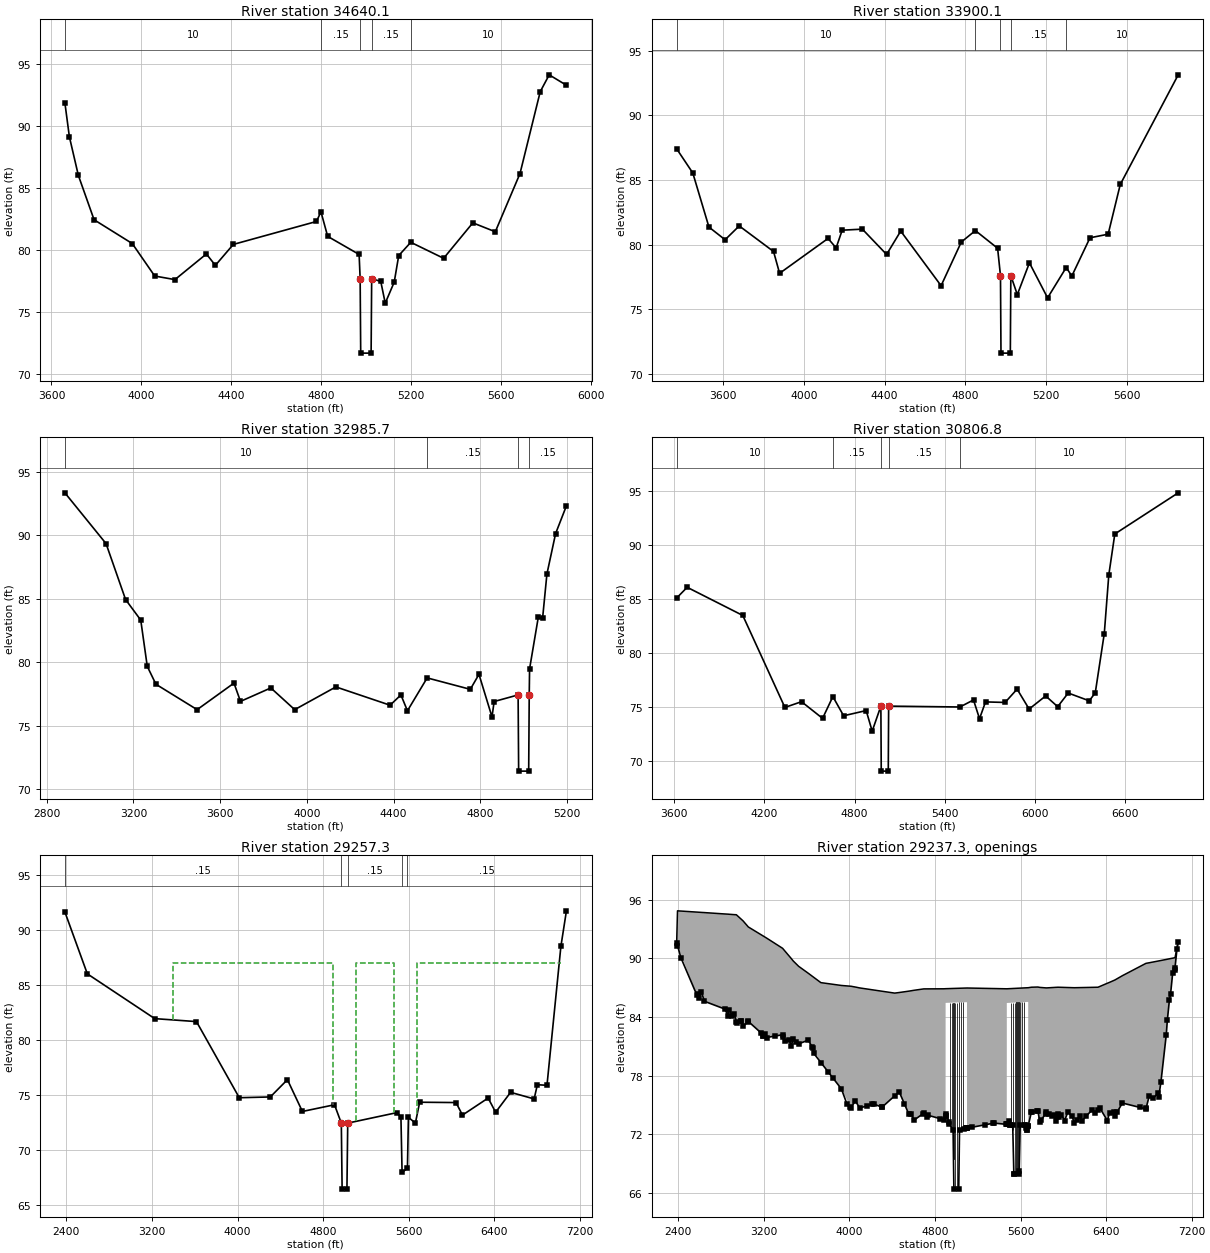
Type RM Length L Ch R = 1 ,34640.1 ,740,740,740
BEGIN DESCRIPTION:
Black Creek DS 35.0
END DESCRIPTION:
XS GIS Cut Line= 3
        .1677725        .3891232        .1159863        .3811994
         .081036         .377402
#Sta/Elev= 30
  3659.8   91.91  3679.8   89.17  3719.8   86.05  3789.8   82.47  3959.8   80.55
  4059.8   77.93  4149.8   77.64  4289.8   79.71  4329.8   78.79  4409.8   80.48
  4779.8   82.33  4799.9   83.11  4829.8   81.13  4969.8   79.67  4974.4   77.71
  4976.9   71.71  5023.2   71.71  5025.7   77.71  5066.1    77.5  5086.1   75.74
  5126.1   77.44  5146.1   79.58  5199.9   80.65  5346.1   79.36  5476.1   82.22
  5576.1    81.5  5686.1    86.2  5776.1    92.8  5816.1   94.16  5892.8   93.32
#Mann= 5 , 1 , 0
  3659.8      10       0  4799.9     .15       0  4974.4     .05       0
  5025.7     .15       0  5199.9      10       0
Bank Sta=4974.4,5025.7
Exp/Cntr=0.3,0.1

Type RM Length L Ch R = 1 ,33900.1 ,914.4,914.4,914.4
BEGIN DESCRIPTION:
Black Creek DS 34.0
END DESCRIPTION:
XS GIS Cut Line= 3
        .1806658        .3680251        .1173715        .3551318
        .0845523        .3551318
#Sta/Elev= 30
  3370.1   87.41  3450.1   85.54  3530.1   81.35  3610.1   80.37  3680.1   81.44
  3850.1   79.46  3880.1   77.77  4120.1   80.47  4160.1   79.74  4190.1   81.11
  4290.1   81.19  4410.1   79.23  4480.1   81.04  4680.1   76.81  4780.1   80.19
  4849.9   81.08  4960.1   79.71  4974.3   77.59  4976.8   71.59  5023.1   71.59
  5025.6   77.59  5057.7   76.12  5117.7   78.58  5207.7   75.87  5299.9   78.22
  5327.7   77.56  5417.7   80.52  5507.7    80.8  5567.7   84.65  5854.8   93.14
#Mann= 5 , 1 , 0
  3370.1      10       0  4849.9     .15       0  4974.3     .05       0
  5025.6     .15       0  5299.9      10       0
Bank Sta=4974.3,5025.6
Exp/Cntr=0.3,0.1

Type RM Length L Ch R = 1 ,32985.7 ,2178.9,2178.9,2178.9
BEGIN DESCRIPTION:
Black Creek DS 33.0
END DESCRIPTION:
XS GIS Cut Line= 3
        .1923869        .3551318        .1150273        .3223126
        .1033062        .3211405
#Sta/Elev= 30
  2883.9   93.34  3073.9   89.34  3163.9   84.94  3233.9   83.32  3263.9   79.68
  3303.9   78.27  3493.9   76.27  3663.9   78.36  3693.9   76.92  3833.9   77.98
  3943.9   76.27  4133.9   78.06  4383.9   76.62  4433.9   77.43  4463.9   76.18
  4554.9   78.77  4753.9   77.87  4793.9   79.05  4853.9    75.7  4863.9   76.91
  4974.4   77.43  4976.9   71.43  5023.2   71.43  5025.7   77.43  5027.3   79.48
  5067.3   83.53  5087.3   83.46  5107.3   86.95  5147.3   90.13  5197.3   92.32
#Mann= 4 , 1 , 0
  2883.9      10       0  4554.9     .15       0  4974.4     .05       0
  5025.7     .15       0
Bank Sta=4974.4,5025.7
Exp/Cntr=0.3,0.1

Type RM Length L Ch R = 1 ,30806.8 ,1549.5,1549.5,1549.5
BEGIN DESCRIPTION:
Black Creek DS 32.0
END DESCRIPTION:
XS GIS Cut Line= 4
        .2111408        .3422386        .1947312        .3141078
        .1767426        .3026528        .1009619        .2894934
#Sta/Elev= 30
  3615.7   85.09  3685.7   86.08  4055.7   83.48  4335.7   74.99  4446.4   75.52
  4586.4   73.98  4654.9   75.99  4726.4   74.22  4876.4    74.7  4916.4    72.8
  4974.2   75.11  4976.7   69.11  5023.4   69.11  5025.9   75.11  5499.9   75.03
  5590.4   75.68  5630.4   73.95  5670.4    75.5  5800.4   75.45  5880.4   76.68
  5960.4   74.84  6070.4   76.05  6150.4   75.06  6220.4   76.32  6360.4    75.6
  6400.4   76.34  6460.4   81.81  6490.4   87.22  6530.4      91  6952.2    94.8
#Mann= 5 , 1 , 0
  3615.7      10       0  4654.9     .15       0  4974.2     .05       0
  5025.9     .15       0  5499.9      10       0
Bank Sta=4974.2,5025.9
Exp/Cntr=0.5,0.3

Type RM Length L Ch R = 1 ,29257.3 ,40,40,40
BEGIN DESCRIPTION:
Upstream Section of Bridge/Culvert/Weir
END DESCRIPTION:
XS GIS Cut Line= 3
        .2273785        .3370121        .1972122        .2620955
        .1706263        .1960882
#Sta/Elev= 30
  2386.3   91.62  2596.3   85.99  3226.3   81.92  3616.3   81.65  4016.3   74.73
  4306.3    74.8  4466.3   76.37  4606.3   73.48  4906.3   74.09    4970   72.42
  4977.5   66.42  5022.5   66.42    5030   72.42  5492.2   73.38  5527.2   72.95
  5537.9   67.95  5587.9    68.3  5597.2   72.95  5662.2   72.42  5702.2   74.32
  6042.2   74.29  6102.2   73.15  6342.2    74.7  6412.2   73.41  6552.2   75.22
  6772.2   74.62  6802.2   75.91  6892.2   75.86  7022.2   88.49    7074   91.72
#Mann= 5 , 1 , 0
  2386.3     .15       0    4970     .05       0    5030     .15       0
  5537.9     .05       0  5587.9     .15       0
#XS Ineff= 3 ,-1
    3400    4890      87    5110    5460      87    5680    7020      87
Permanent Ineff=
       F       F       F
Bank Sta=4970,5030
Exp/Cntr=0.5,0.3

Type RM Length L Ch R = 4 ,29237.3 ,,,
BEGIN DESCRIPTION:
Railroad-TOR
Structure ID: Railroad
Approximate Survey Structure
END DESCRIPTION:
Bridge Culvert--1,0,-1,-1, 0
Deck Dist Width WeirC Skew NumUp NumDn MinLoCord MaxHiCord MaxSubmerge Is_Ogee
10,20,2.6,0, 60, 60, , , 0.95, 0, 1,1,,
  2386.3  2394.2  2576.3  2616.3  2646.3  2836.3  2866.3  2876.3  2926.3  2944.2
  3006.3  3056.3  3226.3  3376.3  3456.3  3476.3  3526.3  3616.3  3734.2  3926.3
  4016.3  4056.3  4096.3  4306.3  4424.2  4466.3  4556.3  4606.3  4696.3  4886.3
 4899.91    4900 5099.89    5100 5471.91    5472 5671.89    5672  5702.2  5762.2
  5782.2  5842.2  5932.2  5952.2  6012.2  6042.2  6102.2  6324.2  6412.2  6432.2
  6482.2  6552.2  6772.2  6802.2  6892.2  6962.2  6992.2  7022.2  7044.2    7074
    91.6   94.85   94.72   94.69   94.67   94.53   94.51    94.5   94.46   94.45
   93.83    93.2   92.07   91.02   89.99   89.72   89.18   88.47   87.51   87.22
   87.14   87.06   86.97   86.63   86.44    86.5   86.64   86.73   86.87   86.88
   86.89   86.89   86.96   86.96   86.88   86.88   86.99   86.99   87.04   87.06
   87.02   86.97   87.03   87.04   87.02   87.01   86.99   87.04   87.45   87.54
   87.78   88.22   89.48   89.54   89.73   89.88   89.95   90.01   90.06    91.7
    91.6   91.29   86.21   86.56    85.6   84.81   84.14   84.76   84.26   83.49
   83.03   83.54    81.9   82.18   81.06   81.71   81.25   81.63   79.34   76.64
   74.71   75.44   74.69   74.78   75.94   76.35   74.06   73.46   74.17   73.49
   73.88   85.44   85.51   72.63   73.02   85.43   85.54   72.87    74.3   74.37
   73.24   74.27    73.4   74.06   73.41   74.27   73.13   74.51   73.39   74.23
   73.89    75.2    74.6   75.89   75.84   82.17   85.78   88.47   89.04    91.7
  2386.3  2394.2  2576.3  2616.3  2646.3  2836.3  2866.3  2876.3  2926.3  2944.2
  3006.3  3056.3  3226.3  3376.3  3456.3  3476.3  3526.3  3616.3  3734.2  3926.3
  4016.3  4056.3  4096.3  4306.3  4424.2  4466.3  4556.3  4606.3  4696.3  4886.3
 4899.91    4900 5099.89    5100 5471.91    5472 5671.89    5672  5702.2  5762.2
  5782.2  5842.2  5932.2  5952.2  6012.2  6042.2  6102.2  6324.2  6412.2  6432.2
  6482.2  6552.2  6772.2  6802.2  6892.2  6962.2  6992.2  7022.2  7042.2    7074
   91.55   94.85   94.72   94.69   94.67   94.53   94.51    94.5   94.46   94.45
   93.83    93.2   92.07   91.02   89.99   89.72   89.18   88.47   87.51   87.22
   87.14   87.06   86.97   86.63   86.44    86.5   86.64   86.73   86.87   86.88
   86.89   86.89   86.96   86.96   86.88   86.88   86.99   86.99   87.04   87.06
   87.02   86.97   87.03   87.04   87.02   87.01   86.99   87.04   87.45   87.54
   87.78   88.22   89.48   89.54   89.73   89.88   89.95   90.01   90.06   91.65
    91.5   91.19   86.11   86.46    85.5   84.71   84.04   84.66   84.16   83.39
   82.93   83.44    81.8   82.08   80.96   81.61   81.15   81.53   79.24   76.54
   74.61   75.34   74.59   74.68   75.84   76.25   73.96   73.36   74.07   73.39
   73.78   85.34   85.41   72.53   72.92   85.33   85.44   72.77    74.2   74.27
   73.14   74.17    73.3   73.96   73.31   74.17   73.03   74.41   73.29   74.13
   73.79    75.1    74.5   75.79   75.74   82.07   85.68   88.37   88.73    91.6
Pier Skew, UpSta & Num, DnSta & Num=  ,4938.7, 2 ,4938.7, 2 , 0 , 0 , 0 ,,
     1.5     1.5
   72.01   86.45
     1.5     1.5
   71.91   86.35
Pier Skew, UpSta & Num, DnSta & Num=  ,4956.2, 2 ,4956.2, 2 , 0 , 0 , 0 ,,
     1.5     1.5
   71.66   86.46
     1.5     1.5
   71.56   86.36
Pier Skew, UpSta & Num, DnSta & Num=  ,4973.7, 2 ,4973.7, 2 , 0 , 0 , 0 ,,
     1.5     1.5
   67.84   86.47
     1.5     1.5
   67.74   86.37
Pier Skew, UpSta & Num, DnSta & Num=  ,4991.2, 2 ,4991.2, 2 , 0 , 0 , 0 ,,
     1.5     1.5
    65.4   86.47
     1.5     1.5
    65.3   86.37
Pier Skew, UpSta & Num, DnSta & Num=  ,5008.7, 2 ,5008.7, 2 , 0 , 0 , 0 ,,
     1.5     1.5
    65.4   86.48
     1.5     1.5
    65.3   86.38
Pier Skew, UpSta & Num, DnSta & Num=  ,5026.2, 2 ,5026.2, 2 , 0 , 0 , 0 ,,
     1.5     1.5
   67.76   86.48
     1.5     1.5
   67.66   86.38
Pier Skew, UpSta & Num, DnSta & Num=  ,5043.7, 2 ,5043.7, 2 , 0 , 0 , 0 ,,
     1.5     1.5
   71.45   86.49
     1.5     1.5
   71.35   86.39
Pier Skew, UpSta & Num, DnSta & Num=  ,5061.2, 2 ,5061.2, 2 , 0 , 0 , 0 ,,
     1.5     1.5
   71.51    86.5
     1.5     1.5
   71.41    86.4
Pier Skew, UpSta & Num, DnSta & Num=  ,5510.7, 2 ,5510.7, 2 , 0 , 0 , 0 ,,
     1.5     1.5
   71.93   86.45
     1.5     1.5
   71.83   86.35
Pier Skew, UpSta & Num, DnSta & Num=  ,5528.2, 2 ,5528.2, 2 , 0 , 0 , 0 ,,
     1.5     1.5
   71.05   86.46
     1.5     1.5
   70.95   86.36
Pier Skew, UpSta & Num, DnSta & Num=  ,5545.7, 2 ,5545.7, 2 , 0 , 0 , 0 ,,
     1.5     1.5
   66.93   86.47
     1.5     1.5
   66.83   86.37
Pier Skew, UpSta & Num, DnSta & Num=  ,5563.2, 2 ,5563.2, 2 , 0 , 0 , 0 ,,
     1.5     1.5
   66.93   86.48
     1.5     1.5
   66.83   86.38
Pier Skew, UpSta & Num, DnSta & Num=  ,5580.7, 2 ,5580.7, 2 , 0 , 0 , 0 ,,
     1.5     1.5
   66.93   86.49
     1.5     1.5
   66.83   86.39
Pier Skew, UpSta & Num, DnSta & Num=  ,5598.2, 2 ,5598.2, 2 , 0 , 0 , 0 ,,
     1.5     1.5
   71.93    86.5
     1.5     1.5
   71.83    86.4
Pier Skew, UpSta & Num, DnSta & Num=  ,5615.7, 2 ,5615.7, 2 , 0 , 0 , 0 ,,
     1.5     1.5
   71.93   86.51
     1.5     1.5
   71.83   86.41
Pier Skew, UpSta & Num, DnSta & Num=  ,5633.2, 2 ,5633.2, 2 , 0 , 0 , 0 ,,
     1.5     1.5
   71.93   86.52
     1.5     1.5
   71.83   86.42
Abutment Skew #Up #Dn= , 2 , 2
  4899.8    4930
   85.44   73.28
  4899.8    4930
   85.34   73.18
Abutment Skew #Up #Dn= , 2 , 2
    5070 5100.09
   72.54   85.51
    5070 5100.09
   72.44   85.41
Abutment Skew #Up #Dn= , 2 , 2
  5471.8    5502
   85.43   72.94
  5471.8    5502
   85.33   72.84
Abutment Skew #Up #Dn= , 2 , 2
    5642 5672.09
   72.93   85.54
    5642 5672.09
   72.83   85.44
BR Coef= 1 , 1 , 0 ,1.25, 0 ,,,0.8,0,2,0,
WSPro=,,,, 1 ,,,, 0 ,,,, 0 ,,,,-1 ,-1 ,-1 , 0 , 0 , 0 , 0 , 0
BR Coef= 1 , 1 , 0 ,1.25, 0 ,,,0.8,0,2,0,
WSPro=,,,, 1 ,,,, 0 ,,,, 0 ,,,,-1 ,-1 ,-1 , 0 , 0 , 0 , 0 , 0
BC Mult= 3 ,1386.3,5348,1386.3,5348
BC Mult= 3 ,5224,8074,5224,8074
BR U #Sta/Elev= 153
  2386.3    91.6  2394.2   91.29  2426.3   90.05  2576.3   86.21  2586.3   86.31
  2596.3   85.97  2616.3   86.56  2646.3    85.6  2836.3   84.81  2866.3   84.14
  2876.3   84.76  2906.3   84.13  2926.3   84.26  2944.2   83.49  2946.3    83.4
  2984.2   83.59  2986.3    83.6  3006.3   83.03  3054.2   83.52  3056.3   83.54
  3176.3   82.36  3194.2   82.08  3196.3   82.05  3216.3   82.28  3226.3    81.9
  3304.2   82.05  3376.3   82.18  3384.2   81.92  3396.3   81.53  3436.3   81.69
  3456.3   81.06  3476.3   81.71  3504.2   81.45  3526.3   81.25  3616.3   81.63
  3654.2    80.9  3656.3   80.86  3666.3    80.3  3734.2   79.34  3804.2   78.36
  3844.2    77.8  3926.3   76.64  3976.3   75.15  4004.2   74.84  4016.3   74.71
  4056.3   75.44  4096.3   74.69  4164.2    74.9  4214.2   75.06  4226.3    75.1
  4304.2   74.79  4306.3   74.78  4424.2   75.94  4466.3   76.35  4514.2   75.13
  4556.3   74.06  4576.3   74.13  4606.3   73.46  4684.2   74.07  4696.3   74.17
  4726.3   73.75  4736.3   73.95  4844.2   73.62  4886.3   73.49 4899.91   73.88
    4900   73.89  4906.3   74.07    4930   73.28  4936.3   73.07    4970    72.4
  4977.5    66.4  5022.5    66.4    5030    72.4    5070   72.54  5092.2   72.61
 5099.89   72.63    5100   72.63  5104.2   72.63  5144.2   72.72  5264.2   72.97
  5344.2   73.13  5352.2   73.15  5464.2   73.03 5471.91   73.02    5472   73.02
  5482.2   73.01  5492.2   73.36    5502   72.94  5502.2   72.93  5527.2   72.93
  5537.2   67.93  5537.9   67.93  5587.2   67.93  5587.9   68.28  5597.2   72.93
    5642   72.93  5642.2   72.93  5652.2   72.69  5662.2    72.4  5664.2   72.49
 5671.89   72.86    5672   72.87  5702.2    74.3  5704.2    74.3  5754.2   74.36
  5762.2   74.37  5782.2   73.24  5794.2   73.45  5834.2   74.13  5842.2   74.27
  5864.2   74.09  5892.2   73.85  5912.2   73.93  5932.2    73.4  5944.2    73.8
  5952.2   74.06  5962.2   73.75  5982.2   73.99  6012.2   73.41  6042.2   74.27
  6082.2   73.86  6102.2   73.13  6124.2   73.45  6152.2   73.85  6172.2   73.37
  6214.2   73.86  6272.2   74.54  6292.2    74.2  6324.2   74.51  6342.2   74.68
  6412.2   73.39  6432.2   74.23  6472.2   74.32  6482.2   73.89  6504.2    74.3
  6552.2    75.2  6714.2   74.76  6772.2    74.6  6774.2   74.69  6802.2   75.89
  6842.2   75.71  6882.2   76.18  6892.2   75.84  6912.2   77.33  6962.2   82.17
  6972.2   83.65  6992.2   85.78  7002.2   86.32  7022.2   88.47  7042.2   88.83
  7044.2   89.04  7062.2   90.94    7074    91.7
BR U #Mann= 5
  2386.3     .15    4970     .05    5030     .15  5537.9     .05  5587.9     .15
BR U Banks=4970,5030
BR D #Sta/Elev= 153
  2386.3    91.5  2394.2   91.19  2426.3   89.95  2576.3   86.11  2586.3   86.21
  2596.3   85.87  2616.3   86.46  2646.3    85.5  2836.3   84.71  2866.3   84.04
  2876.3   84.66  2906.3   84.03  2926.3   84.16  2944.2   83.39  2946.3    83.3
  2984.2   83.49  2986.3    83.5  3006.3   82.93  3054.2   83.42  3056.3   83.44
  3176.3   82.26  3194.2   81.98  3196.3   81.95  3216.3   82.18  3226.3    81.8
  3304.2   81.95  3376.3   82.08  3384.2   81.82  3396.3   81.43  3436.3   81.59
  3456.3   80.96  3476.3   81.61  3504.2   81.35  3526.3   81.15  3616.3   81.53
  3654.2    80.8  3656.3   80.76  3666.3    80.2  3734.2   79.24  3804.2   78.26
  3844.2    77.7  3926.3   76.54  3976.3   75.05  4004.2   74.74  4016.3   74.61
  4056.3   75.34  4096.3   74.59  4164.2    74.8  4214.2   74.96  4226.3      75
  4304.2   74.69  4306.3   74.68  4424.2   75.84  4466.3   76.25  4514.2   75.03
  4556.3   73.96  4576.3   74.03  4606.3   73.36  4684.2   73.97  4696.3   74.07
  4726.3   73.65  4736.3   73.85  4844.2   73.52  4886.3   73.39 4899.91   73.78
    4900   73.79  4906.3   73.97    4930   73.18  4936.3   72.97    4970    72.3
  4977.5    66.3  5022.5    66.3    5030    72.3    5070   72.44  5092.2   72.51
 5099.89   72.53    5100   72.53  5104.2   72.53  5144.2   72.62  5264.2   72.87
  5344.2   73.03  5352.2   73.05  5464.2   72.93 5471.91   72.92    5472   72.92
  5482.2   72.91  5492.2   73.26    5502   72.84  5502.2   72.83  5527.2   72.83
  5537.2   67.83  5537.9   67.83  5587.2   67.83  5587.9   68.18  5597.2   72.83
    5642   72.83  5642.2   72.83  5652.2   72.59  5662.2    72.3  5664.2   72.39
 5671.89   72.76    5672   72.77  5702.2    74.2  5704.2    74.2  5754.2   74.26
  5762.2   74.27  5782.2   73.14  5794.2   73.35  5834.2   74.03  5842.2   74.17
  5864.2   73.99  5892.2   73.75  5912.2   73.83  5932.2    73.3  5944.2    73.7
  5952.2   73.96  5962.2   73.65  5982.2   73.89  6012.2   73.31  6042.2   74.17
  6082.2   73.76  6102.2   73.03  6124.2   73.35  6152.2   73.75  6172.2   73.27
  6214.2   73.76  6272.2   74.44  6292.2    74.1  6324.2   74.41  6342.2   74.58
  6412.2   73.29  6432.2   74.13  6472.2   74.22  6482.2   73.79  6504.2    74.2
  6552.2    75.1  6714.2   74.66  6772.2    74.5  6774.2   74.59  6802.2   75.79
  6842.2   75.61  6882.2   76.08  6892.2   75.74  6912.2   77.23  6962.2   82.07
  6972.2   83.55  6992.2   85.68  7002.2   86.22  7022.2   88.37  7042.2   88.73
  7044.2   88.94  7062.2   90.84    7074    91.6
BR D #Mann= 5
  2386.3     .15    4970     .05    5030     .15  5537.9     .05  5587.9     .15
BR D Banks=4970,5030
BC Design=,, 0 ,, 0 ,,,,,,
BC HTab HWMax=91.72