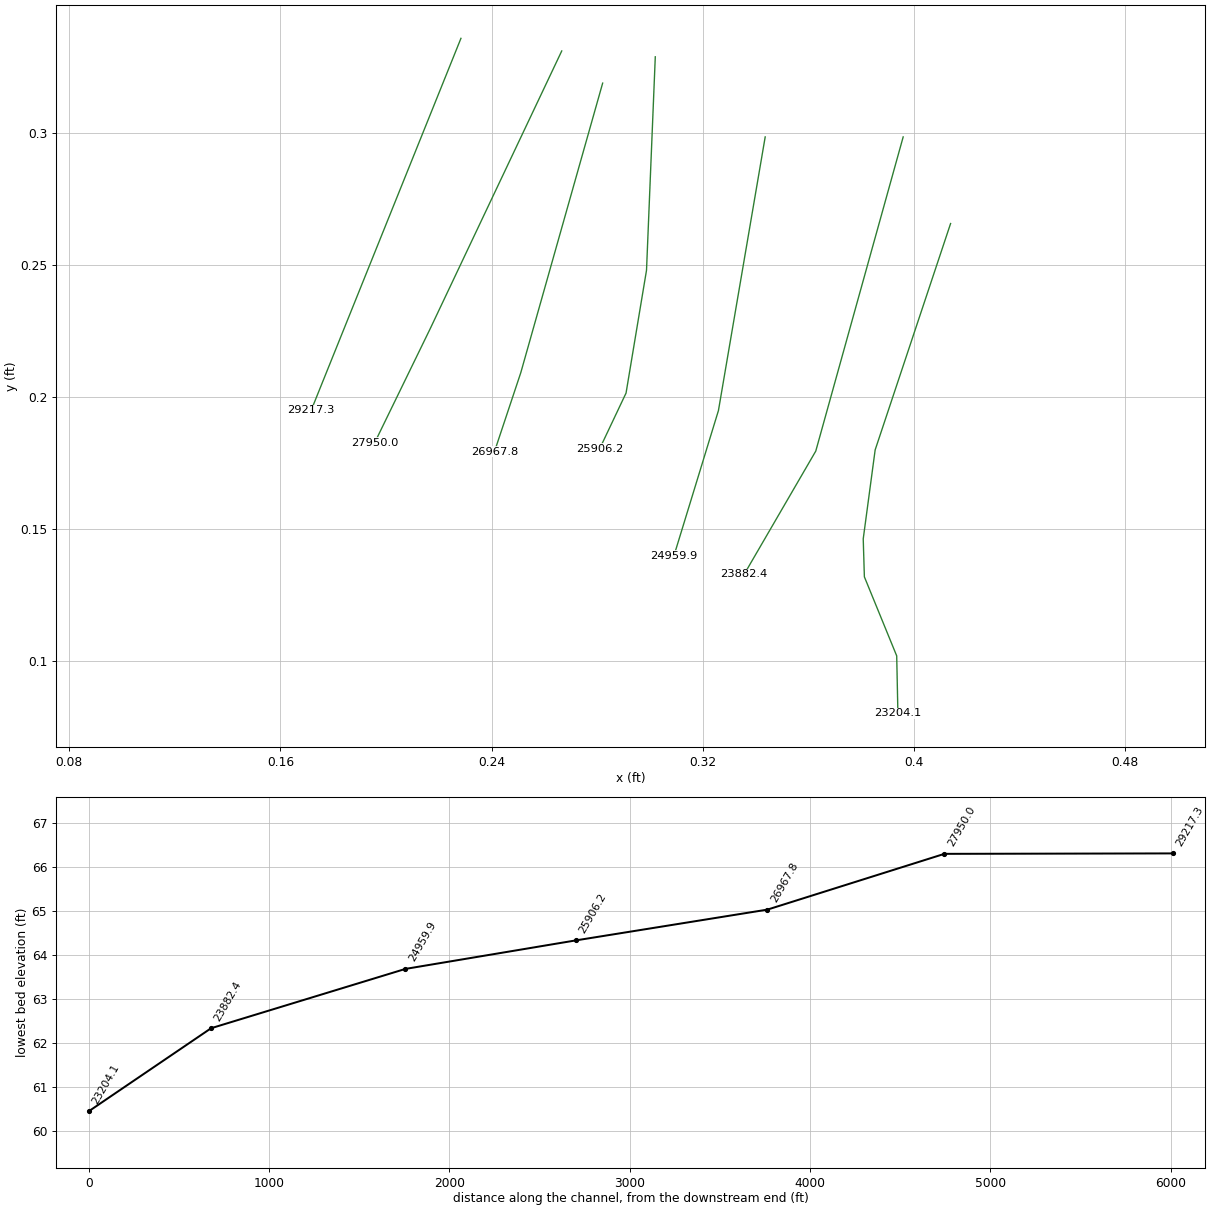
HEC-RAS study Black_Creek_DS_FINAL.prj: Black Creek DS

--- Black_Creek_DS_FINAL.g01 (geometry) --- (continued)

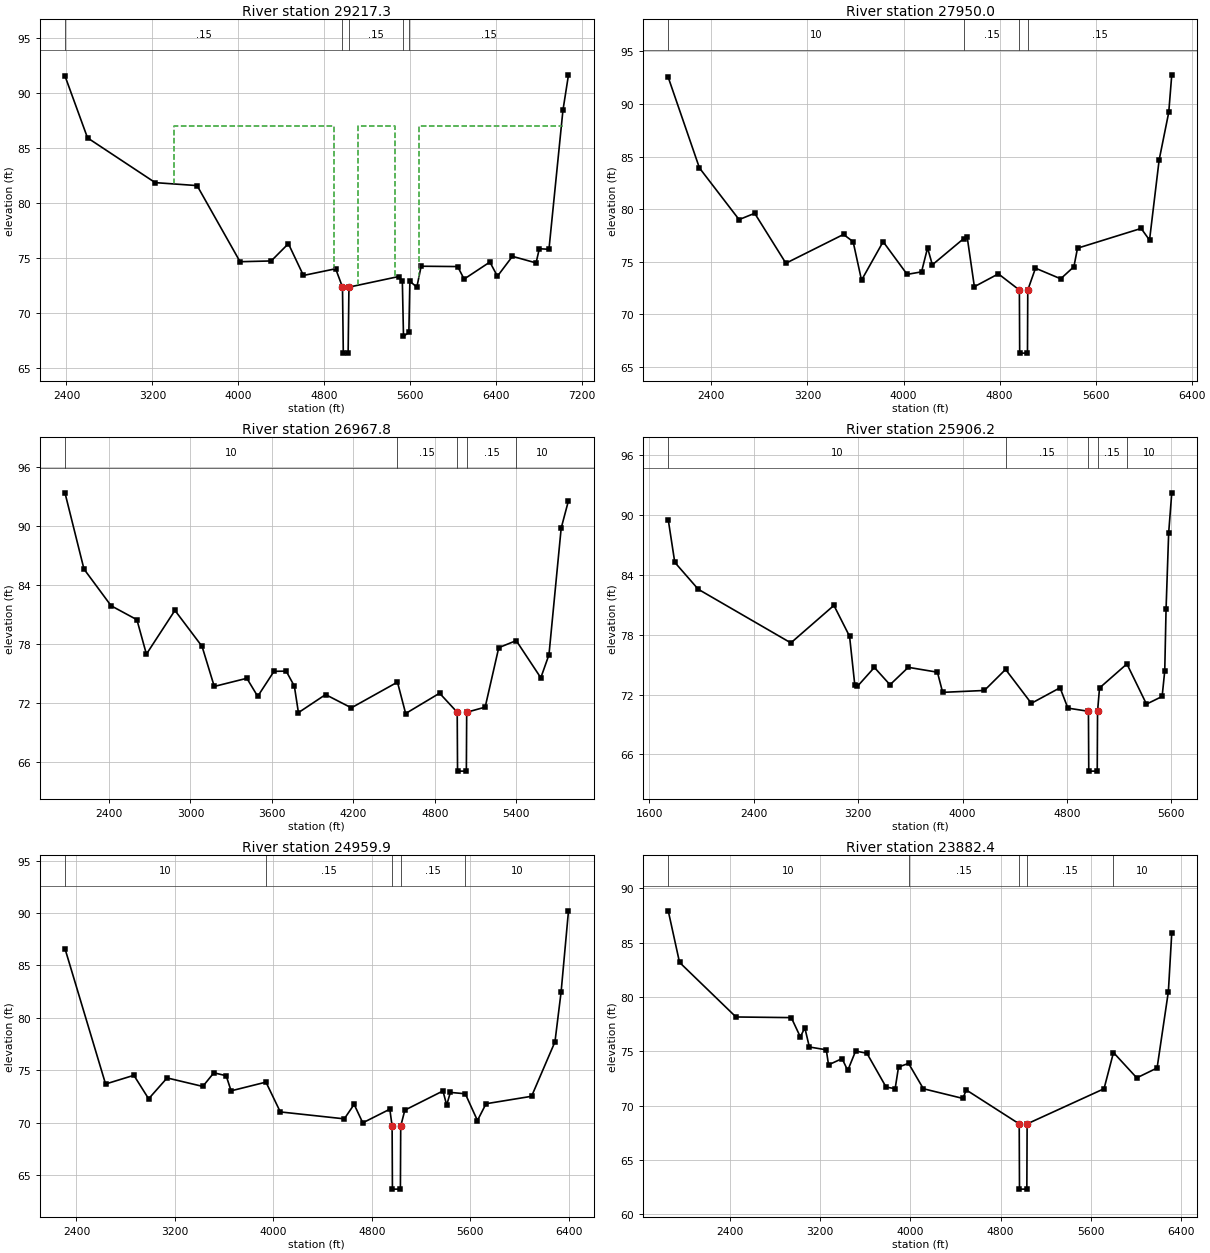
Type RM Length L Ch R = 1 ,29217.3 ,1267.3,1267.3,1267.3
BEGIN DESCRIPTION:
Downstream Section of Bridge/Culvert/Weir
END DESCRIPTION:
XS GIS Cut Line= 3
        .2283826        .3358075        .1982163         .260891
        .1716304        .1948836
#Sta/Elev= 30
  2386.3   91.51  2596.3   85.88  3226.3   81.81  3616.3   81.54  4016.3   74.62
  4306.3   74.69  4466.3   76.26  4606.3   73.37  4906.3   73.98    4970   72.31
  4977.5   66.31  5022.5   66.31    5030   72.31  5492.2   73.27  5527.2   72.84
  5537.9   67.84  5587.9   68.19  5597.2   72.84  5662.2   72.31  5702.2   74.21
  6042.2   74.18  6102.2   73.04  6342.2   74.59  6412.2    73.3  6552.2   75.11
  6772.2   74.51  6802.2    75.8  6892.2   75.75  7022.2   88.38    7074   91.61
#Mann= 5 , 1 , 0
  2386.3     .15       0    4970     .05       0    5030     .15       0
  5537.9     .05       0  5587.9     .15       0
#XS Ineff= 3 ,-1
    3400    4890      87    5110    5460      87    5680    7020      87
Permanent Ineff=
       F       F       F
Bank Sta=4970,5030
Exp/Cntr=0.5,0.3

Type RM Length L Ch R = 1 ,27950.0 ,982.2,982.2,982.2
BEGIN DESCRIPTION:
Black Creek DS 29.0
END DESCRIPTION:
XS GIS Cut Line= 3
        .2665627        .3310285        .2167343        .2258353
        .1956957        .1826507
#Sta/Elev= 30
  2040.2   92.53  2300.2   83.91  2630.2      79  2760.2    79.6  3020.2   74.85
  3500.2   77.59  3580.2    76.9  3650.2   73.24  3830.2    76.9  4030.2   73.79
  4150.2   74.03  4200.2   76.31  4240.2    74.7  4499.9   77.18  4530.2   77.35
  4590.2   72.62  4790.2   73.84  4965.1    72.3  4967.6    66.3  5032.5    66.3
    5035    72.3  5099.2   74.38  5309.2   73.37  5419.2   74.52  5449.2   76.28
  5979.2   78.16  6049.2   77.05  6129.2   84.67  6209.2    89.2  6234.4   92.77
#Mann= 4 , 1 , 0
  2040.2      10       0  4499.9     .15       0  4965.1     .05       0
    5035     .15       0
Bank Sta=4965.1,5035
Exp/Cntr=0.3,0.1

Type RM Length L Ch R = 1 ,26967.8 ,1061.6,1061.6,1061.6
BEGIN DESCRIPTION:
Black Creek DS 28.0
END DESCRIPTION:
XS GIS Cut Line= 3
        .2820648        .3188482        .2510605        .2092258
        .2410949        .1793288
#Sta/Elev= 30
  2075.3   93.39  2215.3   85.62  2415.3   81.88  2605.3   80.46  2675.3   76.95
  2885.3   81.41  3085.3   77.74  3175.3   73.66  3415.3   74.49  3495.3   72.65
  3615.3    75.2  3705.3   75.22  3765.3   73.69  3795.3   70.99  3995.3   72.83
  4185.3   71.48  4524.9    74.1  4585.3    70.9  4835.3   72.97  4965.1   71.03
  4967.6   65.03  5032.5   65.03    5035   71.03  5171.1   71.55  5271.1   77.61
  5399.9   78.33  5581.1   74.54  5641.1   76.89  5731.1   89.79    5785    92.6
#Mann= 5 , 1 , 0
  2075.3      10       0  4524.9     .15       0  4965.1     .05       0
    5035     .15       0  5399.9      10       0
Bank Sta=4965.1,5035
Exp/Cntr=0.3,0.1

Type RM Length L Ch R = 1 ,25906.2 ,946.3,946.3,946.3
BEGIN DESCRIPTION:
Black Creek DS 27.0
END DESCRIPTION:
XS GIS Cut Line= 4
        .3019962        .3288139        .2986743        .2479812
        .2909232        .2014748        .2809575        .1804361
#Sta/Elev= 30
  1743.9   89.55  1793.9   85.27  1973.9   82.57  2683.9   77.19  3013.9   80.95
  3133.9   77.85  3173.9   72.98  3193.9   72.83  3323.9   74.73  3443.9   72.99
  3583.9   74.74  3807.4   74.25  3847.4   72.23  4167.4   72.42  4329.9   74.53
  4527.4   71.13  4747.4   72.69  4807.4   70.65    4965   70.33  4967.5   64.33
  5032.4   64.33  5034.9   70.33    5050   72.67  5259.9   75.08    5410   71.05
    5530   71.82    5550   74.39    5560   80.55    5580   88.21  5603.8   92.24
#Mann= 5 , 1 , 0
  1743.9      10       0  4329.9     .15       0    4965     .05       0
  5034.9     .15       0  5259.9      10       0
Bank Sta=4965,5034.9
Exp/Cntr=0.3,0.1

Type RM Length L Ch R = 1 ,24959.9 ,1077.5,1077.5,1077.5
BEGIN DESCRIPTION:
Black Creek DS 26.0
END DESCRIPTION:
XS GIS Cut Line= 3
        .3436305        .2984739        .3259138         .194831
        .3090829        .1399091
#Sta/Elev= 30
  2306.5   86.61  2636.5    73.7  2866.5   74.53  2986.5   72.29  3136.5   74.28
  3426.5   73.47  3516.5   74.77  3616.5   74.49  3656.5   73.05  3939.9   73.88
  4056.5   71.04  4576.5   70.38  4656.5   71.76  4726.5      70  4946.5    71.3
  4965.1   69.68  4967.6   63.68  5032.5   63.68    5035   69.68  5068.5   71.21
  5378.5   73.04  5408.5   71.69  5438.5    72.9  5559.9   72.77  5658.5   70.22
  5728.5   71.82  6098.5   72.53  6288.5   77.72  6338.5   82.48  6398.5   90.21
#Mann= 5 , 1 , 0
  2306.5      10       0  3939.9     .15       0  4965.1     .05       0
    5035     .15       0  5559.9      10       0
Bank Sta=4965.1,5035
Exp/Cntr=0.3,0.1

Type RM Length L Ch R = 1 ,23882.4 ,678.3,678.3,678.3
BEGIN DESCRIPTION:
Black Creek DS 24.0
END DESCRIPTION:
XS GIS Cut Line= 3
        .3958949        .2984739        .3627818        .1794838
         .335658        .1328224
#Sta/Elev= 30
  1855.9   87.92  1955.9   83.18  2455.9   78.16  2945.9    78.1  3025.9   76.33
  3065.9   77.16  3105.9    75.4  3255.9   75.14  3275.9   73.76  3395.9   74.33
  3445.9   73.24  3515.9   75.03  3615.9   74.82  3785.9   71.71  3865.9   71.57
  3895.9   73.56  3984.9   73.89  4115.9   71.56  4465.9   70.67  4495.9   71.45
  4964.9   68.33  4967.4   62.33  5032.5   62.33    5035   68.33  5716.3   71.56
  5799.9   74.89  6006.3   72.56  6186.3   73.47  6286.3    80.5  6316.3    85.9
#Mann= 5 , 1 , 0
  1855.9      10       0  3984.9     .15       0  4964.9     .05       0
    5035     .15       0  5799.9      10       0
Bank Sta=4964.9,5035
Exp/Cntr=0.5,0.3

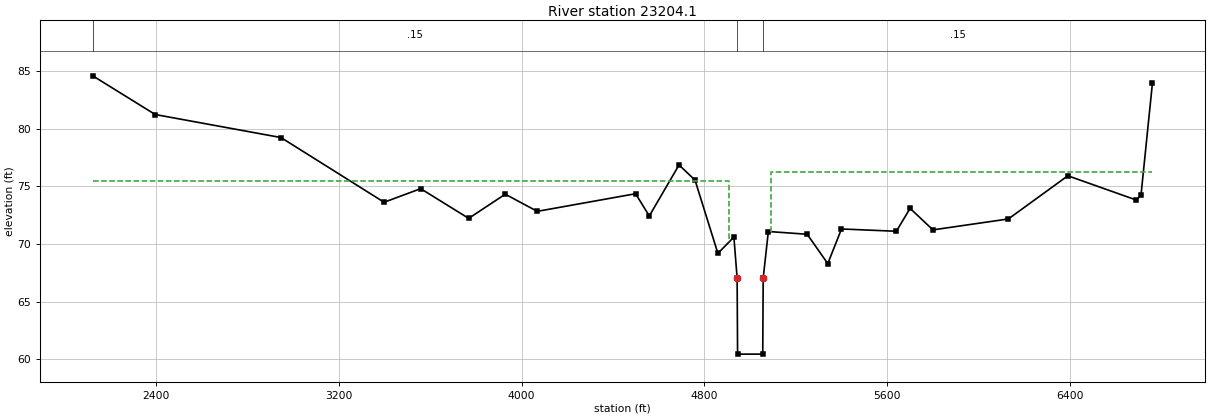
Type RM Length L Ch R = 1 ,23204.1 ,48,48,48
BEGIN DESCRIPTION:
Upstream Section of Bridge/Culvert/Weir
END DESCRIPTION:
XS GIS Cut Line= 6
        .4138521        .2656667        .3852785         .179946
        .3807615        .1462539        .3811966        .1318698
        .3934424        .1019356         .393896        .0801653
#Sta/Elev= 30
  2124.7   84.61  2397.8   81.25  2947.8   79.25  3398.9   73.63  3558.9   74.81
  3768.9   72.23  3928.9   74.33  4068.9   72.84  4498.9   74.37  4558.9   72.44
  4688.9   76.87  4758.9   75.55  4858.9   69.19  4928.9   70.61    4943   67.04
    4945   60.44    5055   60.44    5057   67.04  5079.5   71.09  5249.5   70.85
  5339.5    68.3  5399.5   71.31  5639.5   71.11  5699.5    73.1  5799.5   71.23
  6129.5   72.18  6389.5   75.93  6689.5   73.82  6709.5   74.25  6759.5   83.98
#Mann= 3 , 1 , 0
  2124.7     .15       0    4943     .05       0    5057     .15       0
#XS Ineff= 2 , 0
       0    4909    75.5    5091       0    76.3
Permanent Ineff=
       F       F
Bank Sta=4943,5057
Exp/Cntr=0.5,0.3