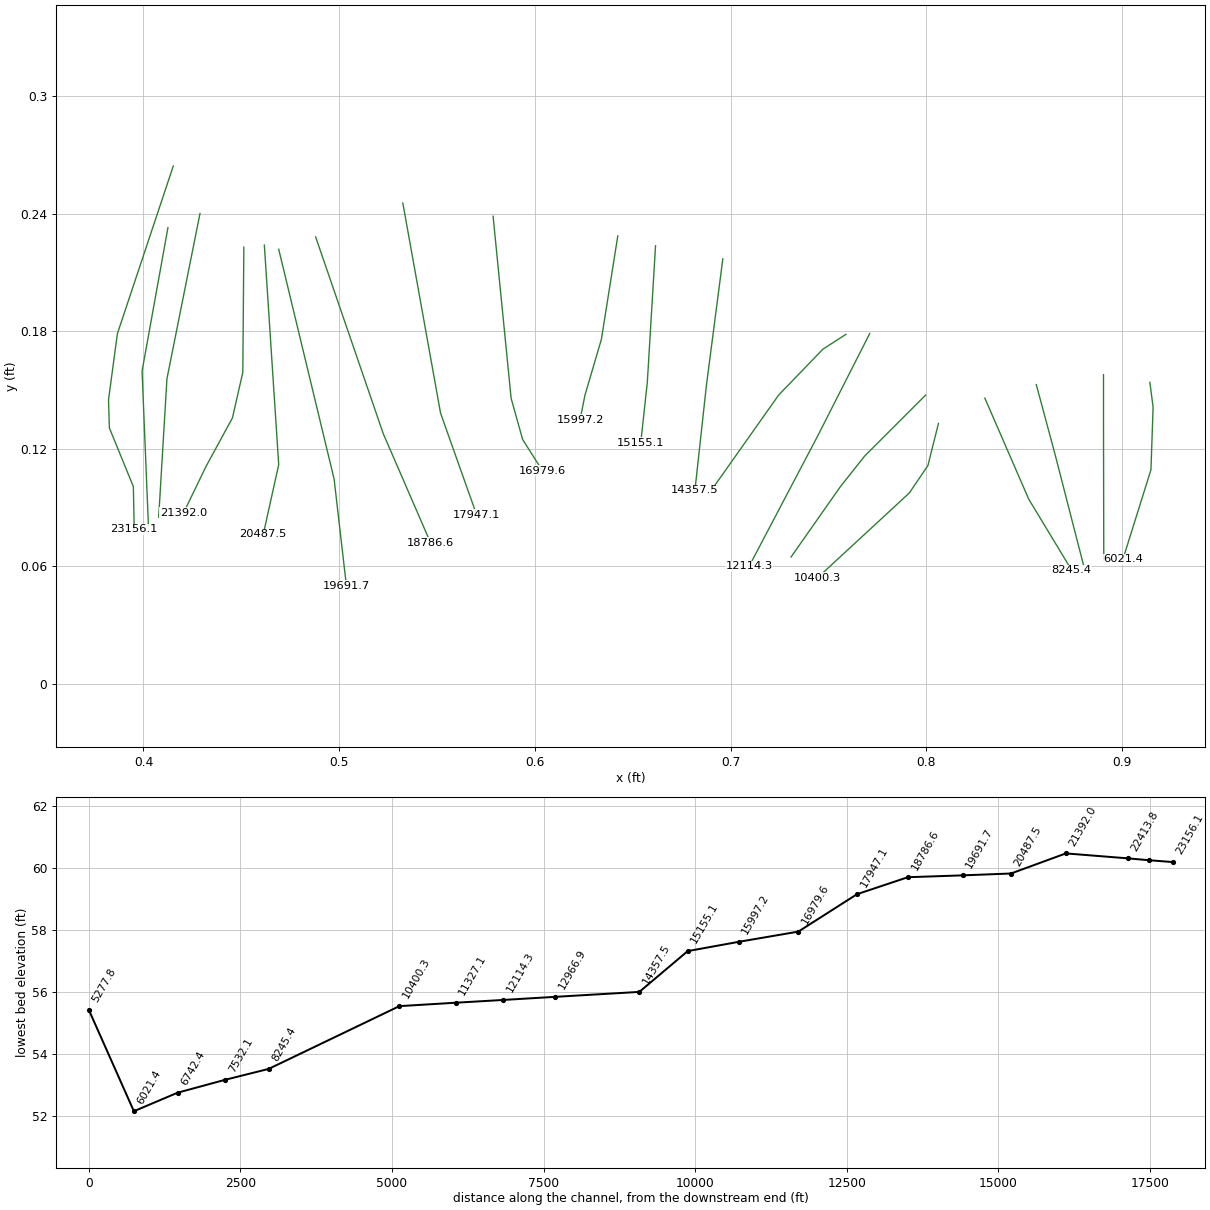
HEC-RAS study Black_Creek_DS_FINAL.prj: Black Creek DS

--- Black_Creek_DS_FINAL.g01 (geometry) --- (continued)

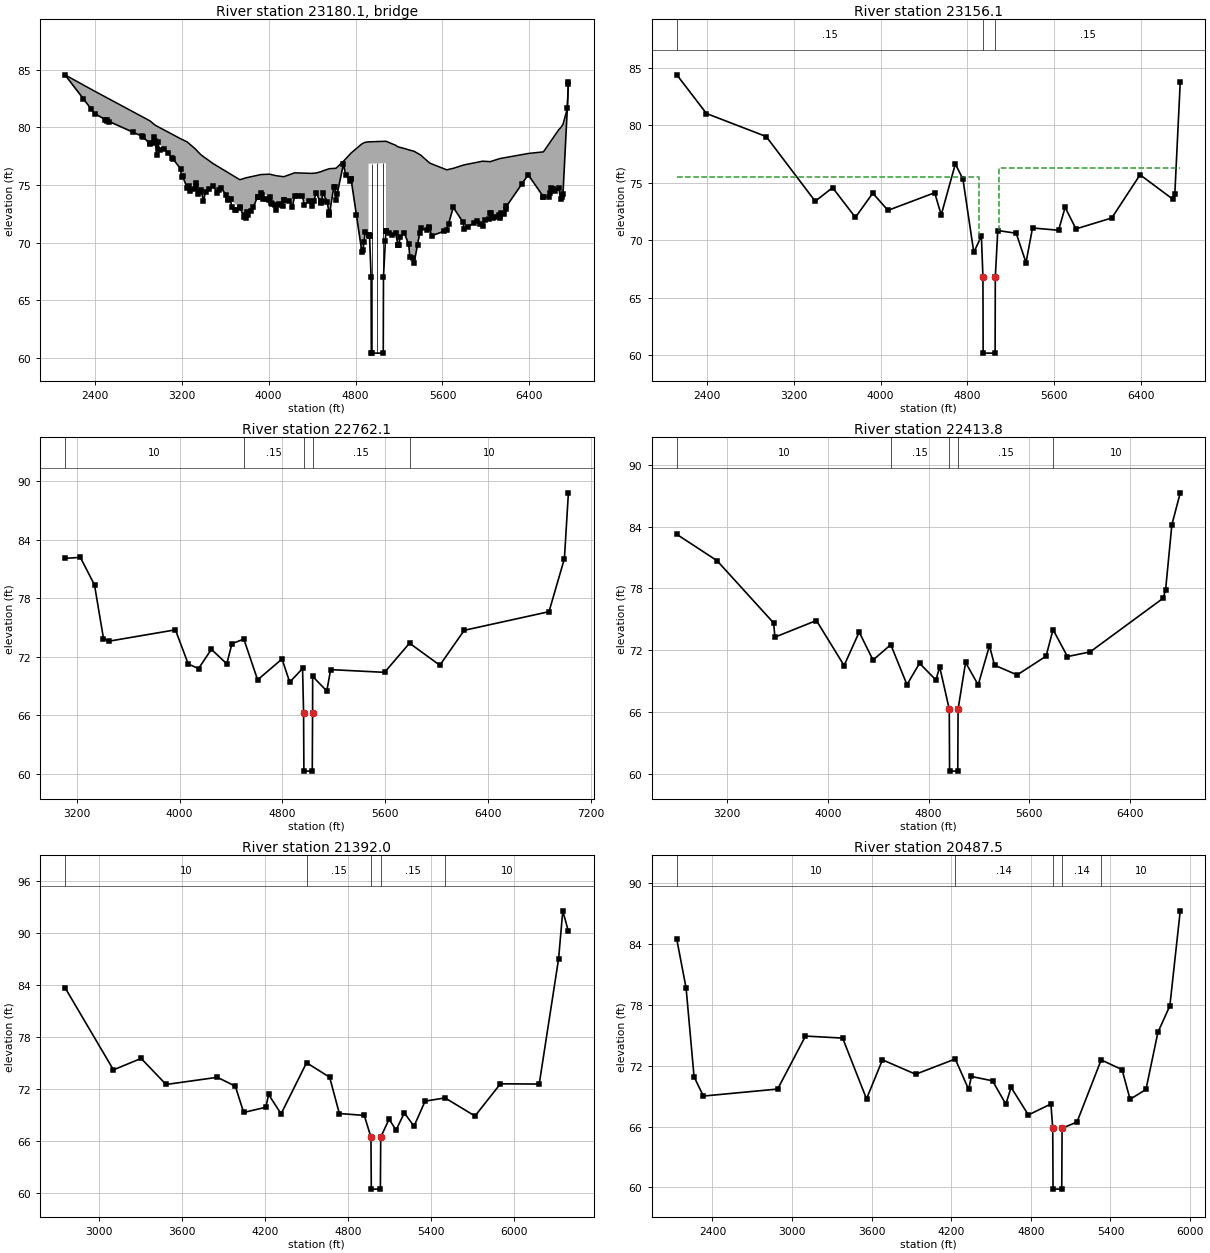
Type RM Length L Ch R = 3 ,23180.1 ,,,
BEGIN DESCRIPTION:
Frank Price Church Rd-TOR
Structure ID: Frank Price Church Rd
Approximate Survey Structure
END DESCRIPTION:
Bridge Culvert--1,0,-1,-1, 0
Deck Dist Width WeirC Skew NumUp NumDn MinLoCord MaxHiCord MaxSubmerge Is_Ogee
10,28,2.6,0, 60, 60, , , 0.95, 0, 1,1,,
  2124.7  2397.8  2907.8  2947.8  2967.8  2977.8  3188.9  3248.9  3328.9  3348.9
  3378.9  3398.9  3488.9  3734.7  3788.9  3928.9  4008.9  4068.9  4138.9  4218.9
  4238.9  4398.9  4438.9  4478.9  4498.9  4558.9  4598.9  4608.9  4618.9  4688.9
  4708.9  4758.9  4858.9  4888.9 4919.41  4919.5 5080.39  5080.5  5169.5  5189.5
  5249.5  5289.5  5299.5  5339.5  5399.5  5479.5  5499.5  5639.5  5699.5  5799.5
  5969.5  6039.5  6129.5  6389.5  6529.5  6669.5  6689.5  6709.5  6749.5  6759.5
   84.57   83.15   80.57   80.25   80.13   80.08   79.02   78.75    78.1   77.89
   77.61   77.47   76.86   75.46   75.62   75.91   75.94   75.81   75.72   75.99
   76.06   76.01   76.05   76.15   76.23   76.42   76.44   76.45   76.45   77.07
   77.27   77.78   78.58   78.71   78.75   78.75    78.8    78.8   78.45   78.32
   78.17   78.06   78.03   77.93    77.6   76.93   76.84   76.32   76.45   76.75
   77.07   77.03    77.3   77.74   77.88   79.79   79.99   80.27   81.65   83.94
   84.57   81.21   78.58   79.21   77.59   78.73   76.41   74.77   75.18   74.19
   74.57   73.59    74.9   73.03   72.15   74.29      74    72.8   73.71   73.09
   74.07   73.16   74.33   73.41   74.33    72.4    74.8   74.83   73.71   76.83
   75.86   75.51   69.15   70.93   70.66   76.85    76.9   71.04   70.79   69.79
   70.81   69.84   68.73   68.26   71.27   71.35   70.59   71.07   73.06   71.19
   71.41    72.6   72.14   75.89   73.98   74.78   73.78   74.21   81.65   83.94
  2124.7  2397.8  2907.8  2947.8  2967.8  2977.8  3188.9  3248.9  3328.9  3348.9
  3378.9  3398.9  3488.9  3734.7  3788.9  3928.9  4008.9  4068.9  4138.9  4218.9
  4238.9  4398.9  4438.9  4478.9  4498.9  4558.9  4598.9  4608.9  4618.9  4688.9
  4708.9  4758.9  4858.9  4888.9 4919.41  4919.5 5080.39  5080.5  5169.5  5189.5
  5249.5  5289.5  5299.5  5339.5  5399.5  5479.5  5499.5  5639.5  5699.5  5799.5
  5969.5  6039.5  6129.5  6389.5  6529.5  6669.5  6689.5  6709.5  6749.5  6759.5
   84.47   83.15   80.57   80.25   80.13   80.08   79.02   78.75    78.1   77.89
   77.61   77.47   76.86   75.46   75.62   75.91   75.94   75.81   75.72   75.99
   76.06   76.01   76.05   76.15   76.23   76.42   76.44   76.45   76.45   77.07
   77.27   77.78   78.58   78.71   78.75   78.75    78.8    78.8   78.45   78.32
   78.17   78.06   78.03   77.93    77.6   76.93   76.84   76.32   76.45   76.75
   77.07   77.03    77.3   77.74   77.88   79.79   79.99   80.27   81.56   83.84
   84.37   81.01   78.38   79.01   77.39   78.53   76.21   74.57   74.98   73.99
   74.37   73.39    74.7   72.83   71.95   74.09    73.8    72.6   73.51   72.89
   73.87   72.96   74.13   73.21   74.13    72.2    74.6   74.63   73.51   76.63
   75.66   75.31   68.95   70.73   70.46   76.65    76.7   70.84   70.59   69.59
   70.61   69.64   68.53   68.06   71.07   71.15   70.39   70.87   72.86   70.99
   71.21    72.4   71.94   75.69   73.78   74.58   73.58   74.01   81.45   83.74
Pier Skew, UpSta & Num, DnSta & Num=  ,4950.4, 2 ,4950.4, 2 , 0 , 0 , 0 ,,
       1       1
    59.4   77.88
       1       1
    59.2   77.68
Pier Skew, UpSta & Num, DnSta & Num=  ,5000, 2 ,5000, 2 , 0 , 0 , 0 ,,
       1       1
    59.4   77.89
       1       1
    59.2   77.69
Pier Skew, UpSta & Num, DnSta & Num=  ,5049.7, 2 ,5049.7, 2 , 0 , 0 , 0 ,,
       1       1
    59.4    77.9
       1       1
    59.2    77.7
Abutment Skew #Up #Dn= , 2 , 2
  4919.3  4925.5
   76.85    70.6
  4919.3  4925.5
   76.65    70.4
Abutment Skew #Up #Dn= , 2 , 2
  5074.5 5080.59
   70.15    76.9
  5074.5 5080.59
   69.95    76.7
BR Coef= 1 , 1 , 0 ,1.25, 0 ,,,0.8,0,2,0,
WSPro=,,,, 1 ,,,, 0 ,,,, 0 ,,,,-1 ,-1 ,-1 , 0 , 0 , 0 , 0 , 0
BR U #Sta/Elev= 183
  2124.7   84.57  2294.7   82.48  2364.7   81.62  2397.8   81.21  2494.7   80.68
  2507.8   80.61  2514.7   80.58  2534.7    80.5  2754.7   79.57  2837.8   79.22
  2844.7   79.16  2904.7   78.61  2907.8   78.58  2947.8   79.21  2954.7   78.84
  2957.8   78.67  2967.8   77.59  2977.8   78.73  2997.8   78.01  3037.8   78.14
  3074.7   77.74  3114.7   77.32  3118.9   77.27  3188.9   76.41  3198.9   75.69
  3208.9   75.74  3248.9   74.77  3254.7   74.82  3268.9   74.95  3278.9    74.5
  3308.9   74.62  3328.9   75.18  3334.7   74.89  3348.9   74.19  3364.7   74.39
  3378.9   74.57  3398.9   73.59  3418.9   74.41  3454.7   74.66  3488.9    74.9
  3528.9   74.32  3544.7   74.56  3558.9   74.77  3608.9   74.14  3624.7   73.77
  3628.9   73.67  3648.9   73.75  3658.9   73.12  3694.7   72.85  3698.9   72.82
  3734.7   73.03  3738.9   73.05  3768.9   72.19  3778.9   72.43  3788.9   72.15
  3798.9   72.66  3804.7   72.51  3808.9   72.41  3834.7   72.76  3858.9   73.09
  3898.9      74  3904.6   73.99  3918.9   73.98  3928.9   74.29  3934.6   74.14
  3948.9   73.77  3974.6   73.75  3998.9   73.74  4008.9      74  4018.9   73.46
  4034.6   73.39  4058.9   73.28  4068.9    72.8  4098.9   73.38  4114.6   73.28
  4128.9   73.18  4138.9   73.71  4144.6    73.7  4188.9   73.64  4218.9   73.09
  4238.9   74.07  4274.6   74.06  4308.9   74.05  4328.9    73.3  4368.9   73.62
  4398.9   73.16  4414.6   73.62  4438.9   74.33  4478.9   73.41  4484.6   73.54
  4488.9   73.64  4498.9   74.33  4538.9   73.54  4554.6   72.65  4558.9    72.4
  4559.6   72.44  4598.9    74.8  4608.9   74.83  4618.9   73.71  4629.6   74.19
  4688.9   76.83  4708.9   75.86  4748.9   75.34  4757.8   75.49  4758.9   75.51
  4807.8    72.4  4858.9   69.15  4868.9   69.35  4877.8   70.05  4888.9   70.93
 4919.41   70.66  4919.5   70.65  4925.5    70.6  4928.9   70.57    4943      67
    4945    60.4  4947.8    60.4    5055    60.4    5057      67  5074.5   70.15
  5079.5   71.05 5080.39   71.04  5080.5   71.04  5110.3   70.83  5139.5   70.63
  5169.5   70.79  5189.5   69.79  5190.3   69.79  5199.5   69.78  5209.5   70.47
  5249.5   70.81  5289.5   69.84  5299.5   68.73  5329.5   68.62  5339.5   68.26
  5370.3   69.81  5390.3   70.81  5399.5   71.27  5459.5   71.08  5476.8   71.31
  5479.5   71.35  5499.5   70.59  5616.8   70.99  5639.5   71.07  5656.8   71.64
  5699.5   73.06  5789.5   71.77  5799.5   71.19  5833.9   71.38  5893.9   71.72
  5919.5   71.87  5943.9   71.65  5969.5   71.41  5989.5      72  6029.5   72.08
  6039.5    72.6  6043.9   72.54  6069.5   72.17  6083.9   72.23  6119.5   72.39
  6129.5   72.14  6133.9   72.33  6139.5   72.57  6169.5   72.45  6183.9   72.95
  6189.5   73.15  6328.8   75.06  6389.5   75.89  6528.8   73.99  6529.5   73.98
  6579.5   73.97  6588.8   74.32  6599.5   74.72  6618.8   74.62  6618.9   74.62
  6639.5   74.51  6669.5   74.78  6689.5   73.78  6698.9   73.98  6709.5   74.21
  6749.5   81.65  6758.9    83.8  6759.5   83.94
BR U #Mann= 3
  2124.7     .15    4943     .05    5057     .15
BR U Banks=4943,5057
BR D #Sta/Elev= 183
  2124.7   84.37  2294.7   82.28  2364.7   81.42  2397.8   81.01  2494.7   80.48
  2507.8   80.41  2514.7   80.38  2534.7    80.3  2754.7   79.37  2837.8   79.02
  2844.7   78.96  2904.7   78.41  2907.8   78.38  2947.8   79.01  2954.7   78.64
  2957.8   78.47  2967.8   77.39  2977.8   78.53  2997.8   77.81  3037.8   77.94
  3074.7   77.54  3114.7   77.12  3118.9   77.07  3188.9   76.21  3198.9   75.49
  3208.9   75.54  3248.9   74.57  3254.7   74.62  3268.9   74.75  3278.9    74.3
  3308.9   74.42  3328.9   74.98  3334.7   74.69  3348.9   73.99  3364.7   74.19
  3378.9   74.37  3398.9   73.39  3418.9   74.21  3454.7   74.46  3488.9    74.7
  3528.9   74.12  3544.7   74.36  3558.9   74.57  3608.9   73.94  3624.7   73.57
  3628.9   73.47  3648.9   73.55  3658.9   72.92  3694.7   72.65  3698.9   72.62
  3734.7   72.83  3738.9   72.85  3768.9   71.99  3778.9   72.23  3788.9   71.95
  3798.9   72.46  3804.7   72.31  3808.9   72.21  3834.7   72.56  3858.9   72.89
  3898.9    73.8  3904.6   73.79  3918.9   73.78  3928.9   74.09  3934.6   73.94
  3948.9   73.57  3974.6   73.55  3998.9   73.54  4008.9    73.8  4018.9   73.26
  4034.6   73.19  4058.9   73.08  4068.9    72.6  4098.9   73.18  4114.6   73.08
  4128.9   72.98  4138.9   73.51  4144.6    73.5  4188.9   73.44  4218.9   72.89
  4238.9   73.87  4274.6   73.86  4308.9   73.85  4328.9    73.1  4368.9   73.42
  4398.9   72.96  4414.6   73.42  4438.9   74.13  4478.9   73.21  4484.6   73.34
  4488.9   73.44  4498.9   74.13  4538.9   73.34  4554.6   72.45  4558.9    72.2
  4559.6   72.24  4598.9    74.6  4608.9   74.63  4618.9   73.51  4629.6   73.99
  4688.9   76.63  4708.9   75.66  4748.9   75.14  4757.8   75.29  4758.9   75.31
  4807.8    72.2  4858.9   68.95  4868.9   69.15  4877.8   69.85  4888.9   70.73
 4919.41   70.46  4919.5   70.45  4925.5    70.4  4928.9   70.37    4943    66.8
    4945    60.2  4947.8    60.2    5055    60.2    5057    66.8  5074.5   69.95
  5079.5   70.85 5080.39   70.84  5080.5   70.84  5110.3   70.63  5139.5   70.43
  5169.5   70.59  5189.5   69.59  5190.3   69.59  5199.5   69.58  5209.5   70.27
  5249.5   70.61  5289.5   69.64  5299.5   68.53  5329.5   68.42  5339.5   68.06
  5370.3   69.61  5390.3   70.61  5399.5   71.07  5459.5   70.88  5476.8   71.11
  5479.5   71.15  5499.5   70.39  5616.8   70.79  5639.5   70.87  5656.8   71.44
  5699.5   72.86  5789.5   71.57  5799.5   70.99  5833.9   71.18  5893.9   71.52
  5919.5   71.67  5943.9   71.45  5969.5   71.21  5989.5    71.8  6029.5   71.88
  6039.5    72.4  6043.9   72.34  6069.5   71.97  6083.9   72.03  6119.5   72.19
  6129.5   71.94  6133.9   72.13  6139.5   72.37  6169.5   72.25  6183.9   72.75
  6189.5   72.95  6328.8   74.86  6389.5   75.69  6528.8   73.79  6529.5   73.78
  6579.5   73.77  6588.8   74.12  6599.5   74.52  6618.8   74.42  6618.9   74.42
  6639.5   74.31  6669.5   74.58  6689.5   73.58  6698.9   73.78  6709.5   74.01
  6749.5   81.45  6758.9    83.6  6759.5   83.74
BR D #Mann= 3
  2124.7     .15    4943     .05    5057     .15
BR D Banks=4943,5057
BC Design=,, 0 ,, 0 ,,,,,,
BC HTab HWMax=84.61

Type RM Length L Ch R = 1 ,23156.1 ,394,394,394
BEGIN DESCRIPTION:
Downstream Section of Bridge/Culvert/Weir
END DESCRIPTION:
XS GIS Cut Line= 6
        .4152279        .2643827        .3866543        .1786621
        .3821373          .14497        .3825724        .1305859
        .3948182        .1006517        .3952718        .0788814
#Sta/Elev= 30
  2124.7   84.37  2397.8   81.01  2947.8   79.01  3398.9   73.39  3558.9   74.57
  3768.9   71.99  3928.9   74.09  4068.9    72.6  4498.9   74.13  4558.9    72.2
  4688.9   76.63  4758.9   75.31  4858.9   68.95  4928.9   70.37    4943    66.8
    4945    60.2    5055    60.2    5057    66.8  5079.5   70.85  5249.5   70.61
  5339.5   68.06  5399.5   71.07  5639.5   70.87  5699.5   72.86  5799.5   70.99
  6129.5   71.94  6389.5   75.69  6689.5   73.58  6709.5   74.01  6759.5   83.74
#Mann= 3 , 1 , 0
  2124.7     .15       0    4943     .05       0    5057     .15       0
#XS Ineff= 2 , 0
       0    4909    75.5    5091       0    76.3
Permanent Ineff=
       F       F
Bank Sta=4943,5057
Exp/Cntr=0.5,0.3

Type RM Length L Ch R = 1 ,22762.1 ,348.3,348.3,348.3
BEGIN DESCRIPTION:
Black Creek DS 23.0
END DESCRIPTION:
XS GIS Cut Line= 3
        .4124956        .2328872         .399275         .159636
        .4025335         .080468
#Sta/Elev= 30
  3107.2   82.08  3227.2   82.18  3337.2   79.35  3407.2   73.86  3447.2   73.58
  3967.2   74.75  4067.2   71.24  4147.2   70.78  4247.2   72.75  4367.2   71.26
  4407.2   73.33  4499.9    73.8  4607.2   69.62  4797.2   71.76  4857.2   69.38
  4957.2   70.79    4965   66.26  4967.5   60.26  5032.6   60.26  5035.1   66.26
  5035.8   69.97  5145.8   68.48  5175.8   70.67  5595.8   70.39  5789.9   73.38
  6025.8   71.12  6215.8    74.7  6875.8   76.61  6995.8   82.05  7026.9    88.8
#Mann= 5 , 1 , 0
  3107.2      10       0  4499.9     .15       0    4965     .05       0
  5035.1     .15       0  5789.9      10       0
Bank Sta=4965,5035.1
Exp/Cntr=0.3,0.1

Type RM Length L Ch R = 1 ,22413.8 ,1021.8,1021.8,1021.8
BEGIN DESCRIPTION:
Black Creek DS 22.0
END DESCRIPTION:
XS GIS Cut Line= 3
        .4288691        .2401265        .4119851        .1557065
        .4077641        .0850047
#Sta/Elev= 30
  2798.7   83.24  3118.7   80.69  3568.7   74.66  3578.7   73.29  3908.7    74.9
  4128.7   70.54  4248.7   73.78  4358.7   71.07  4499.9   72.56  4628.7   68.69
  4728.7   70.76  4858.7   69.14  4888.7   70.41  4964.9   66.32  4967.4   60.32
  5032.5   60.32    5035   66.32  5094.6   70.84  5194.6   68.67  5284.6   72.46
  5324.6   70.58  5504.6   69.63  5734.6   71.45  5789.9   74.02  5904.6   71.41
  6084.6   71.86  6664.6   77.05  6684.6   77.84  6734.6   84.16  6801.3   87.26
#Mann= 5 , 1 , 0
  2798.7      10       0  4499.9     .15       0  4964.9     .05       0
    5035     .15       0  5789.9      10       0
Bank Sta=4964.9,5035
Exp/Cntr=0.3,0.1

Type RM Length L Ch R = 1 ,21392.0 ,904.5,904.5,904.5
BEGIN DESCRIPTION:
Black Creek DS 21.0
END DESCRIPTION:
XS GIS Cut Line= 5
        .4512678        .2229231        .4507438        .1589939
        .4454458         .135706        .4318794        .1107851
        .4204271        .0871152
#Sta/Elev= 30
  2755.8   83.75  3105.8   74.25  3305.8   75.57  3485.8   72.56  3855.8   73.39
  3985.8   72.36  4045.8   69.33  4205.8   69.93  4225.8   71.41  4315.8   69.17
  4499.9   75.07  4666.5    73.4  4736.5   69.21  4916.5   68.99  4964.7   66.48
  4967.2   60.48  5032.8   60.48  5035.3   66.48  5095.7   68.56  5145.7   67.29
  5205.7   69.28  5275.7   67.74  5355.7   70.64  5499.9   71.01  5715.7   68.92
  5899.4   72.64  6179.4   72.61  6319.4   87.08  6349.4   92.61  6390.1   90.24
#Mann= 5 , 1 , 0
  2755.8      10       0  4499.9     .15       0  4964.7     .05       0
  5035.3     .15       0  5499.9      10       0
Bank Sta=4964.7,5035.3
Exp/Cntr=0.3,0.1

Type RM Length L Ch R = 1 ,20487.5 ,795.8,795.8,795.8
BEGIN DESCRIPTION:
Black Creek DS 20.0
END DESCRIPTION:
XS GIS Cut Line= 3
         .461748        .2239711        .4690841        .1118331
        .4612114        .0763034
#Sta/Elev= 30
  2131.2   84.43  2201.2   79.64  2261.2   70.91  2331.2      69  2891.2   69.69
  3101.2   74.91  3381.2   74.71  3561.2   68.72  3681.2   72.57  3931.2   71.15
  4229.9   72.65  4331.2   69.65  4351.2   70.93  4511.2    70.5  4611.2    68.2
  4651.2   69.85  4781.2   67.14  4951.2   68.22  4964.7   65.83  4967.2   59.83
  5032.8   59.83  5035.3   65.83  5147.6   66.44  5329.9   72.56  5487.6    71.6
  5547.6   68.68  5667.6   69.65  5757.6   75.28  5847.6   77.89  5925.9   87.25
#Mann= 5 , 1 , 0
  2131.2      10       0  4229.9     .14       0  4964.7    .048       0
  5035.3     .14       0  5329.9      10       0
Bank Sta=4964.7,5035.3
Exp/Cntr=0.3,0.1

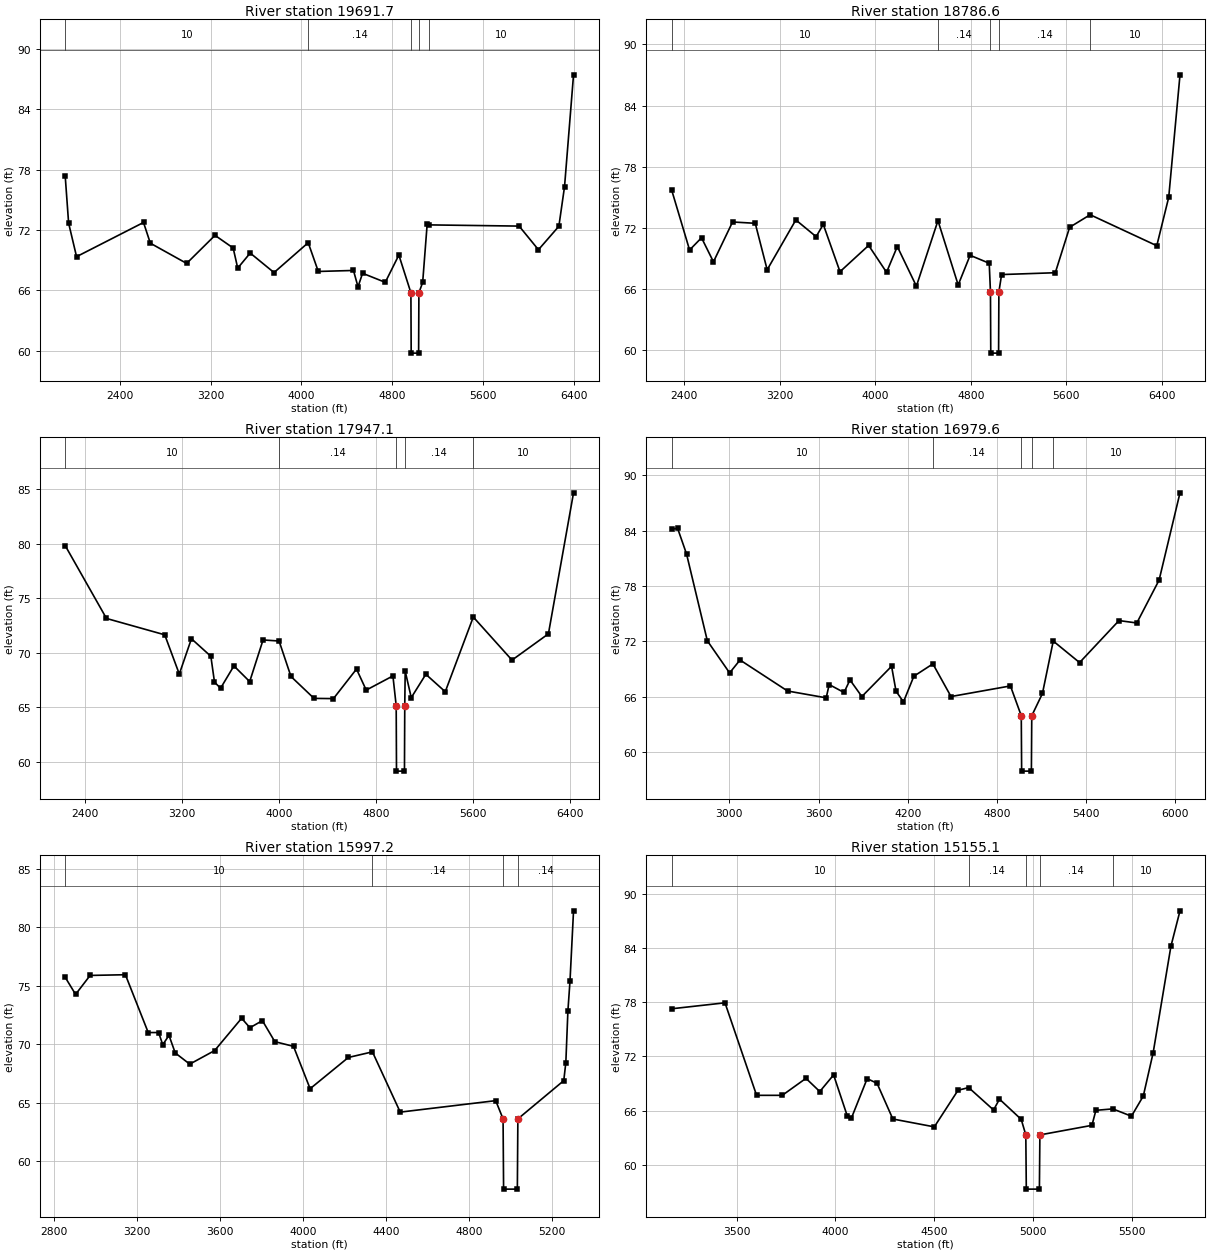
Type RM Length L Ch R = 1 ,19691.7 ,905.1,905.1,905.1
BEGIN DESCRIPTION:
Black Creek DS 19.0
END DESCRIPTION:
XS GIS Cut Line= 3
        .4690841        .2218751        .4973806         .104497
        .5036687             .05
#Sta/Elev= 30
  1918.8   77.38  1948.8    72.7  2018.8   69.36  2608.8   72.76  2668.8    70.7
  2988.8   68.69  3238.8   71.48  3398.8   70.22  3438.8   68.22  3548.8   69.72
  3758.8   67.78  4059.9   70.75  4148.8   67.89  4458.8   67.99  4498.8   66.36
  4538.8   67.71  4738.8   66.81  4858.8   69.52  4964.8   65.77  4967.3   59.77
  5032.8   59.77  5035.3   65.77  5068.5    66.8  5108.5   72.65  5124.9   72.52
  5918.5    72.4  6088.5   70.05  6268.5   72.38  6318.5   76.32  6397.8   87.44
#Mann= 5 , 1 , 0
  1918.8      10       0  4059.9     .14       0  4964.8    .048       0
  5035.3     .14       0  5124.9      10       0
Bank Sta=4964.8,5035.3
Exp/Cntr=0.3,0.1

Type RM Length L Ch R = 1 ,18786.6 ,839.5,839.5,839.5
BEGIN DESCRIPTION:
Black Creek DS 18.0
END DESCRIPTION:
XS GIS Cut Line= 3
        .4879484        .2281632        .5225331        .1275534
        .5466375        .0720084
#Sta/Elev= 30
  2294.3   75.71  2444.3   69.83  2544.3   71.03  2644.3   68.67  2804.3   72.58
  2994.3   72.45  3094.3   67.89  3334.3   72.78  3504.3   71.14  3564.3   72.34
  3704.3    67.7  3944.3   70.28  4094.3   67.64  4184.3   70.17  4344.3   66.28
  4524.9   72.71  4694.3    66.4  4794.3   69.31  4954.3   68.53  4964.7   65.71
  4967.2   59.71  5032.8   59.71  5035.3   65.71  5057.9   67.42  5507.9    67.6
  5627.9   72.06  5799.9   73.29  6357.9   70.25  6457.9      75  6552.4   87.02
#Mann= 5 , 1 , 0
  2294.3      10       0  4524.9     .14       0  4964.7    .048       0
  5035.3     .14       0  5799.9      10       0
Bank Sta=4964.7,5035.3
Exp/Cntr=0.3,0.1

Type RM Length L Ch R = 1 ,17947.1 ,967.5,967.5,967.5
BEGIN DESCRIPTION:
Black Creek DS 17.0
END DESCRIPTION:
XS GIS Cut Line= 3
        .5324892        .2454555        .5517728        .1381384
        .5702179        .0861566
#Sta/Elev= 30
  2237.7   79.84  2577.7   73.16  3057.7   71.66  3177.7   68.06  3277.7    71.3
  3437.7   69.69  3467.7   67.32  3517.7   66.76  3627.7   68.81  3757.7   67.37
  3867.7   71.19  3999.9   71.09  4097.7   67.84  4287.7   65.83  4447.7   65.81
  4637.7   68.52  4717.7   66.59  4937.7   67.89  4964.7   65.16  4967.2   59.16
  5032.8   59.16  5035.3   65.16  5038.9   68.32  5088.9    65.9  5208.9   68.04
  5368.9   66.44  5599.9   73.29  5918.9   69.34  6218.9   71.75  6425.8   84.68
#Mann= 5 , 1 , 0
  2237.7      10       0  3999.9     .14       0  4964.7    .048       0
  5035.3     .14       0  5599.9      10       0
Bank Sta=4964.7,5035.3
Exp/Cntr=0.3,0.1

Type RM Length L Ch R = 1 ,16979.6 ,982.4,982.4,982.4
BEGIN DESCRIPTION:
Black Creek DS 16.0
END DESCRIPTION:
XS GIS Cut Line= 4
        .5786021        .2387482        .5878246        .1456841
        .5936935        .1247237        .6037545        .1087939
#Sta/Elev= 30
  2611.8   84.17  2651.8   84.25  2711.8   81.48  2851.8   72.07  3001.8   68.59
  3071.8   69.99  3391.8   66.63  3651.8   65.89  3671.8   67.33  3771.8   66.47
  3811.8   67.83  3891.8   66.03  4091.8   69.31  4121.8   66.61  4171.8   65.45
  4241.8   68.23  4369.9   69.57  4491.8   66.03  4891.8   67.18  4964.7   63.95
  4967.2   57.95  5032.8   57.95  5035.3   63.95  5107.2   66.36  5179.9   72.04
  5357.2   69.71  5622.4   74.26  5742.4      74  5892.4   78.65    6033    88.1
#Mann= 5 , 1 , 0
  2611.8      10       0  4369.9     .14       0  4964.7    .048       0
  5035.3     .14       0  5179.9      10       0
Bank Sta=4964.7,5035.3
Exp/Cntr=0.3,0.1

Type RM Length L Ch R = 1 ,15997.2 ,842.1,842.1,842.1
BEGIN DESCRIPTION:
Black Creek DS 14.0
END DESCRIPTION:
XS GIS Cut Line= 4
        .6423216        .2286872        .6339375         .175867
        .6255533        .1473609        .6230381        .1347847
#Sta/Elev= 30
  2854.7   75.72  2904.7   74.26  2974.7   75.88  3144.7   75.94  3254.7      71
  3304.7      71  3324.7   69.96  3354.7   70.76  3384.7   69.26  3454.7    68.3
  3574.7   69.46  3704.7   72.22  3744.7   71.41  3804.7   72.02  3864.7   70.22
  3954.7   69.82  4034.7    66.2  4218.9   68.87  4334.9   69.35  4468.9    64.2
  4928.9   65.18  4964.4   63.62  4966.9   57.62  5033.2   57.62  5035.7   63.62
  5256.8   66.89  5266.8   68.43  5276.8   72.86  5286.8   75.38  5303.9    81.4
#Mann= 4 , 1 , 0
  2854.7      10       0  4334.9     .14       0  4964.4    .048       0
  5035.7     .14       0
Bank Sta=4964.4,5035.7
Exp/Cntr=0.3,0.1

Type RM Length L Ch R = 1 ,15155.1 ,797.6,797.6,797.6
BEGIN DESCRIPTION:
Black Creek DS 13.0
END DESCRIPTION:
XS GIS Cut Line= 3
        .6616051        .2236567        .6574131        .1540683
        .6540594        .1230469
#Sta/Elev= 30
    3171   77.28    3441   77.94    3601    67.7    3731    67.7    3851   69.58
    3921   68.12    3991   69.96    4061   65.37    4081   65.17    4161   69.55
    4211   69.03    4291   65.08    4501   64.21    4621   68.26  4674.9   68.56
    4801   66.08    4831   67.28    4941   65.04  4964.3   63.32  4966.8   57.32
  5033.1   57.32  5035.6   63.32  5299.2   64.38  5319.2   66.04  5404.9    66.2
  5499.2   65.39  5559.2   67.62  5609.2   72.42  5699.2   84.21  5745.1   88.12
#Mann= 5 , 1 , 0
    3171      10       0  4674.9     .14       0  4964.3    .048       0
  5035.6     .14       0  5404.9      10       0
Bank Sta=4964.3,5035.6
Exp/Cntr=0.3,0.1

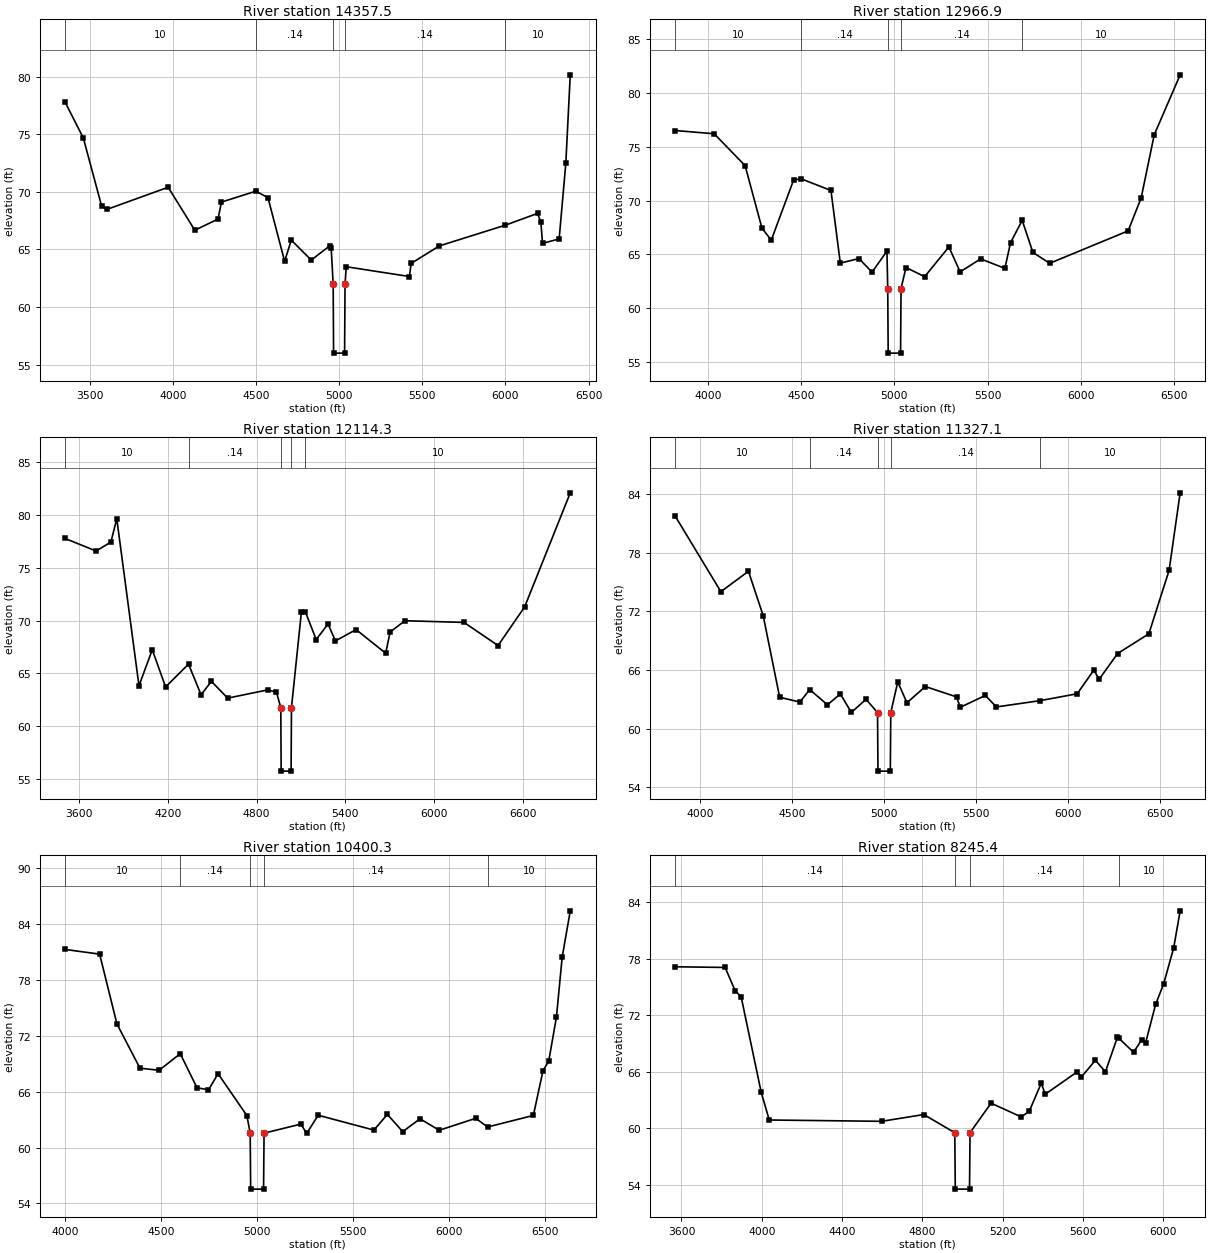
Type RM Length L Ch R = 1 ,14357.5 ,1390.6,1390.6,1390.6
BEGIN DESCRIPTION:
Black Creek DS 12.0
END DESCRIPTION:
XS GIS Cut Line= 3
        .6959802        .2169494         .687596        .1523914
        .6817271        .0987329
#Sta/Elev= 30
  3352.4    77.8  3462.4   74.67  3572.4   68.76  3602.4   68.47  3972.4    70.4
  4132.4   66.67  4272.4   67.64  4292.4   69.11  4499.9   70.06  4572.4   69.49
  4672.4   63.97  4712.4   65.81  4832.4   64.08  4942.4    65.3  4952.4   65.11
  4964.3      62  4966.8      56  5033.1      56  5035.6      62  5042.9    63.5
  5422.9   62.65  5432.9   63.79  5602.9   65.31  5999.9   67.11  6192.9   68.13
  6212.9   67.38  6222.9   65.53  6322.9   65.91  6362.9   72.48  6389.7   80.16
#Mann= 5 , 1 , 0
  3352.4      10       0  4499.9     .14       0  4964.3    .048       0
  5035.6     .14       0  5999.9      10       0
Bank Sta=4964.3,5035.6
Exp/Cntr=0.3,0.1

Type RM Length L Ch R = 1 ,12966.9 ,852.6,852.6,852.6
BEGIN DESCRIPTION:
Black Creek DS 11.0
END DESCRIPTION:
XS GIS Cut Line= 4
        .7588613        .1783823        .7471235        .1708366
        .7244863        .1473609        .6901113        .0987329
#Sta/Elev= 30
  3824.4   76.51  4034.4   76.21  4200.3   73.25  4290.3   67.46  4340.3   66.32
  4460.3   71.92  4499.9   72.03  4660.3   70.94  4710.3    64.2  4810.3   64.62
  4880.3   63.36  4960.3   65.31  4964.4   61.84  4966.9   55.84  5033.2   55.84
  5035.7   61.84  5062.2   63.79  5162.2   62.94  5292.2    65.7  5352.2   63.38
  5462.2   64.59  5592.2   63.71  5622.2   66.09  5684.9   68.17  5742.2   65.19
  5832.2   64.18  6252.2   67.19  6322.2   70.25  6392.2   76.11  6531.1   81.68
#Mann= 5 , 1 , 0
  3824.4      10       0  4499.9     .14       0  4964.4    .048       0
  5035.7     .14       0  5684.9      10       0
Bank Sta=4964.4,5035.7
Exp/Cntr=0.3,0.1

Type RM Length L Ch R = 1 ,12114.3 ,787.2,787.2,787.2
BEGIN DESCRIPTION:
Black Creek DS 9.0
END DESCRIPTION:
XS GIS Cut Line= 3
        .7710183        .1788015        .7444016        .1264156
         .709378        .0598472
#Sta/Elev= 30
  3504.6   77.77  3714.6   76.58  3814.6   77.43  3854.6   79.63  4004.6   63.82
  4094.6   67.23  4184.6   63.71  4339.9   65.87  4424.6   62.97  4494.6   64.24
  4604.6   62.65  4874.6   63.43  4934.6   63.22  4963.9   61.74  4966.4   55.74
  5033.6   55.74  5036.1   61.74  5103.4   70.83  5129.9   70.83  5203.4    68.2
  5283.4   69.67  5333.4   68.07  5473.4   69.14  5673.4    66.9  5703.4   68.91
  5803.4   69.98  6203.4   69.82  6433.4   67.63  6613.4   71.29    6922   82.09
#Mann= 5 , 1 , 0
  3504.6      10       0  4339.9     .14       0  4963.9    .048       0
  5036.1     .14       0  5129.9      10       0
Bank Sta=4963.9,5036.1
Exp/Cntr=0.3,0.1

Type RM Length L Ch R = 1 ,11327.1 ,926.8,926.8,926.8
BEGIN DESCRIPTION:
Black Creek DS 8.0
END DESCRIPTION:
XS GIS Cut Line= 4
        .7995244        .1473106        .7684024        .1161887
         .756061        .1006277        .7308415        .0646765
#Sta/Elev= 30
  3861.5    81.8  4111.5   74.02  4261.5   76.11  4341.5   71.58  4431.5   63.21
  4541.5   62.72  4594.9      64  4691.5   62.44  4761.5   63.55  4821.5   61.66
  4901.5      63  4963.9   61.65  4966.4   55.65  5033.6   55.65  5036.1   61.65
  5074.1   64.78  5124.1   62.65  5224.1   64.31  5394.1   63.25  5414.1   62.18
  5550.7    63.4  5610.7   62.22  5849.9   62.87  6050.7   63.57  6140.7   65.98
  6170.7   65.07  6270.7   67.69  6440.7   69.71  6550.7    76.2  6610.9   84.14
#Mann= 5 , 1 , 0
  3861.5      10       0  4594.9     .14       0  4963.9    .048       0
  5036.1     .14       0  5849.9      10       0
Bank Sta=4963.9,5036.1
Exp/Cntr=0.3,0.1

Type RM Length L Ch R = 1 ,10400.3 ,2154.9,2154.9,2154.9
BEGIN DESCRIPTION:
Black Creek DS 6.0
END DESCRIPTION:
XS GIS Cut Line= 4
        .8061332        .1328899        .8007464        .1113426
        .7912481        .0973617        .7442561        .0539447
#Sta/Elev= 30
  4000.3   81.23  4180.3   80.73  4270.3   73.25  4390.3    68.5  4490.3   68.28
  4599.9   70.06  4686.8   66.41  4746.8   66.18  4796.8   67.91  4946.8   63.42
  4963.9   61.54  4966.4   55.54  5033.6   55.54  5036.1   61.54  5227.9   62.51
  5257.9   61.51  5317.9   63.46  5607.9   61.87  5677.9   63.55  5757.9    61.7
  5847.9   63.08  5947.9   61.85  6137.9   63.13  6199.9    62.2  6437.9   63.44
  6487.9   68.23  6517.9   69.27  6557.9   73.98  6587.9   80.42  6629.9   85.37
#Mann= 5 , 1 , 0
  4000.3      10       0  4599.9     .14       0  4963.9    .048       0
  5036.1     .14       0  6199.9      10       0
Bank Sta=4963.9,5036.1
Exp/Cntr=0.3,0.1

Type RM Length L Ch R = 1 ,8245.4  ,713.3,713.3,713.3
BEGIN DESCRIPTION:
Black Creek DS 5.0
END DESCRIPTION:
XS GIS Cut Line= 3
        .8298352        .1458183         .852261        .0942086
        .8742226        .0579054
#Sta/Elev= 30
  3567.5   77.15  3817.5   77.08  3867.5   74.61  3897.5   73.95  3997.5   63.79
  4037.5   60.86  4597.5   60.72  4807.5   61.44    4962   59.51  4964.5   53.51
  5035.5   53.51    5038   59.51  5142.8   62.65  5292.8   61.19  5332.8   61.77
  5392.8   64.77  5412.8    63.6  5572.8   65.99  5592.8   65.43  5662.8   67.21
  5712.8   65.98  5772.8   69.69  5779.9   69.55  5852.8   68.06  5892.8   69.37
  5912.8   69.05  5962.8   73.15  6002.8   75.33  6052.8   79.15  6085.1    83.1
#Mann= 4 , 1 , 0
  3567.5     .14       0    4962    .048       0    5038     .14       0
  5779.9      10       0
Bank Sta=4962,5038
Exp/Cntr=0.3,0.1

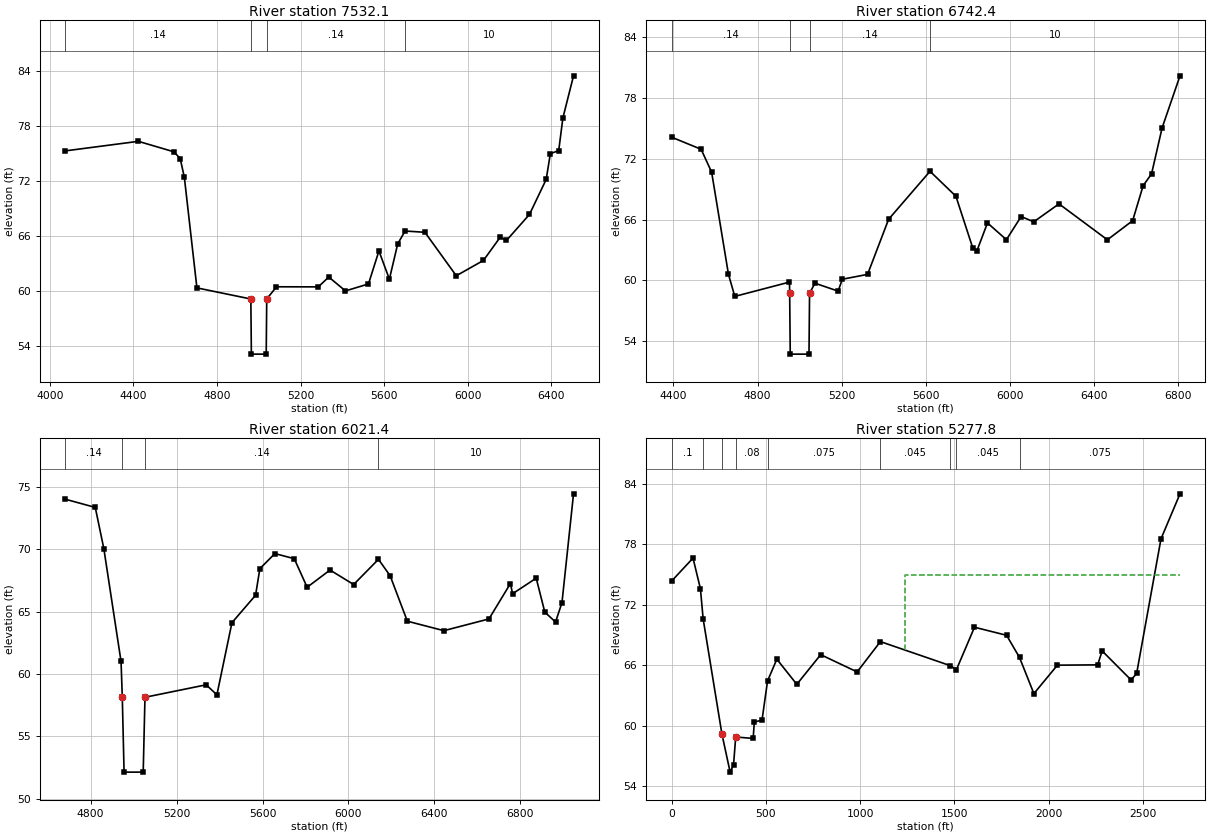
Type RM Length L Ch R = 1 ,7532.1  ,789.7,789.7,789.7
BEGIN DESCRIPTION:
Black Creek DS 4.0
END DESCRIPTION:
XS GIS Cut Line= 3
        .8561229        .1527134        .8656037        .1174793
        .8802558        .0604911
#Sta/Elev= 30
    4074   75.28    4424   76.32    4594   75.18    4624   74.45    4644   72.39
    4704   60.37    4962   59.16  4964.5   53.16  5035.5   53.16    5038   59.16
  5084.7   60.49  5284.7   60.48  5334.7   61.55  5414.7   60.04  5524.7    60.8
  5574.7   64.39  5624.7   61.32  5664.7   65.17  5699.9   66.56  5794.7   66.42
  5944.7   61.69  6074.7   63.36  6154.7   65.88  6184.7   65.53  6294.7   68.36
  6374.7   72.17  6394.7   74.98  6434.7   75.31  6454.7   78.87  6505.6   83.45
#Mann= 4 , 1 , 0
    4074     .14       0    4962    .048       0    5038     .14       0
  5699.9      10       0
Bank Sta=4962,5038
Exp/Cntr=0.3,0.1

Type RM Length L Ch R = 1 ,6742.4  ,721,721,721
BEGIN DESCRIPTION:
Black Creek DS 3.0
END DESCRIPTION:
XS GIS Cut Line= 3
        .8904589        .1578117        .8904589        .1338479
        .8905985        .0630768
#Sta/Elev= 30
  4391.8   74.12  4531.8   72.93  4581.8   70.67  4661.8    60.6  4691.8   58.43
  4951.8   59.84  4952.7   58.74 4955.45   52.74 5044.55   52.74  5047.3   58.74
    5073   59.73    5183   58.95    5203   60.12    5323    60.6    5423   66.03
  5619.9   70.76    5743    68.3    5823   63.21    5843   62.93    5893   65.67
    5983   64.02    6053    66.3    6113   65.78    6233   67.55    6463   64.01
    6583   65.89    6633   69.34    6673   70.51    6723   75.03  6808.2   80.17
#Mann= 4 , 1 , 0
  4391.8     .14       0  4952.7    .047       0  5047.3     .14       0
  5619.9      10       0
Bank Sta=4952.7,5047.3
Exp/Cntr=0.3,0.1

Type RM Length L Ch R = 1 ,6021.4  ,743.6,743.6,743.6
BEGIN DESCRIPTION:
Black Creek DS 2.0
END DESCRIPTION:
XS GIS Cut Line= 4
        .9141454        .1538856        .9158002        .1411985
         .914697        .1092051        .9003551        .0634215
#Sta/Elev= 30
  4681.4   74.02  4821.4   73.36  4861.4   70.04  4941.4   61.01  4947.2   58.14
 4955.45   52.14 5044.55   52.14  5052.8   58.14  5337.7   59.14  5387.7   58.34
  5457.7   64.12  5567.7   66.32  5587.7   68.45  5657.7   69.66  5747.8   69.25
  5807.8   66.96  5914.3   68.34  6024.3   67.18  6139.9    69.2  6194.3   67.88
  6274.3   64.24  6444.3   63.48  6654.3   64.42  6754.3   67.26  6764.3   66.44
  6874.3   67.69  6914.3   64.97  6964.3   64.17  6994.3   65.73  7048.1   74.45
#Mann= 4 , 1 , 0
  4681.4     .14       0  4947.2    .047       0  5052.8     .14       0
  6139.9      10       0
Bank Sta=4947.2,5052.8
Exp/Cntr=0.3,0.1

Type RM Length L Ch R = 1 ,5277.8  ,0,0,0
BEGIN DESCRIPTION:
TIE IN WITH xs 5170 FROM DTL MODEL
END DESCRIPTION:
#Sta/Elev= 30
       0   74.36  113.24   76.63  152.55   73.59  166.95   70.61  266.74   59.18
  310.15   55.42  328.27   56.14  339.75    58.9  432.31   58.76  438.57   60.39
  479.33   60.57  508.66   64.46  558.03   66.61  663.83   64.12  790.72   67.06
  984.03   65.35  1107.468.35486 1477.16   65.98 1511.14   65.59 1606.61   69.78
 1776.98   68.98 1845.57   66.78 1921.79    63.2 2046.61   66.02 2260.19   66.05
 2283.93   67.43  2437.7   64.55 2467.07   65.21 2596.18   78.54 2697.02      83
#Mann= 9 ,-1 , 0
       0      .1       0  166.95     .08       0  266.74     .05       0
  339.75     .08       0  508.66    .075       0  1107.4    .045       0
 1477.16    .075       0 1511.14    .045       0 1845.57    .075       0
#XS Ineff= 2 , 0
       0                 1235.32       0      75
Permanent Ineff=
       F       F
Bank Sta=266.74,339.75
Exp/Cntr=0.3,0.1

Chan Stop Cuts=-1
Use User Specified Reach Order=0
User Specified Reach Order=Black Ck DS     ,Reach - 1