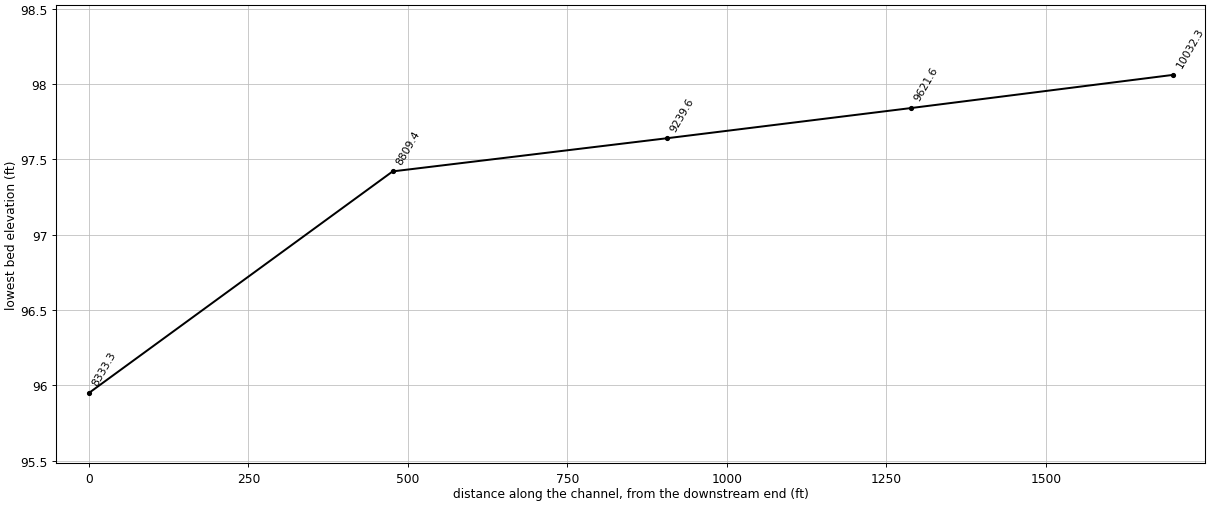
--- Black_Creek_Trib_030114.prj (project) ---

Proj Title=Black Creek Tributary
Current Plan=p02
Default Exp/Contr=0.3,0.1
English Units
Geom File=g01
Flow File=f01
Flow File=f02
Plan File=p01
Plan File=p02
Y Axis Title=Elevation
X Axis Title(PF)=Main Channel Distance
X Axis Title(XS)=Station
BEGIN DESCRIPTION:
NEUSE RIVER BASIN
Little Contentnea Creek Sub-basin
BLACK CREEK TRIBUTARY
(Flood Hazard, Floodway) Model
Prepared by: Andrew J. Bonner   Date: 11/5/2002
Watershed Concepts
3333 Regency Pkwy
Cary, North Carolina 27511
END DESCRIPTION:
DSS Export Rating Curves= 0
DSS Export Rating Curve Sorted= 0
DSS Export Volume Flow Curves= 0
DXF OffsetX= 0
DXF OffsetY= 0
DXF ScaleX= 1
DXF ScaleY= 10

--- Black_Creek_Trib_030114.p02 (plan) ---

Plan Title=Multi_Profile
Program Version=4.00
Short Identifier=Multi_Profile
Geom File=g01
Flow File=f02
Subcritical Flow
K Sum by GR= 0
Std Step Tol= 0.01
Critical Tol= 0.01
Num of Std Step Trials= 20
Max Error Tol= 0.3
Flow Tol Ratio= 0.001
Split Flow NTrial= 30
Split Flow Tol= 0.02
Split Flow Ratio= 0.02
Log Output Level= 0
Friction Slope Method= 1
Unsteady Friction Slope Method= 2
Unsteady Bridges Friction Slope Method= 1
Parabolic Critical Depth
Global Vel Dist= 0 , 0 , 0
Global Log Level= 0
CheckData=True
Encroach Param=-1 ,10,10, 2
Computation Interval=1HOUR
Output Interval=1HOUR
Run HTab= 0
Run UNet= 0
Run PostProcess= 0
Run WQNet= 0
UNET Theta= 1
UNET Theta Warmup= 1
UNET ZTol= 0.02
UNET ZSATol= 0.1
UNET MxIter= 20
UNET MaxInSteps= 20
UNET DtIC= 0
UNET DtMin= 0
UNET MaxCRTS= 20
UNET WFStab= 2
UNET SFStab= 1
UNET WFX= 1
UNET SFX= 1
UNET DSS MLevel= 4
UNET DZMax Abort= 100
UNET Convert EG Bridges=-1
UNET Use Existing IB Tables=-1
UNET Froude Reduction=False
UNET Froude Limit= 1
UNET Froude Power= 10
UNET Time Slicing=0,0, 5
Instantaneous Interval=1HOUR
Write IC File= 0
Echo Input=False
Echo Output=False
Write Detailed= 0
Detailed Automatic Start=False, 10
WQ ULTIMATE=-1
WQ Max Comp Step=1HOUR
WQ Output Interval=15MIN
WQ Output Selected Increments= 0
WQ Output face flow=0
WQ Output face velocity=0
WQ Output face area=0
WQ Output face dispersion=0
WQ Output cell volume=0
WQ Output cell surface area=0
WQ Output cell continuity=0
WQ Output face conc=0
WQ Output face dconc_dx=0
WQ Output face courant=0
WQ Output face peclet=0
WQ Output face adv mass=0
WQ Output face disp mass=0
WQ Output cell mass=0
WQ Output cell source sink temp=0
WQ Output cell source sink nsm=0
WQ Output MaxMinRange=-1
WQ Daily Max Min Mean=-1
WQ Daily Range=0
WQ Daily Time=0
WQ Create Restart=0
WQ Fixed Restart=0
WQ System Summary=False
Sorting and Armoring Iterations= 10
XS Update Threshold= 0.02
Hydraulics Update Threshold= 0.02
Energy Slope Method= 1
Volume Change Method= 0
XS Weighting Method= 0
Number of US Weighted Cross Sections= 1
Number of DS Weighted Cross Sections= 1
Upstream XS Weight=0.25
Main XS Weight=0.5
Downstream XS Weight=0.25
Number of DS XS's Weighted with US Boundary= 1
Upstream Boundary Weight= 1
Weight of XSs Associated with US Boundary= 0
Number of US XS's Weighted with DS Boundary= 1
Downstream Boundary Weight= 0.5
Weight of XSs Associated with DS Boundary= 0.5
Sediment Output Level= 4
Mass or Volume Output= 0
Output Increment Type= 1
Profile and TS Output Increment= 10
XS Output Flag= 0
XS Output Increment= 10
Disregard all LS=0
Disregard all Conn=0
Disregard all Breaches=0
Disregard all Pumps=0

--- Black_Creek_Trib_030114.p01 (plan) ---

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Plan Title=100 Year Single
Short Identifier=Multi_Profil
Geom File=g01
Flow File=f01
Encroach River=Black Creek Trib
Encroach Reach=Reach - 1
Encroach Node=10032.3
       4      .7
Encroach Node=9621.6
       4      .7
Encroach Node=9239.6
       4      .7
Encroach Node=8809.4
       4      .7
Encroach Node=8333.3
       1  4985.9 5161.35

--- Black_Creek_Trib_030114.f02 (steady flow) ---

Flow Title=Multi_Profile
Program Version=4.00
Number of Profiles= 7
Profile Names=10yr,25yr,50yr,500yr,100yr-10%,100yr-20%,100yr-35%
River Rch & RM=Black Creek Trib,Reach - 1       ,10032.3
     682     955    1194    2228    1627    2073    2532
Boundary for River Rch & Prof#=Black Creek Trib,Reach - 1       , 1
Up Type= 0
Dn Type= 1
Dn Known WS=101.97
Boundary for River Rch & Prof#=Black Creek Trib,Reach - 1       , 2
Up Type= 0
Dn Type= 1
Dn Known WS=102.43
Boundary for River Rch & Prof#=Black Creek Trib,Reach - 1       , 3
Up Type= 0
Dn Type= 1
Dn Known WS=102.79
Boundary for River Rch & Prof#=Black Creek Trib,Reach - 1       , 4
Up Type= 0
Dn Type= 1
Dn Known WS=103.96
Boundary for River Rch & Prof#=Black Creek Trib,Reach - 1       , 5
Up Type= 0
Dn Type= 1
Dn Known WS=103.31
Boundary for River Rch & Prof#=Black Creek Trib,Reach - 1       , 6
Up Type= 0
Dn Type= 1
Dn Known WS=103.8
Boundary for River Rch & Prof#=Black Creek Trib,Reach - 1       , 7
Up Type= 0
Dn Type= 1
Dn Known WS=104.25
DSS Import GetInterval= 0
DSS Import GetPeak= 0
DSS Import FillOption= 0

--- Black_Creek_Trib_030114.f01 (steady flow) ---

Flow Title= 100 Year Single
Program Version=4.00
Number of Profiles= 2
Profile Names=100-Year,AFW
River Rch & RM=Black Creek Trib,Reach - 1       ,10032.3
    1462    1462
Boundary for River Rch & Prof#=Black Creek Trib,Reach - 1       , 1
Up Type= 0
Dn Type= 1
Dn Known WS=103.12
Boundary for River Rch & Prof#=Black Creek Trib,Reach - 1       , 2
Up Type= 0
Dn Type= 1
Dn Known WS=104.09
DSS Import GetInterval= 0
DSS Import GetPeak= 0
DSS Import FillOption= 0

--- Black_Creek_Trib_030114.g01 (geometry) ---

Geom Title=Geom 01 by CodeH2 for Windows
Program Version=4.00

River Reach=Black Creek Trib,Reach - 1
Reach XY= 2
             0.5            0.95             0.5            0.05

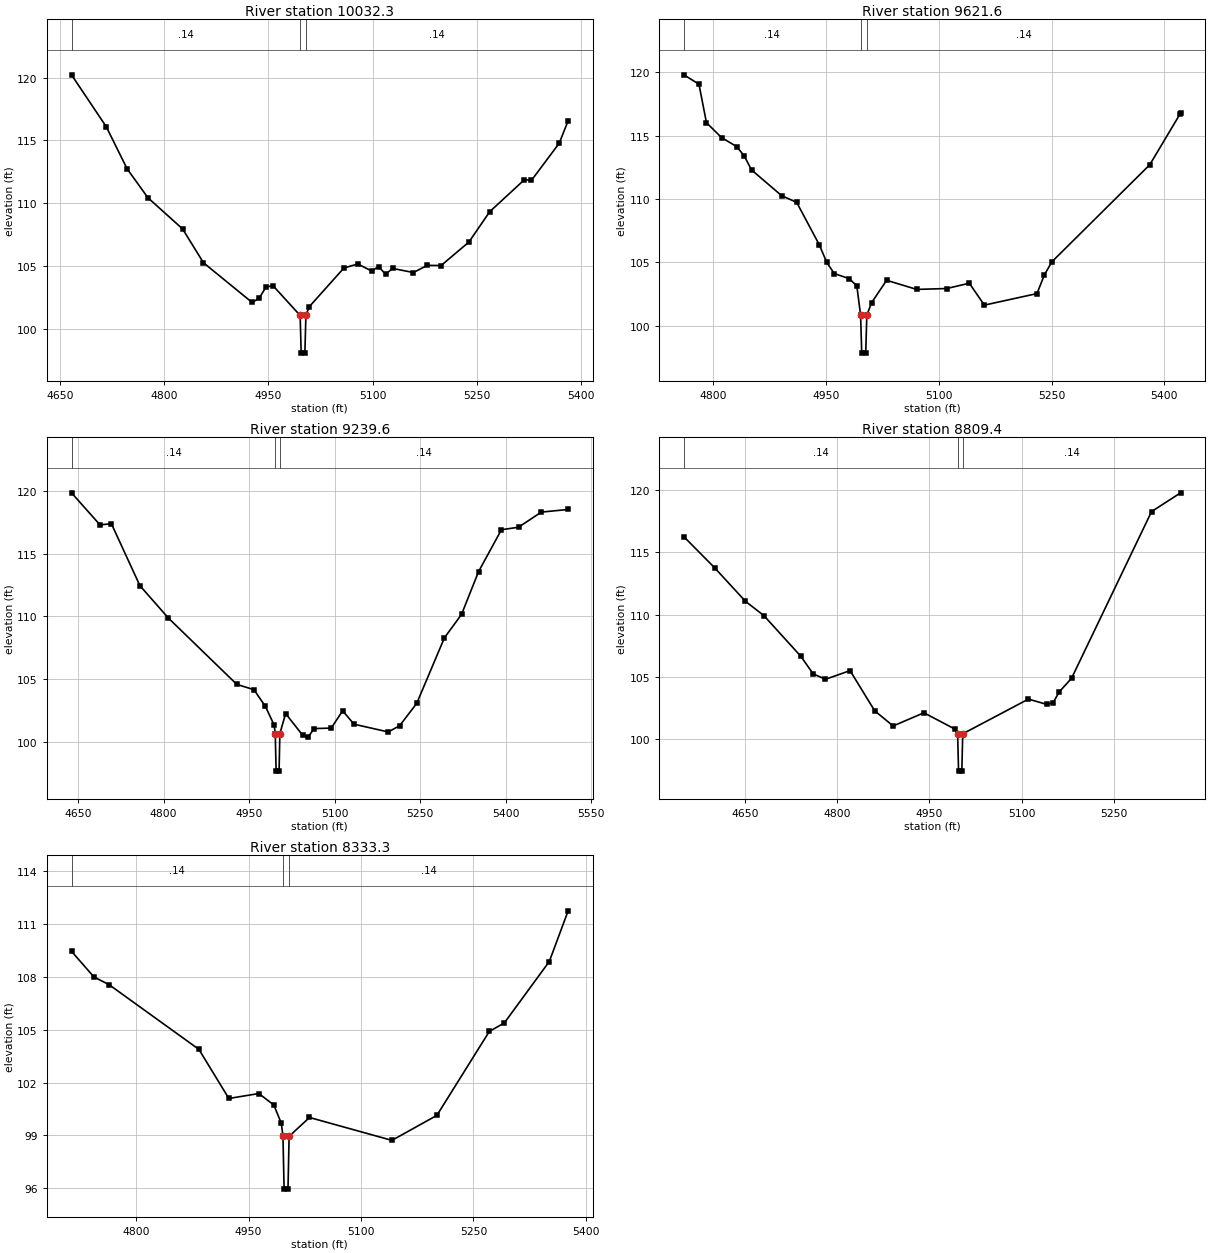
Type RM Length L Ch R = 1 ,10032.3 ,410.7,410.7,410.7
BEGIN DESCRIPTION:
Black Creek Tributary 4.0
END DESCRIPTION:
#Sta/Elev= 30
  4666.6  120.23  4716.6   116.1  4746.6  112.75  4776.6  110.44  4826.6  107.95
  4856.6  105.26  4926.6   102.1  4936.6  102.42  4946.6  103.32  4956.6  103.44
  4995.8  101.06  4997.3   98.06  5002.6   98.06  5004.1  101.06  5008.8  101.75
  5058.8  104.84  5078.8  105.16  5098.8   104.6  5108.8  104.96  5118.8  104.34
  5128.8  104.81  5158.8  104.48  5178.8  105.05  5198.8  105.04  5238.8  106.91
  5268.8  109.33  5318.8  111.88  5328.8  111.82  5368.8  114.78  5381.7  116.58
#Mann= 3 , 1 , 0
  4666.6     .14       0  4995.8    .047       0  5004.1     .14       0
Bank Sta=4995.8,5004.1
XS Rating Curve= 0 ,0
Exp/Cntr=0.3,0.1

Type RM Length L Ch R = 1 ,9621.6  ,382,382,382
BEGIN DESCRIPTION:
Black Creek Tributary 3.0
END DESCRIPTION:
#Sta/Elev= 30
  4760.9  119.81  4780.9  119.07  4790.9  116.03  4810.9  114.86  4830.9  114.15
  4840.9  113.43  4850.9   112.3  4890.9  110.27  4910.9  109.74  4940.9   106.4
  4950.9     105  4960.9  104.12  4980.9  103.72  4990.9  103.14  4995.9  100.84
  4997.4   97.84  5002.7   97.84  5004.2  100.84  5010.5  101.82  5030.5  103.59
  5070.5  102.87  5110.5  102.94  5140.5  103.36  5160.5  101.63  5230.5  102.54
  5240.5  104.04  5250.5  105.06  5380.5  112.71  5420.5  116.69  5421.5  116.77
#Mann= 3 , 1 , 0
  4760.9     .14       0  4995.9    .047       0  5004.2     .14       0
Bank Sta=4995.9,5004.2
XS Rating Curve= 0 ,0
Exp/Cntr=0.3,0.1

Type RM Length L Ch R = 1 ,9239.6  ,430.2,430.2,430.2
BEGIN DESCRIPTION:
Black Creek Tributary 2.5
END DESCRIPTION:
#Sta/Elev= 30
  4638.5  119.88  4688.5  117.32  4708.5  117.41  4758.5  112.46  4808.5  109.87
  4928.5  104.57  4958.5  104.15  4978.5  102.82  4994.1  101.31  4995.9  100.64
  4997.4   97.64  5002.6   97.64    5004  100.64  5014.1  102.24  5044.1   100.5
  5054.1   100.4  5064.1  101.04  5094.1  101.08  5114.1  102.46  5134.1  101.39
  5194.1  100.77  5214.1  101.27  5244.1  103.06  5292.6  108.29  5322.6  110.16
  5352.6  113.59  5392.6  116.93  5422.6  117.13  5462.6  118.34  5509.7  118.55
#Mann= 3 , 1 , 0
  4638.5     .14       0  4995.9    .047       0    5004     .14       0
Bank Sta=4995.9,5004
XS Rating Curve= 0 ,0
Exp/Cntr=0.3,0.1

Type RM Length L Ch R = 1 ,8809.4  ,476.1,476.1,476.1
BEGIN DESCRIPTION:
Black Creek Tributary 2.0
END DESCRIPTION:
#Sta/Elev= 23
    4551  116.26    4601  113.76    4651  111.07    4681  109.92    4741  106.65
    4761  105.24    4781   104.8    4821   105.5    4861  102.27    4891  101.05
    4941  102.11    4991  100.81  4995.8  100.42  4997.3   97.42  5002.6   97.42
  5004.1  100.42  5110.9  103.21  5140.9  102.78  5150.9  102.92  5160.9  103.79
  5180.9  104.88  5310.9  118.28  5358.1  119.79
#Mann= 3 , 1 , 0
    4551     .14       0  4995.8    .047       0  5004.1     .14       0
Bank Sta=4995.8,5004.1
XS Rating Curve= 0 ,0
Exp/Cntr=0.3,0.1

Type RM Length L Ch R = 1 ,8333.3  ,160.5,160.5,160.5
BEGIN DESCRIPTION:
Black Creek Tributary 1.0
END DESCRIPTION:
#Sta/Elev= 19
  4713.7  109.46  4743.7     108  4763.7  107.57  4883.7  103.89  4923.7   101.1
  4963.7  101.38  4983.7  100.73  4993.7   99.69  4995.9   98.95  4997.4   95.95
  5002.6   95.95  5004.1   98.95  5031.3  100.02  5141.3   98.72  5201.3  100.14
  5271.3  104.91  5291.3  105.39  5351.3  108.88  5376.5  111.76
#Mann= 3 , 1 , 0
  4713.7     .14       0  4995.9    .047       0  5004.1     .14       0
Bank Sta=4995.9,5004.1
XS Rating Curve= 0 ,0
Exp/Cntr=0.3,0.1

Chan Stop Cuts=-1
Use User Specified Reach Order=0