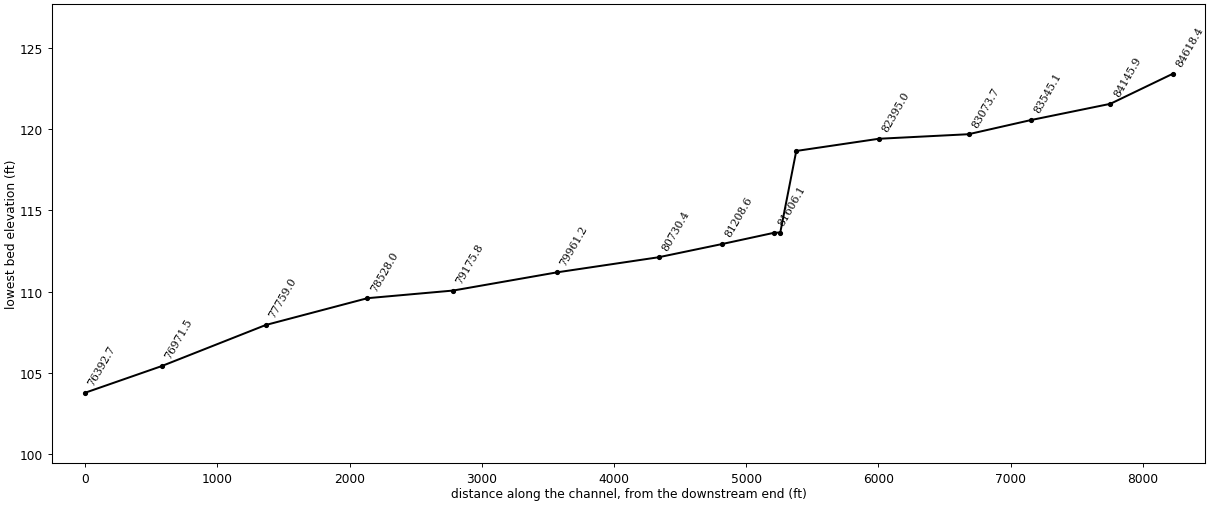
--- Black_Creek_US_FINAL.prj (project) ---

Proj Title=Black Creek US
Current Plan=p02
Default Exp/Contr=0.3,0.1
English Units
Geom File=g01
Flow File=f01
Flow File=f02
Plan File=p01
Plan File=p02
Y Axis Title=Elevation
X Axis Title(PF)=Main Channel Distance
X Axis Title(XS)=Station
BEGIN DESCRIPTION:
NEUSE RIVER BASIN
Little Contentnea Creek Sub-basin
BLACK CREEK 1
(Flood Hazard, Floodway) Model
Prepared by: Andrew J. Bonner   Date: 11/21/2002
Watershed Concepts
3333 Regency Pkwy
Cary, North Carolina 27511
END DESCRIPTION:
DSS Export Rating Curves= 0
DSS Export Rating Curve Sorted= 0
DSS Export Volume Flow Curves= 0
DXF OffsetX= 0
DXF OffsetY= 0
DXF ScaleX= 1
DXF ScaleY= 10

--- Black_Creek_US_FINAL.p02 (plan) ---

Plan Title=Multi_Profile
Program Version=4.00
Short Identifier=Multi_Profile
Geom File=g01
Flow File=f02
Subcritical Flow
K Sum by GR= 0
Std Step Tol= 0.01
Critical Tol= 0.01
Num of Std Step Trials= 20
Max Error Tol= 0.3
Flow Tol Ratio= 0.001
Split Flow NTrial= 30
Split Flow Tol= 0.02
Split Flow Ratio= 0.02
Log Output Level= 0
Friction Slope Method= 1
Unsteady Friction Slope Method= 2
Unsteady Bridges Friction Slope Method= 1
Parabolic Critical Depth
Global Vel Dist= 0 , 0 , 0
Global Log Level= 0
CheckData=True
Encroach Param=-1 ,10,10, 2
Computation Interval=1HOUR
Output Interval=1HOUR
Run HTab= 0
Run UNet= 0
Run PostProcess= 0
Run WQNet= 0
UNET Theta= 1
UNET Theta Warmup= 1
UNET ZTol= 0.02
UNET ZSATol= 0.1
UNET MxIter= 20
UNET MaxInSteps= 20
UNET DtIC= 0
UNET DtMin= 0
UNET MaxCRTS= 20
UNET WFStab= 2
UNET SFStab= 1
UNET WFX= 1
UNET SFX= 1
UNET DSS MLevel= 4
UNET DZMax Abort= 100
UNET Convert EG Bridges=-1
UNET Use Existing IB Tables=-1
UNET Froude Reduction=False
UNET Froude Limit= 1
UNET Froude Power= 10
UNET Time Slicing=0,0, 5
Instantaneous Interval=1HOUR
Write IC File= 0
Echo Input=False
Echo Output=False
Write Detailed= 0
Detailed Automatic Start=False, 10
WQ ULTIMATE=-1
WQ Max Comp Step=1HOUR
WQ Output Interval=15MIN
WQ Output Selected Increments= 0
WQ Output face flow=0
WQ Output face velocity=0
WQ Output face area=0
WQ Output face dispersion=0
WQ Output cell volume=0
WQ Output cell surface area=0
WQ Output cell continuity=0
WQ Output face conc=0
WQ Output face dconc_dx=0
WQ Output face courant=0
WQ Output face peclet=0
WQ Output face adv mass=0
WQ Output face disp mass=0
WQ Output cell mass=0
WQ Output cell source sink temp=0
WQ Output cell source sink nsm=0
WQ Output MaxMinRange=-1
WQ Daily Max Min Mean=-1
WQ Daily Range=0
WQ Daily Time=0
WQ Create Restart=0
WQ Fixed Restart=0
WQ System Summary=False
Sorting and Armoring Iterations= 10
XS Update Threshold= 0.02
Hydraulics Update Threshold= 0.02
Energy Slope Method= 1
Volume Change Method= 0
XS Weighting Method= 0
Number of US Weighted Cross Sections= 1
Number of DS Weighted Cross Sections= 1
Upstream XS Weight=0.25
Main XS Weight=0.5
Downstream XS Weight=0.25
Number of DS XS's Weighted with US Boundary= 1
Upstream Boundary Weight= 1
Weight of XSs Associated with US Boundary= 0
Number of US XS's Weighted with DS Boundary= 1
Downstream Boundary Weight= 0.5
Weight of XSs Associated with DS Boundary= 0.5
Sediment Output Level= 4
Mass or Volume Output= 0
Output Increment Type= 1
Profile and TS Output Increment= 10
XS Output Flag= 0
XS Output Increment= 10
Disregard all LS=0
Disregard all Conn=0
Disregard all Breaches=0
Disregard all Pumps=0

--- Black_Creek_US_FINAL.p01 (plan) ---

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Plan Title=100 Year Single
Short Identifier=Plan01
Geom File=g01
Flow File=f01
Encroach River=Black Ck US
Encroach Reach=Reach - 1
Encroach Node=84618.4
       4      .7
Encroach Node=84145.9
       4      .7
Encroach Node=83545.1
       4      .7
Encroach Node=83073.7
       4      .7
Encroach Node=82395.0
       4      .7
Encroach Node=81771.0
       1    4815    5203
Encroach Node=81650.1
       1    4940    5203
Encroach Node=81606.1
       1    4940    5203
Encroach Node=81208.6
       4      .7
Encroach Node=80730.4
       4      .7
Encroach Node=79961.2
       4      .7
Encroach Node=79175.8
       4      .7
Encroach Node=78528.0
       4      .7
Encroach Node=77759.0
       4      .7
Encroach Node=76971.5
       4      .7
Encroach Node=76392.7
       4      .7
Encroach Node=75721.6
       1    4850    5200
Encroach Node=74999.3
       1    4825    5125
Encroach Node=74467.7
       1    4600    5030
Encroach Node=73750.6
       4      .7
Encroach Node=73286.3
       4      .7
Encroach Node=73241.3
       4      .7
Encroach Node=72732.8
       4      .7
Encroach Node=72169.2
       4      .7
Encroach Node=71638.5
       4      .7
Encroach Node=71148.2
       4      .7
Encroach Node=70684.9
       4      .7
Encroach Node=70247.2
       4      .7
Encroach Node=69332.9
       1    4500    5250
Encroach Node=68725.6
       1    4600    5300
Encroach Node=68090.4
       1    4600    5300
Encroach Node=67467.7
       4      .7
Encroach Node=66679.7
       4      .7
Encroach Node=66140.7
       4      .7
Encroach Node=65670.2
       1    4900    5400
Encroach Node=65626.2
       1    4900    5400
Encroach Node=65043.1
       4      .7
Encroach Node=64391.3
       1    4700    5200
Encroach Node=63191.1
       1    4500    5350
Encroach Node=61980.8
       1    4700    5400
Encroach Node=60797.5
       4      .7
Encroach Node=60077.1
       4      .7
Encroach Node=59093.6
       1    4800    5150
Encroach Node=58157.0
       1    4500    5050
Encroach Node=57357.2
       4      .7
Encroach Node=56215.9
       1    4875    5375
Encroach Node=55330.0
       1    4750    5600
Encroach Node=54724.8
       4      .7
Encroach Node=54010.6
       1    4600    5100
Encroach Node=53158.6
       1    4800    5450
Encroach Node=52361.1
       4      .7
Encroach Node=51505.4
       1    4875    5394

--- Black_Creek_US_FINAL.f02 (steady flow) ---

Flow Title=Multi_Profile
Program Version=4.00
Number of Profiles= 7
Profile Names=10yr,25yr,50yr,500yr,100yr-10%,100yr-20%,100yr-35%
River Rch & RM=Black Ck US,Reach - 1       ,84618.4
     630     883    1106    2070    1505    1929    2357
River Rch & RM=Black Ck US,Reach - 1       ,83545.1
    1107    1530    1901    3469    2496    3199    3908
River Rch & RM=Black Ck US,Reach - 1       ,79175.8
    1171    1616    2005    3650    2623    3362    4108
River Rch & RM=Black Ck US,Reach - 1       ,77759.0
    1234    1701    2109    3830    2750    3525    4307
River Rch & RM=Black Ck US,Reach - 1       ,74999.3
    1343    1846    2286    4137    2965    3801    4644
River Rch & RM=Black Ck US,Reach - 1       ,73286.3
    1442    1979    2448    4414    3161    4051    4949
River Rch & RM=Black Ck US,Reach - 1       ,66679.7
    2561    3464    4248    7463    5288    6777    8281
River Rch & RM=Black Ck US,Reach - 1       ,63191.1
    2610    3529    4326    7595    5380    6895    8424
River Rch & RM=Black Ck US,Reach - 1       ,58157.0
    2826    3813    4669    8168    5777    7404    9046
River Rch & RM=Black Ck US,Reach - 1       ,54010.6
    2944    3967    4855    8477    5991    7679    9382
Boundary for River Rch & Prof#=Black Ck US,Reach - 1       , 1
Up Type= 0
Dn Type= 1
Dn Known WS=90.97
Boundary for River Rch & Prof#=Black Ck US,Reach - 1       , 2
Up Type= 0
Dn Type= 1
Dn Known WS=91.69
Boundary for River Rch & Prof#=Black Ck US,Reach - 1       , 3
Up Type= 0
Dn Type= 1
Dn Known WS=92.26
Boundary for River Rch & Prof#=Black Ck US,Reach - 1       , 4
Up Type= 0
Dn Type= 1
Dn Known WS=94.66
Boundary for River Rch & Prof#=Black Ck US,Reach - 1       , 5
Up Type= 0
Dn Type= 1
Dn Known WS=92.97
Boundary for River Rch & Prof#=Black Ck US,Reach - 1       , 6
Up Type= 0
Dn Type= 1
Dn Known WS=94.27
Boundary for River Rch & Prof#=Black Ck US,Reach - 1       , 7
Up Type= 0
Dn Type= 1
Dn Known WS=95.33
DSS Import GetInterval= 0
DSS Import GetPeak= 0
DSS Import FillOption= 0

--- Black_Creek_US_FINAL.f01 (steady flow) ---

Flow Title= 100 Year Single
Program Version=4.00
Number of Profiles= 2
Profile Names=100-Year,AFW
River Rch & RM=Black Ck US,Reach - 1       ,84618.4
    1355    1355
River Rch & RM=Black Ck US,Reach - 1       ,83545.1
    2310    2310
River Rch & RM=Black Ck US,Reach - 1       ,79175.8
    2435    2435
River Rch & RM=Black Ck US,Reach - 1       ,77759
    2559    2559
River Rch & RM=Black Ck US,Reach - 1       ,74999.3
    2771    2771
River Rch & RM=Black Ck US,Reach - 1       ,73286.3
    2963    2963
River Rch & RM=Black Ck US,Reach - 1       ,66679.7
    5097    5097
River Rch & RM=Black Ck US,Reach - 1       ,63191.1
    5190    5190
River Rch & RM=Black Ck US,Reach - 1       ,58157
    5595    5595
River Rch & RM=Black Ck US,Reach - 1       ,54010.6
    5814    5814
River Rch & RM=Black Ck US,Reach - 1       ,51505.4
    5814    5814
Boundary for River Rch & Prof#=Black Ck US,Reach - 1       , 1
Up Type= 0
Dn Type= 1
Dn Known WS=92.88
Boundary for River Rch & Prof#=Black Ck US,Reach - 1       , 2
Up Type= 0
Dn Type= 1
Dn Known WS=93.85
DSS Import GetInterval= 0
DSS Import GetPeak= 0
DSS Import FillOption= 0

--- Black_Creek_US_FINAL.g01 (geometry) ---

Geom Title=Geom 01 by CodeH2 for Windows
Program Version=4.00

River Reach=Black Ck US     ,Reach - 1
Reach XY= 30
       0.0595906       0.1092972       0.0711231       0.0767576
       0.1070924       0.0591911       0.1435229       0.0726557
       0.1772387       0.1099547       0.2095972       0.1173385
       0.2411411       0.1401956       0.3369678       0.1247765
       0.3917489       0.1603925       0.4333372       0.1606641
       0.4586376        0.200569       0.5325299       0.2309188
       0.5589706       0.2678378       0.6144675       0.2647167
       0.6297808       0.2549906       0.6509573       0.1986347
       0.6673056        0.206981       0.6806873        0.237332
       0.7011054       0.2253985       0.7414581       0.2328481
       0.7480111       0.2201559       0.7875183       0.2089576
       0.7981933       0.1978492       0.8301645       0.2159479
       0.8386719       0.2060859       0.8607269       0.2276528
       0.8630567       0.2558308         0.88121       0.2837376
       0.8790967       0.3076347       0.9264807       0.3364563

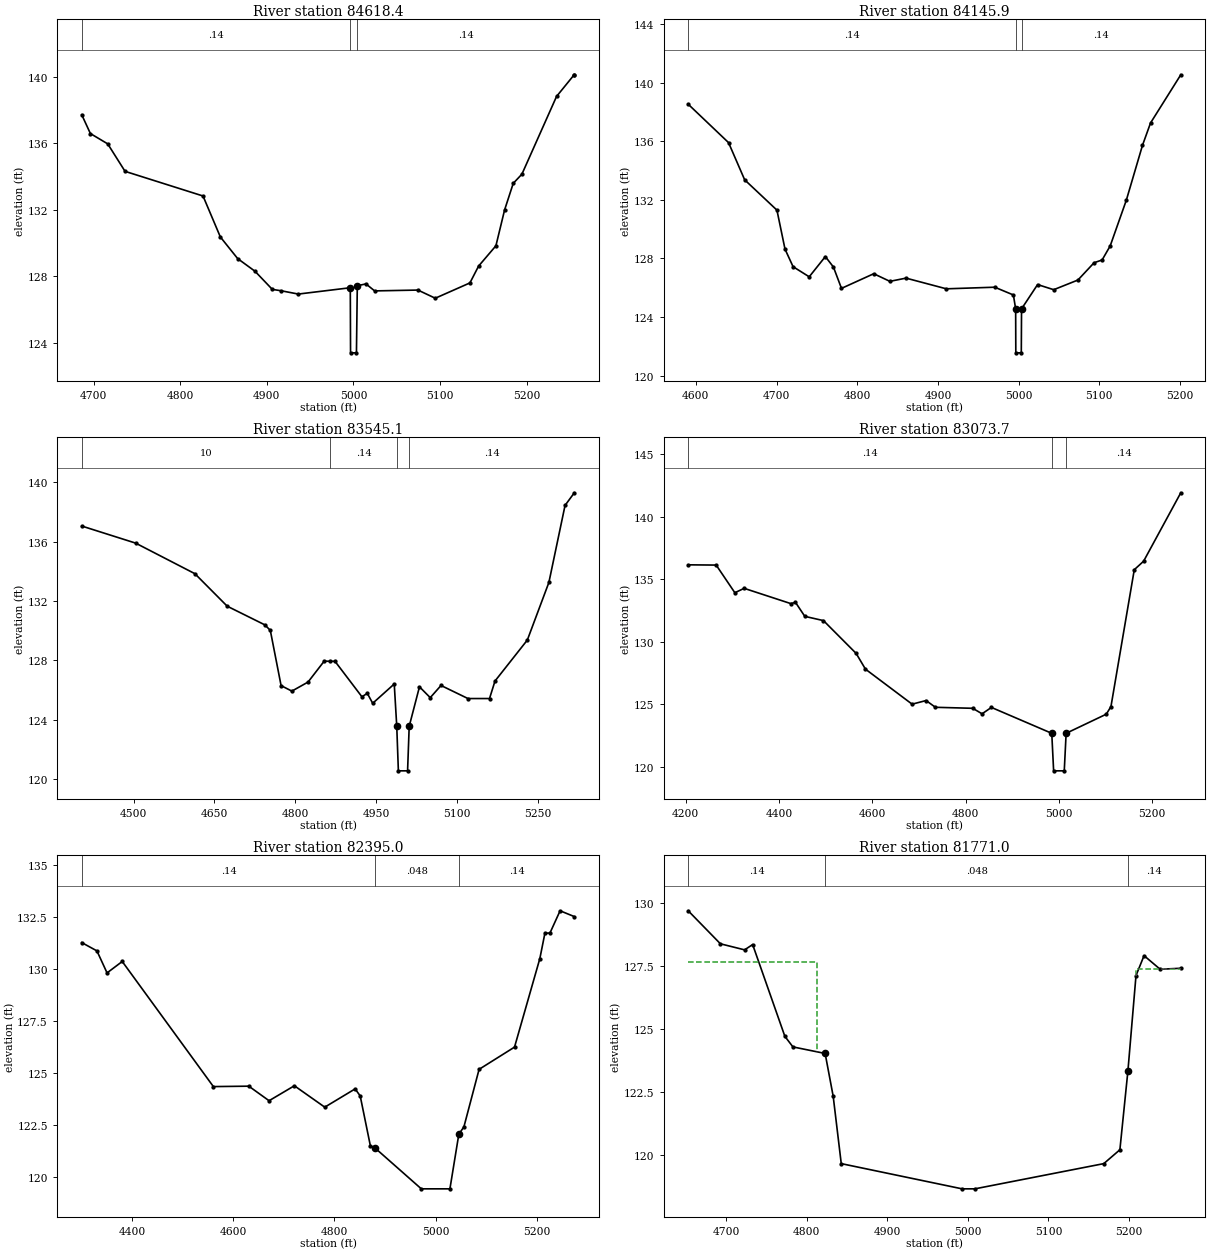
Type RM Length L Ch R = 1 ,84618.4 ,472.5,472.5,472.5
BEGIN DESCRIPTION:
Black Creek 165.0
END DESCRIPTION:
#Sta/Elev= 28
  4686.3  137.71  4696.3  136.58  4716.3  135.96  4736.3  134.31  4826.3  132.83
  4846.3  130.37  4866.3  129.07  4886.3  128.31  4906.3  127.22  4916.3  127.14
  4936.3  126.94  4996.3  127.32  4996.6  123.41  5003.4  123.41  5004.4  127.44
  5014.4  127.55  5024.4  127.13  5074.4  127.18  5094.4  126.69  5134.4  127.61
  5144.4  128.62  5164.4  129.84  5174.4  131.99  5184.4  133.59  5194.4  134.14
  5234.4  138.81  5254.4  140.09  5254.9  140.11
#Mann= 3 , 1 , 0
  4686.3     .14       0  4996.3    .048       0  5004.4     .14       0
Bank Sta=4996.3,5004.4
XS Rating Curve= 0 ,0
Exp/Cntr=0.3,0.1

Type RM Length L Ch R = 1 ,84145.9 ,600.8,600.8,600.8
BEGIN DESCRIPTION:
Black Creek 164.0
END DESCRIPTION:
#Sta/Elev= 30
  4590.5  138.53  4640.5  135.91  4660.5  133.37  4700.5   131.3  4710.5  128.64
  4720.5  127.44  4740.5  126.75  4760.5  128.13  4770.5  127.42  4780.5  125.96
  4820.5  126.96  4840.5  126.44  4860.5  126.66  4910.5  125.93  4970.5  126.04
  4993.6  125.51  4996.4  124.56  4996.6  121.56  5003.4  121.56  5003.7  124.56
  5023.6  126.22  5043.6  125.87  5073.6  126.53  5093.6  127.71  5103.6   127.9
  5113.6  128.86  5133.6  131.98  5153.6  135.72  5163.6  137.25  5201.1  140.54
#Mann= 3 , 1 , 0
  4590.5     .14       0  4996.4    .048       0  5003.7     .14       0
Bank Sta=4996.4,5003.7
XS Rating Curve= 0 ,0
Exp/Cntr=0.3,0.1

Type RM Length L Ch R = 1 ,83545.1 ,471.4,471.4,471.4
BEGIN DESCRIPTION:
Black Creek US 163.0
END DESCRIPTION:
#Sta/Elev= 30
  4403.8  137.05  4503.8   135.9  4613.8  133.84  4673.8  131.65  4743.8  130.39
  4753.8  130.02  4773.8   126.3  4793.8  125.93  4823.8  126.54  4853.8  127.95
  4864.9  127.94  4873.8  127.94  4923.8  125.55  4933.8  125.78  4943.8  125.11
  4983.8  126.41 4988.45  123.56 4991.45  120.56 5008.55  120.56 5011.55  123.56
  5030.6  126.22  5050.6  125.49  5070.6  126.31  5120.6  125.43  5160.6  125.43
  5170.8  126.61  5230.8  129.37  5270.8  133.25  5300.8  138.44    5318  139.29
#Mann= 4 , 1 , 0
  4403.8      10       0  4864.9     .14       0 4988.45    .048       0
 5011.55     .14       0
Bank Sta=4988.45,5011.55
XS Rating Curve= 0 ,0
Exp/Cntr=0.3,0.1

Type RM Length L Ch R = 1 ,83073.7 ,678.7,678.7,678.7
BEGIN DESCRIPTION:
Black Creek US 162.5
END DESCRIPTION:
#Sta/Elev= 25
  4205.2  136.16  4265.2  136.14  4305.2  133.93  4325.2  134.28  4425.2  133.06
  4435.2  133.16  4455.2  132.04  4495.2   131.7  4565.2  129.08  4585.2  127.82
  4685.2  125.02  4715.2  125.31  4735.2  124.77  4815.2  124.69  4835.2  124.25
  4855.2  124.76  4984.6  122.69  4988.6  119.69  5011.4  119.69  5015.4  122.69
  5101.5  124.22  5111.5  124.83  5161.5  135.77  5181.5  136.45  5261.2  141.92
#Mann= 3 , 1 , 0
  4205.2     .14       0  4984.6    .048       0  5015.4     .14       0
Bank Sta=4984.6,5015.4
XS Rating Curve= 0 ,0
Exp/Cntr=0.3,0.1

Type RM Length L Ch R = 1 ,82395.0 ,624,624,624
BEGIN DESCRIPTION:
Black Creek US 162.0
END DESCRIPTION:
#Sta/Elev= 24
  4300.8  131.26  4330.8  130.86  4350.8   129.8  4380.8  130.35  4560.8  124.33
  4630.8  124.35  4670.8  123.65  4720.8  124.37  4780.8  123.34  4840.8  124.22
  4850.8  123.88  4870.8  121.49  4880.8  121.36  4971.5  119.41    5028  119.41
  5045.6  122.04  5055.6  122.39  5085.6  125.16  5155.6  126.23  5205.6  130.49
  5215.6  131.71  5225.6  131.72  5245.6  132.79  5273.7  132.51
#Mann= 3 , 1 , 0
  4300.8     .14       0  4880.8    .048       0  5045.6     .14       0
Bank Sta=4880.8,5045.6
XS Rating Curve= 0 ,0
Exp/Cntr=0.5,0.3

Type RM Length L Ch R = 1 ,81771.0 ,120.9,120.9,120.9
BEGIN DESCRIPTION:
Upstream Section of Bridge/Culvert/Weir
END DESCRIPTION:
#Sta/Elev= 18
  4652.8  129.69  4692.8  128.38  4722.8  128.14  4732.8  128.35  4772.8  124.71
  4782.8  124.29  4822.8  124.03  4832.8  122.33  4842.8  119.66  4992.8  118.66
  5008.7  118.66  5168.7  119.66  5188.7  120.21  5198.7  123.35  5208.7  127.12
  5218.7  127.91  5238.7  127.37  5264.3  127.41
#Mann= 3 , 1 , 0
  4652.8     .14       0  4822.8    .048       0  5198.7     .14       0
#XS Ineff= 2 , 0
       0  4812.8  127.65  5208.7       0  127.38
Permanent Ineff=
       F       F
Bank Sta=4822.8,5198.7
XS Rating Curve= 0 ,0
Exp/Cntr=0.5,0.3

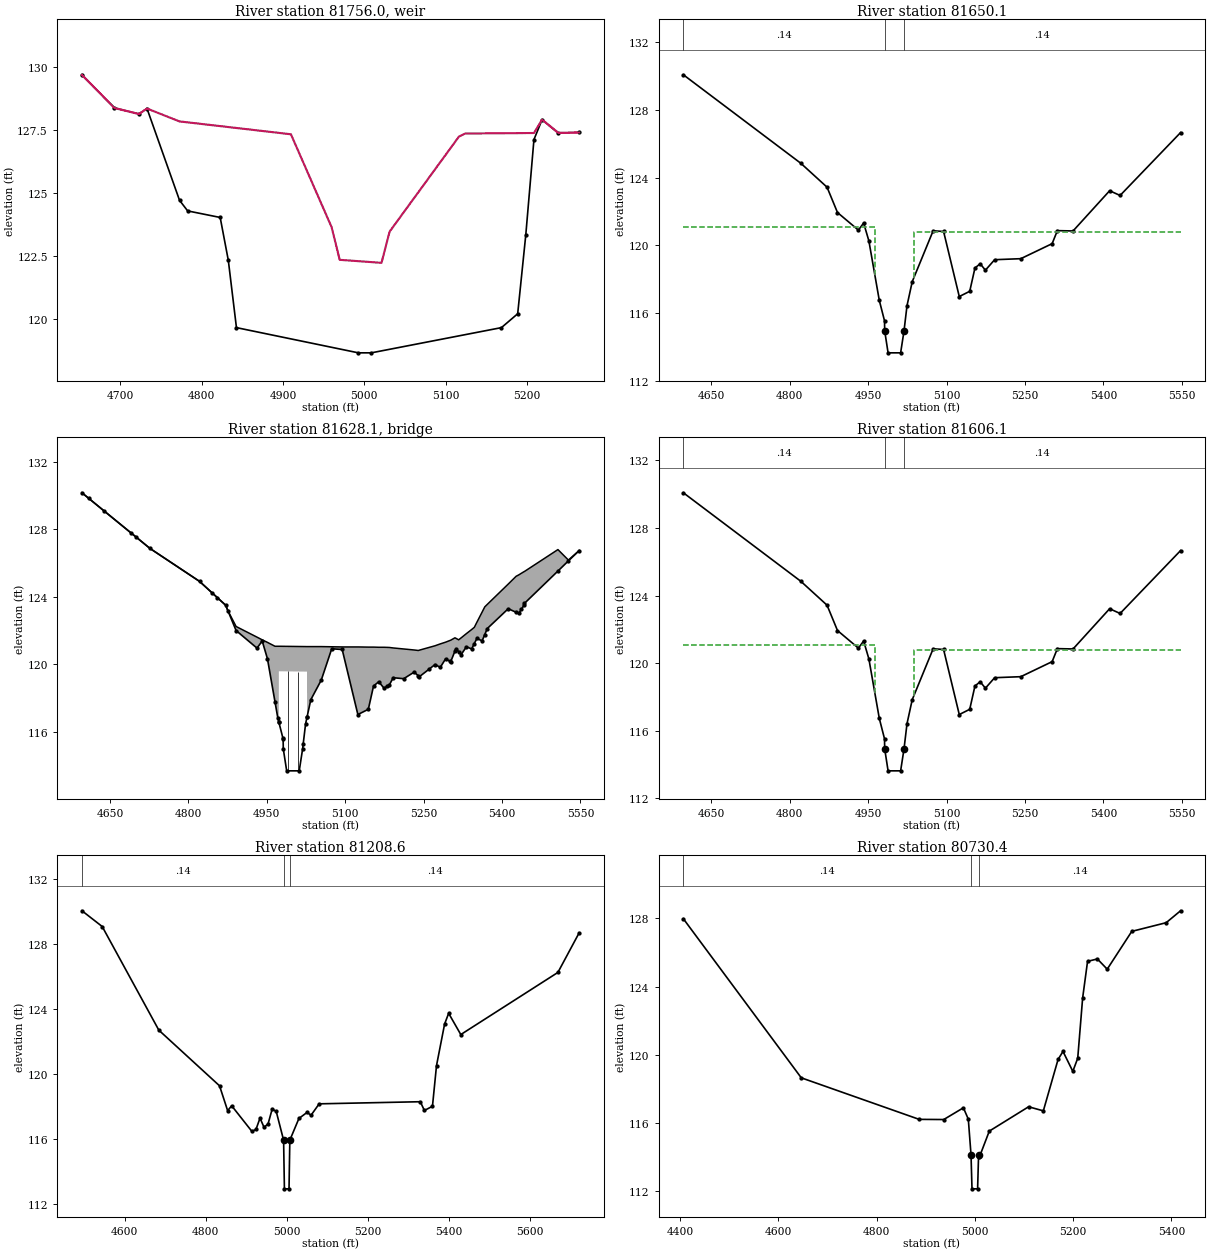
Type RM Length L Ch R = 5 ,81756.0 ,,,
BEGIN DESCRIPTION:
Newsom Millpond Dam-TOR
Structure ID: Newsom Millpond Dam
Approximate Survey Structure
END DESCRIPTION:
IW Pilot Flow=0
#Inline Weir SE= 16
  4652.8  129.68  4692.8  128.37  4722.8  128.13  4732.8  128.35  4772.8  127.84
  4909.8  127.33  4959.8  123.65  4969.8  122.35  5021.2  122.23  5031.2  123.47
  5116.5  127.24  5124.3  127.36  5208.7  127.38  5218.7  127.91  5238.7  127.39
  5264.3   127.4
IW Dist,WD,Coef,Skew,MaxSub,Min_El,Is_Ogee,SpillHt,DesHd
10,10,3,0,0.95,, 0 ,,,2,2,

Type RM Length L Ch R = 1 ,81650.1 ,44,44,44
BEGIN DESCRIPTION:
Upstream Section of Bridge/Culvert/Weir
END DESCRIPTION:
#Sta/Elev= 30
  4596.3  130.09  4821.2  124.85  4871.2  123.44  4891.2  121.94  4931.2   120.9
  4941.2  121.32  4951.2  120.27  4971.2  116.74  4981.2  115.53  4981.5  114.94
    4988  113.64    5012  113.64  5018.5  114.94  5024.2  116.43  5034.2  117.85
  5074.2  120.86  5094.2  120.82  5124.2  116.97  5144.2  117.28  5154.2  118.66
  5164.2  118.91  5174.2  118.53  5191.9  119.15  5241.9  119.21  5301.9   120.1
  5311.9  120.87  5341.9  120.85  5411.9  123.23  5431.9  122.95  5547.6  126.67
#Mann= 3 , 1 , 0
  4596.3     .14       0  4981.5    .048       0  5018.5     .14       0
#XS Ineff= 2 , 0
       0    4963   121.1    5037       0   120.8
Permanent Ineff=
       F       F
Bank Sta=4981.5,5018.5
XS Rating Curve= 0 ,0
Exp/Cntr=0.5,0.3

Type RM Length L Ch R = 3 ,81628.1 ,,,
BEGIN DESCRIPTION:
Upper BC Church Rd-TOR
Structure ID: Upper BC Church Rd
Approximate Survey Structure
END DESCRIPTION:
Bridge Culvert--1,0,-1,-1, 0
Deck Dist Width WeirC Skew NumUp NumDn MinLoCord MaxHiCord MaxSubmerge Is_Ogee
10,24,2.6,0, 53, 53, , , 0.95, 0, 1,1,,
  4596.3  4726.3  4821.2  4871.2  4875.6  4891.2  4931.2  4941.2  4951.2  4965.6
  4971.2 4972.91    4973 5026.89    5027  5034.2  5054.2  5074.2  5094.2  5124.2
  5144.2  5154.2  5164.2  5174.2  5184.2  5191.9  5211.9  5231.9  5239.9  5241.9
  5271.9  5281.9  5291.9  5301.9  5309.9  5311.9    5317  5321.9  5331.9  5341.9
    5347  5351.9  5361.9    5367  5371.9  5411.9    5427  5431.9  5441.9  5442.7
    5507    5527  5547.6
  130.15  126.86  124.91   123.5  123.17  122.24  121.61  121.45   121.3  121.07
  121.07  121.07  121.07  121.05  121.05  121.05  121.05  121.04  121.03  121.03
  121.02  121.02  121.01  121.01     121  120.97  120.91  120.85  120.82  120.84
   121.1  121.21  121.31  121.43  121.57  121.54  121.45  121.57  121.82  122.06
  122.19  122.49  123.09   123.4  123.55  124.75  125.21  125.29  125.48  125.49
  126.79  126.17  126.73
  130.15  126.86  124.91   123.5  123.17     122  120.96  121.38  120.33  117.79
   116.8  116.59  119.59  119.57  116.89  117.91  119.07  120.92  120.88  117.03
  117.34  118.72  118.97  118.59  118.77  119.21  119.15  119.54  119.32  119.27
  119.99  119.82  120.32  120.16  120.78  120.93  120.75  120.58  121.04  120.91
  121.23  121.53  121.39  121.76  122.12  123.29  123.08  123.01  123.49   123.6
  125.52  126.12  126.73
  4596.3  4726.3  4821.2  4871.2  4875.6  4891.2  4931.2  4941.2  4951.2  4965.6
  4971.2 4972.91    4973 5026.89    5027  5034.2  5054.2  5074.2  5094.2  5124.2
  5144.2  5154.2  5164.2  5174.2  5184.2  5191.9  5211.9  5231.9  5239.9  5241.9
  5271.9  5281.9  5291.9  5301.9  5309.9  5311.9    5317  5321.9  5331.9  5341.9
    5347  5351.9  5361.9    5367  5371.9  5411.9    5427  5431.9  5441.9  5442.7
    5507    5527  5547.6
  130.13  126.85   124.9  123.49  123.16  122.24  121.61  121.45   121.3  121.07
  121.07  121.07  121.07  121.05  121.05  121.05  121.05  121.04  121.03  121.03
  121.02  121.02  121.01  121.01     121  120.97  120.91  120.85  120.82  120.84
   121.1  121.21  121.31  121.43  121.57  121.54  121.45  121.57  121.82  122.06
  122.19  122.49  123.09   123.4  123.55  124.75  125.21  125.29  125.48  125.49
  126.79  126.17  126.71
   130.1  126.81  124.86  123.45  123.12  121.95  120.91  121.33  120.28  117.74
  116.75  116.54  119.54  119.52  116.84  117.86  119.02  120.87  120.83  116.98
  117.29  118.67  118.92  118.54  118.72  119.16   119.1  119.49  119.27  119.22
  119.94  119.77  120.27  120.11  120.73  120.88   120.7  120.53  120.99  120.86
  121.18  121.48  121.34  121.71  122.07  123.24  123.03  122.96  123.44  123.55
  125.47  126.07  126.68
Pier Skew, UpSta & Num, DnSta & Num=  ,4990.2, 2 ,4990.2, 2 , 0 , 0 , 0 ,,
       1       1
   112.7  120.58
       1       1
  112.65  120.53
Pier Skew, UpSta & Num, DnSta & Num=  ,5009.7, 2 ,5009.7, 2 , 0 , 0 , 0 ,,
       1       1
   112.7  120.58
       1       1
  112.65  120.53
Abutment Skew #Up #Dn= , 2 , 2
  4972.8  4980.5
  119.59  115.67
  4972.8  4980.5
  119.54  115.62
Abutment Skew #Up #Dn= , 2 , 2
  5019.5 5027.09
  115.26  119.57
  5019.5 5027.09
  115.21  119.52
BR Coef= 1 , 1 , 0 ,1.25, 0 ,,,0.8,0,2,0,
WSPro=,,,, 1 ,,,, 0 ,,,, 0 ,,,,-1 ,-1 ,-1 , 0 , 0 , 0 , 0 , 0
BR U #Sta/Elev= 71
  4596.3  130.15  4609.2  129.82  4639.2  129.06  4689.2   127.8  4699.2  127.55
  4726.3  126.86  4821.2  124.91  4845.6  124.22  4855.6  123.94  4871.2   123.5
  4875.6  123.17  4891.2     122  4931.2  120.96  4941.2  121.38  4951.2  120.33
  4965.6  117.79  4971.2   116.8 4972.91  116.59    4973  116.58  4980.5  115.67
  4981.2  115.59  4981.5     115    4988   113.7    5012   113.7  5018.5     115
  5019.5  115.26  5024.2  116.49 5026.89  116.87    5027  116.89  5034.2  117.91
  5054.2  119.07  5074.2  120.92  5094.2  120.88  5124.2  117.03  5144.2  117.34
  5154.2  118.72  5164.2  118.97  5174.2  118.59  5179.9  118.69  5184.2  118.77
  5191.9  119.21  5211.9  119.15  5231.9  119.54  5239.9  119.32  5241.9  119.27
  5259.9   119.7  5271.9  119.99  5281.9  119.82  5291.9  120.32  5299.9  120.19
  5301.9  120.16  5309.9  120.78  5311.9  120.93    5317  120.75  5321.9  120.58
  5331.9  121.04  5341.9  120.91    5347  121.23  5351.9  121.53  5361.9  121.39
    5367  121.76  5371.9  122.12  5411.9  123.29    5427  123.08  5431.9  123.01
    5437  123.25  5441.9  123.49  5442.7   123.6    5507  125.52    5527  126.12
  5547.6  126.73
BR U #Mann= 3
  4596.3     .14  4981.5    .048  5018.5     .14
BR U Banks=4981.5,5018.5
BR D #Sta/Elev= 71
  4596.3   130.1  4609.2  129.77  4639.2  129.01  4689.2  127.75  4699.2   127.5
  4726.3  126.81  4821.2  124.86  4845.6  124.17  4855.6  123.89  4871.2  123.45
  4875.6  123.12  4891.2  121.95  4931.2  120.91  4941.2  121.33  4951.2  120.28
  4965.6  117.74  4971.2  116.75 4972.91  116.54    4973  116.53  4980.5  115.62
  4981.2  115.54  4981.5  114.95    4988  113.65    5012  113.65  5018.5  114.95
  5019.5  115.21  5024.2  116.44 5026.89  116.82    5027  116.84  5034.2  117.86
  5054.2  119.02  5074.2  120.87  5094.2  120.83  5124.2  116.98  5144.2  117.29
  5154.2  118.67  5164.2  118.92  5174.2  118.54  5179.9  118.64  5184.2  118.72
  5191.9  119.16  5211.9   119.1  5231.9  119.49  5239.9  119.27  5241.9  119.22
  5259.9  119.65  5271.9  119.94  5281.9  119.77  5291.9  120.27  5299.9  120.14
  5301.9  120.11  5309.9  120.73  5311.9  120.88    5317   120.7  5321.9  120.53
  5331.9  120.99  5341.9  120.86    5347  121.18  5351.9  121.48  5361.9  121.34
    5367  121.71  5371.9  122.07  5411.9  123.24    5427  123.03  5431.9  122.96
    5437   123.2  5441.9  123.44  5442.7  123.55    5507  125.47    5527  126.07
  5547.6  126.68
BR D #Mann= 3
  4596.3     .14  4981.5    .048  5018.5     .14
BR D Banks=4981.5,5018.5
BC Design=,, 0 ,, 0 ,,,,,,
BC HTab HWMax=130.09
BC Use User HTab Curves=0
BC User HTab FreeFlow(D)= 0

Type RM Length L Ch R = 1 ,81606.1 ,397.5,397.5,397.5
BEGIN DESCRIPTION:
Downstream Section of Bridge/Culvert/Weir
END DESCRIPTION:
#Sta/Elev= 30
  4596.3  130.08  4821.2  124.84  4871.2  123.43  4891.2  121.93  4931.2  120.89
  4941.2  121.31  4951.2  120.26  4971.2  116.73  4981.2  115.52  4981.5  114.93
    4988  113.63    5012  113.63  5018.5  114.93  5024.2  116.42  5034.2  117.84
  5074.2  120.85  5094.2  120.81  5124.2  116.96  5144.2  117.27  5154.2  118.65
  5164.2   118.9  5174.2  118.52  5191.9  119.14  5241.9   119.2  5301.9  120.09
  5311.9  120.86  5341.9  120.84  5411.9  123.22  5431.9  122.94  5547.6  126.66
#Mann= 3 , 1 , 0
  4596.3     .14       0  4981.5    .048       0  5018.5     .14       0
#XS Ineff= 2 , 0
       0    4963   121.1    5037       0   120.8
Permanent Ineff=
       F       F
Bank Sta=4981.5,5018.5
XS Rating Curve= 0 ,0
Exp/Cntr=0.5,0.3

Type RM Length L Ch R = 1 ,81208.6 ,478.2,478.2,478.2
BEGIN DESCRIPTION:
Black Creek US 158.0
END DESCRIPTION:
#Sta/Elev= 30
    4494  130.07    4544   129.1    4684  122.71    4834  119.28    4854  117.75
    4864  118.05    4914  116.47    4924  116.59    4934  117.29    4944  116.72
    4954  116.94    4964  117.84    4974  117.71  4992.3  115.93  4994.3  112.93
  5005.7  112.93  5007.7  115.93  5030.2  117.27  5050.2  117.64  5060.2  117.47
  5080.2  118.17  5330.2   118.3  5340.2  117.76  5360.2  118.02  5370.2  120.53
  5390.2  123.09  5400.2  123.75  5430.2  122.44  5670.2  126.27  5722.7  128.71
#Mann= 3 , 1 , 0
    4494     .14       0  4992.3    .048       0  5007.7     .14       0
Bank Sta=4992.3,5007.7
XS Rating Curve= 0 ,0
Exp/Cntr=0.3,0.1

Type RM Length L Ch R = 1 ,80730.4 ,769.2,769.2,769.2
BEGIN DESCRIPTION:
Black Creek US 157.0
END DESCRIPTION:
#Sta/Elev= 25
  4406.8  127.98  4646.8  118.64  4886.8   116.2  4936.8  116.19  4976.8  116.88
  4986.8  116.21  4992.3  114.12  4994.3  112.12  5005.7  112.12  5007.7  114.12
  5009.5     114  5029.5  115.51  5109.5  116.94  5139.5   116.7  5169.5  119.72
  5179.5  120.19  5199.5  119.02  5209.5  119.79  5219.5  123.33  5229.5  125.48
  5249.5  125.62  5269.5  125.02  5319.5  127.24  5389.5  127.75  5418.8  128.45
#Mann= 3 , 1 , 0
  4406.8     .14       0  4992.3    .048       0  5007.7     .14       0
Bank Sta=4992.3,5007.7
XS Rating Curve= 0 ,0
Exp/Cntr=0.3,0.1

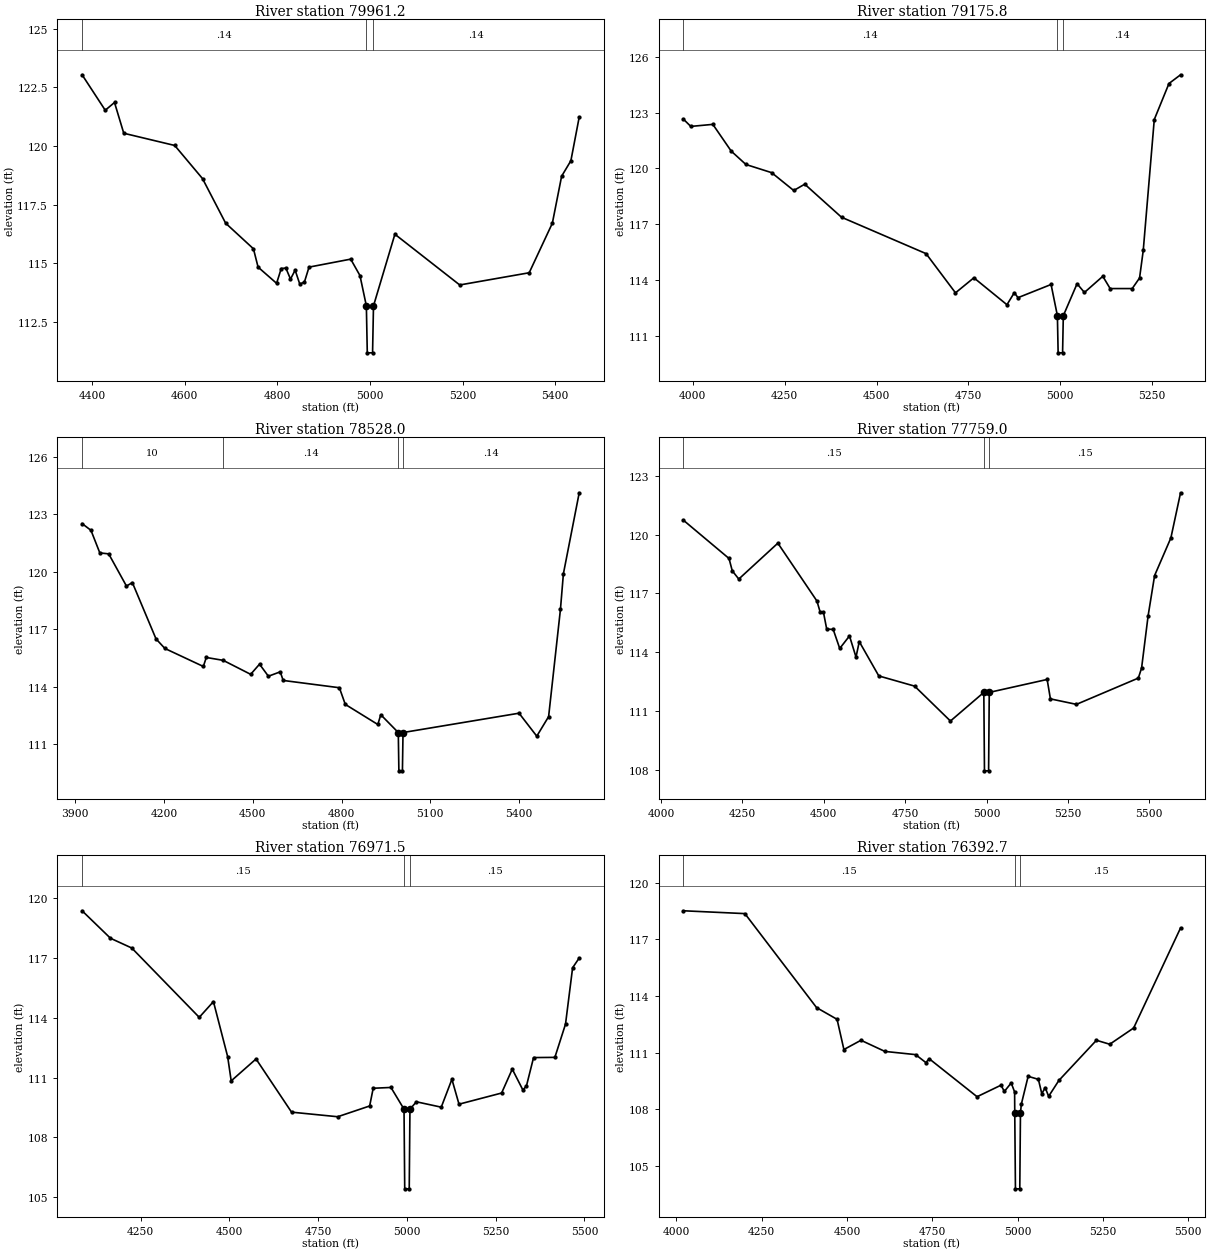
Type RM Length L Ch R = 1 ,79961.2 ,785.4,785.4,785.4
BEGIN DESCRIPTION:
Black Creek US 156.0
END DESCRIPTION:
#Sta/Elev= 30
  4378.5  123.03  4428.5  121.52  4448.5  121.85  4468.5  120.54  4578.5  120.02
  4638.5  118.61  4688.5  116.71  4748.5  115.62  4758.5  114.84  4798.5  114.15
  4808.5  114.78  4818.5   114.8  4828.5  114.33  4838.5  114.71  4848.5  114.12
  4858.5   114.2  4868.5  114.84  4958.5  115.18  4978.5  114.48  4992.3  113.19
  4994.3  111.19  5005.7  111.19  5007.7  113.19  5053.9  116.24  5193.9  114.08
  5343.9   114.6  5393.9  116.71  5413.9  118.71  5433.9  119.37  5451.9  121.23
#Mann= 3 , 1 , 0
  4378.5     .14       0  4992.3    .048       0  5007.7     .14       0
Bank Sta=4992.3,5007.7
XS Rating Curve= 0 ,0
Exp/Cntr=0.3,0.1

Type RM Length L Ch R = 1 ,79175.8 ,647.8,647.8,647.8
BEGIN DESCRIPTION:
Black Creek US 154.0
END DESCRIPTION:
#Sta/Elev= 30
  3974.8  122.65  3994.8  122.26  4054.8  122.37  4104.8  120.93  4144.8  120.21
  4214.8  119.77  4274.8  118.81  4304.8  119.15  4404.8  117.37  4634.8  115.41
  4714.8   113.3  4764.8  114.11  4854.8  112.66  4874.8  113.31  4884.8  113.04
  4974.8  113.75    4992  112.07    4994  110.07  5006.1  110.07  5008.1  112.07
  5045.5  113.79  5065.5  113.32  5115.5  114.19  5135.5  113.53  5195.5  113.53
  5215.5   114.1  5225.5  115.58  5255.5  122.63  5295.5  124.57    5327  125.04
#Mann= 3 , 1 , 0
  3974.8     .14       0    4992    .048       0  5008.1     .14       0
Bank Sta=4992,5008.1
XS Rating Curve= 0 ,0
Exp/Cntr=0.3,0.1

Type RM Length L Ch R = 1 ,78528.0 ,769,769,769
BEGIN DESCRIPTION:
Black Creek US 153.0
END DESCRIPTION:
#Sta/Elev= 30
  3922.8  122.51  3952.8  122.16  3982.8  120.98  4012.8  120.93  4072.8  119.25
  4092.8  119.43  4172.8  116.49  4202.8  115.99  4332.8  115.05  4342.8  115.52
  4399.9  115.37  4492.8  114.64  4522.8  115.17  4552.8  114.54  4592.8  114.77
  4602.8  114.32  4792.8  113.94  4812.8  113.07  4922.8  112.02  4932.8  112.53
    4992   111.6    4994   109.6    5006   109.6    5008   111.6  5400.3  112.61
  5460.3  111.41  5500.3  112.43  5540.3  118.03  5550.3  119.89  5603.8  124.12
#Mann= 4 , 1 , 0
  3922.8      10       0  4399.9     .14       0    4992    .048       0
    5008     .14       0
Bank Sta=4992,5008
XS Rating Curve= 0 ,0
Exp/Cntr=0.3,0.1

Type RM Length L Ch R = 1 ,77759.0 ,787.5,787.5,787.5
BEGIN DESCRIPTION:
Black Creek US 152.0
END DESCRIPTION:
#Sta/Elev= 30
  4069.1  120.73  4209.1  118.78  4219.1  118.15  4239.1  117.73  4359.1  119.56
  4479.1  116.61  4489.1  116.04  4499.1  116.04  4509.1  115.18  4529.1  115.16
  4549.1  114.19  4579.1  114.83  4599.1  113.75  4609.1  114.54  4669.1  112.79
  4779.1  112.27  4889.1  110.49  4991.6  111.95  4993.6  107.95  5006.3  107.95
  5008.3  111.95  5186.1  112.61  5196.1  111.62  5276.1  111.34  5466.1  112.68
  5476.1  113.19  5496.1  115.85  5516.1  117.91  5566.1  119.83  5595.8  122.13
#Mann= 3 , 1 , 0
  4069.1     .15       0  4991.6    .049       0  5008.3     .15       0
Bank Sta=4991.6,5008.3
XS Rating Curve= 0 ,0
Exp/Cntr=0.3,0.1

Type RM Length L Ch R = 1 ,76971.5 ,578.8,578.8,578.8
BEGIN DESCRIPTION:
Black Creek US 151.0
END DESCRIPTION:
#Sta/Elev= 30
  4084.9  119.38  4164.9     118  4224.9  117.51  4414.9  114.03  4454.9  114.82
  4494.9  112.06  4504.9  110.84  4574.9  111.94  4674.9  109.27  4804.9  109.04
  4894.9  109.58  4904.9  110.47  4954.9  110.51  4991.7  109.42  4993.7  105.42
  5006.4  105.42  5008.4  109.42  5026.6  109.79  5096.6  109.52  5126.6  110.92
  5146.6  109.67  5266.6  110.23  5296.6  111.43  5326.6  110.38  5336.6  110.59
  5356.6  112.01  5416.6  112.02  5446.6  113.69  5466.6  116.52  5485.2  117.01
#Mann= 3 , 1 , 0
  4084.9     .15       0  4991.7    .049       0  5008.4     .15       0
Bank Sta=4991.7,5008.4
XS Rating Curve= 0 ,0
Exp/Cntr=0.3,0.1

Type RM Length L Ch R = 1 ,76392.7 ,671.1,671.1,671.1
BEGIN DESCRIPTION:
Black Creek US 149.0
END DESCRIPTION:
#Sta/Elev= 30
  4021.2  118.51  4201.2  118.36  4411.2  113.38  4471.2  112.76  4491.2  111.16
  4541.2  111.65  4611.2  111.06  4701.2  110.89  4731.2  110.47  4741.2  110.67
  4881.2  108.66  4951.2  109.27  4961.2  108.94  4981.2  109.39  4991.2  108.91
  4991.6  107.78  4993.6  103.78  5006.3  103.78  5008.3  107.78  5010.8  108.26
  5030.8  109.74  5060.8  109.58  5070.8  108.82  5080.8  109.14  5090.8  108.68
  5120.8  109.52  5230.8  111.65  5269.8  111.44  5339.8   112.3  5477.2   117.6
#Mann= 3 , 1 , 0
  4021.2     .15       0  4991.6    .049       0  5008.3     .15       0
Bank Sta=4991.6,5008.3
XS Rating Curve= 0 ,0
Exp/Cntr=0.3,0.1