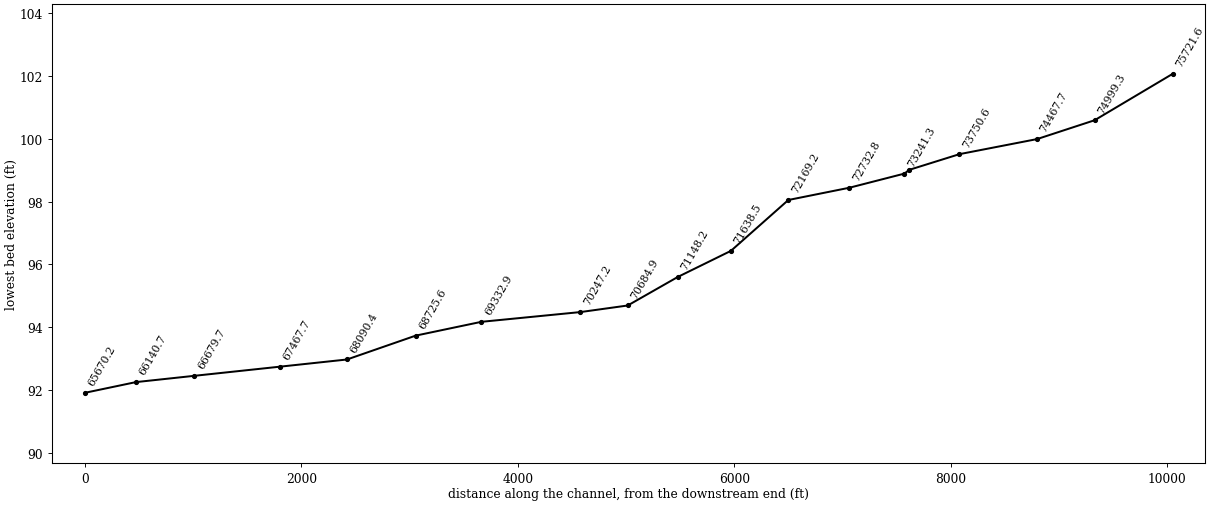
HEC-RAS study Black_Creek_US_FINAL.prj: Black Creek US

--- Black_Creek_US_FINAL.g01 (geometry) --- (continued)

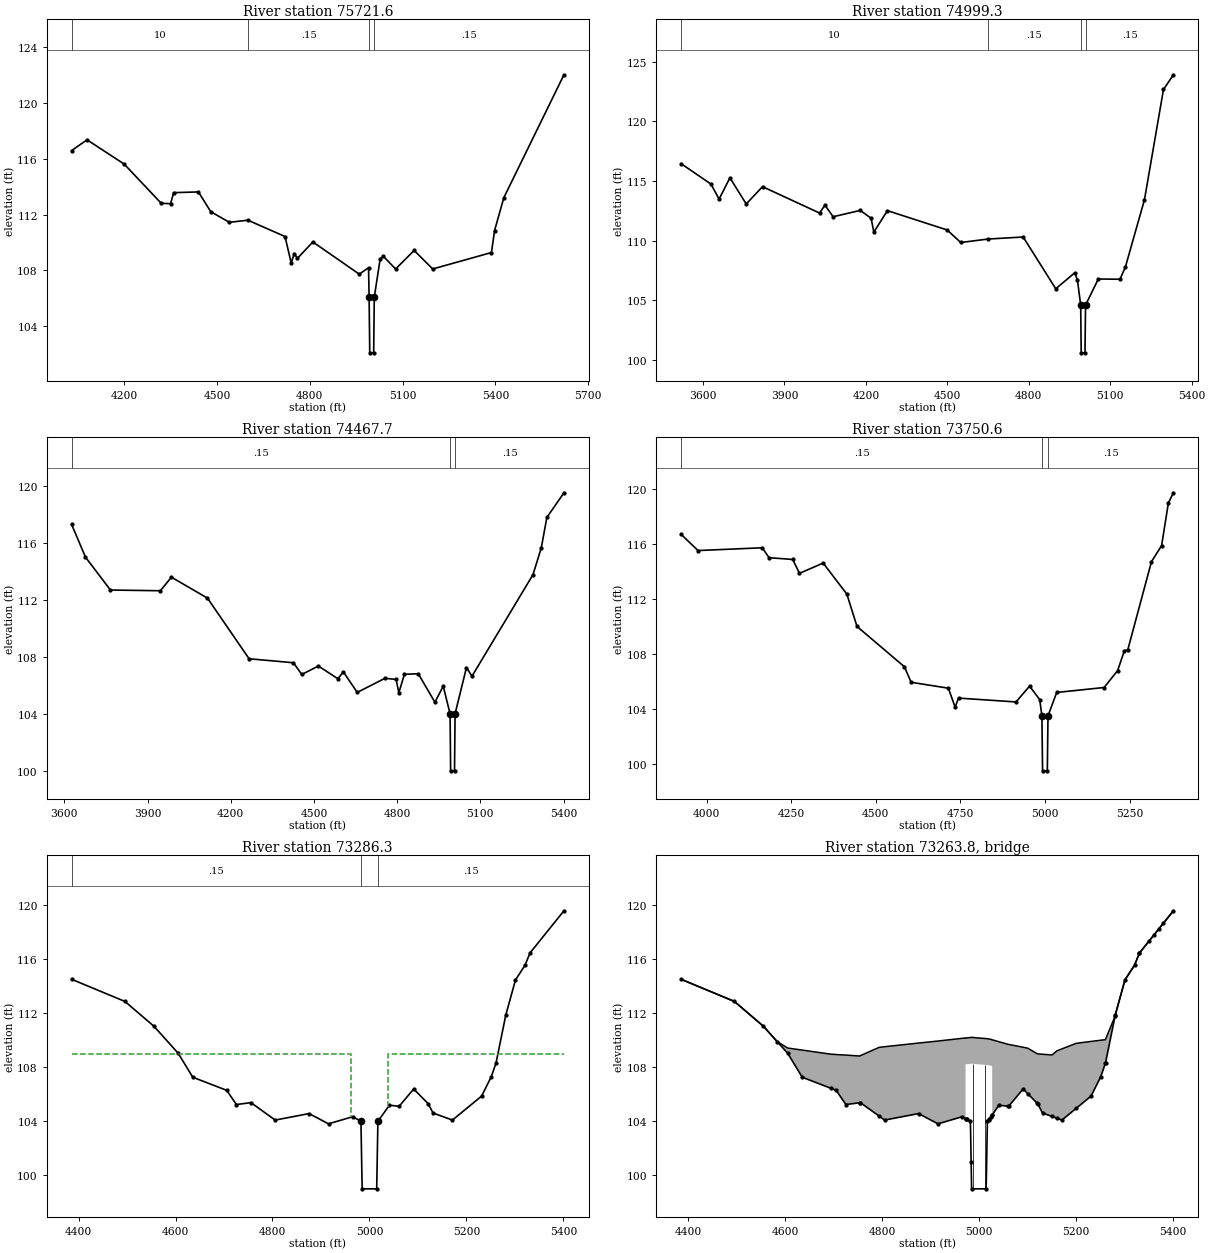
Type RM Length L Ch R = 1 ,75721.6 ,722.3,722.3,722.3
BEGIN DESCRIPTION:
Black Creek US 147.0
END DESCRIPTION:
#Sta/Elev= 30
  4029.8  116.59  4079.8  117.36  4199.8  115.62  4319.8   112.8  4349.8  112.78
  4359.8  113.57  4439.8  113.62  4479.8   112.2  4539.8  111.44  4599.9  111.59
  4719.8  110.42  4739.8  108.52  4749.8   109.2  4759.8  108.85  4809.8  110.03
  4959.8  107.72  4989.8  108.18  4991.7  106.07  4993.7  102.07  5006.4  102.07
  5008.4  106.07  5027.3  108.79  5037.3  109.01  5077.3  108.09  5137.3  109.42
  5197.3  108.09  5387.3  109.27  5397.3  110.85  5427.3  113.21  5621.6  122.03
#Mann= 4 , 1 , 0
  4029.8      10       0  4599.9     .15       0  4991.7    .049       0
  5008.4     .15       0
Bank Sta=4991.7,5008.4
XS Rating Curve= 0 ,0
Exp/Cntr=0.3,0.1

Type RM Length L Ch R = 1 ,74999.3 ,531.6,531.6,531.6
BEGIN DESCRIPTION:
Black Creek US 146.0
END DESCRIPTION:
#Sta/Elev= 30
  3519.2  116.45  3629.2  114.74  3659.2  113.48  3699.2  115.26  3759.2  113.07
  3819.2  114.52  4029.2  112.31  4049.2  112.97  4079.2     112  4179.2  112.53
  4219.2  111.87  4229.2  110.71  4279.2  112.51  4499.2  110.89  4549.2  109.84
  4649.9  110.13  4779.2   110.3  4899.2  105.96  4969.2   107.3  4979.2  106.68
    4991  104.59    4993  100.59  5006.9  100.59  5008.9  104.59    5056  106.78
    5136  106.76    5156  107.81    5226  113.43    5296  122.67  5332.6   123.9
#Mann= 4 , 1 , 0
  3519.2      10       0  4649.9     .15       0    4991    .049       0
  5008.9     .15       0
Bank Sta=4991,5008.9
XS Rating Curve= 0 ,0
Exp/Cntr=0.3,0.1

Type RM Length L Ch R = 1 ,74467.7 ,717.1,717.1,717.1
BEGIN DESCRIPTION:
Black Creek US 145.0
END DESCRIPTION:
#Sta/Elev= 30
  3626.3  117.27  3676.3  114.98  3766.3  112.67  3946.3  112.62  3986.3  113.57
  4116.3   112.1  4266.3  107.85  4426.3  107.57  4456.3  106.75  4516.3  107.34
  4586.3  106.45  4606.3  106.93  4656.3  105.49  4756.3  106.48  4796.3   106.4
  4806.3  105.47  4826.3  106.76  4876.3   106.8  4936.3   104.8  4966.3  105.93
    4991  103.99    4993   99.99    5007   99.99    5009  103.99    5050  107.23
    5070  106.63    5290  113.75    5320  115.64    5340  117.76  5401.6  119.49
#Mann= 3 , 1 , 0
  3626.3     .15       0    4991    .049       0    5009     .15       0
Bank Sta=4991,5009
XS Rating Curve= 0 ,0
Exp/Cntr=0.3,0.1

Type RM Length L Ch R = 1 ,73750.6 ,464.3,464.3,464.3
BEGIN DESCRIPTION:
Black Creek US 144.0
END DESCRIPTION:
#Sta/Elev= 30
  3924.5  116.71  3974.5  115.53  4164.5  115.73  4184.5  115.01  4254.5  114.88
  4274.5  113.87  4344.5  114.62  4414.5  112.36  4444.5  110.01  4584.5  107.08
  4604.5  105.95  4714.5  105.52  4734.5  104.14  4744.5   104.8  4914.5  104.52
  4954.5  105.67  4984.5  104.69    4991  103.51    4993   99.51    5007   99.51
    5009  103.51  5034.8  105.21  5174.8  105.57  5214.8   106.8  5234.8  108.25
  5244.8  108.31  5314.8  114.72  5344.8  115.89  5364.8  118.99  5379.7  119.73
#Mann= 3 , 1 , 0
  3924.5     .15       0    4991    .049       0    5009     .15       0
Bank Sta=4991,5009
XS Rating Curve= 0 ,0
Exp/Cntr=0.5,0.3

Type RM Length L Ch R = 1 ,73286.3 ,45,45,45
BEGIN DESCRIPTION:
Upstream Section of Bridge/Culvert/Weir
END DESCRIPTION:
#Sta/Elev= 30
  4385.6  114.52  4495.6  112.88  4555.6  111.04  4605.6  109.04  4635.6  107.27
  4705.6   106.3  4725.6  105.25  4755.6  105.39  4805.6   104.1  4875.6  104.58
  4915.6  103.82  4965.6  104.35  4982.5  104.01    4985   99.01    5015   99.01
  5017.5  104.01  5041.3   105.2  5061.3  105.12  5091.3   106.4  5121.3  105.31
  5131.3  104.62  5171.3   104.1  5231.3  105.87  5251.3   107.3  5261.3  108.34
  5281.3  111.87  5301.3  114.47  5321.3  115.58  5331.3  116.47  5401.3  119.59
#Mann= 3 , 1 , 0
  4385.6     .15       0  4982.5    .049       0  5017.5     .15       0
#XS Ineff= 2 , 0
       0    4962     109    5038       0     109
Permanent Ineff=
       F       F
Bank Sta=4982.5,5017.5
XS Rating Curve= 0 ,0
Exp/Cntr=0.5,0.3

Type RM Length L Ch R = 3 ,73263.8 ,,,
BEGIN DESCRIPTION:
Huckleberry Rd-TOR
Structure ID: Huckleberry Rd
Approximate Survey Structure
END DESCRIPTION:
Bridge Culvert--1,0,-1,-1, 0
Deck Dist Width WeirC Skew NumUp NumDn MinLoCord MaxHiCord MaxSubmerge Is_Ogee
10,25,2.6,0, 56, 56, , , 0.95, 0, 1,1,,
  4385.6  4495.6  4555.6    4584  4605.6  4635.6    4694  4705.6  4725.6    4754
  4755.6    4794  4805.6  4875.6  4915.6  4965.6 4972.41  4972.5    4975  4982.5
    4984    4985    5015  5017.5  5020.8  5021.3    5025 5027.39  5027.5  5041.3
  5060.8  5061.3  5091.3  5100.8  5120.8  5121.3  5131.3  5150.8  5160.8  5171.3
  5200.8  5231.3  5251.3  5260.8  5261.3  5280.8  5281.3  5301.3  5321.3  5330.8
  5331.3  5350.8  5360.8  5370.8  5380.8  5401.3
  114.51  112.87  111.03  109.89  109.42  109.27  108.97  108.94   108.9  108.83
  108.86  109.47  109.52  109.79  109.94  110.14  110.16  110.17  110.17   110.2
  110.21  110.21  110.12  110.11   110.1  110.09  110.06  110.03  110.03  109.89
  109.69  109.69  109.48  109.41  108.99  108.99  108.96  108.91  109.21  109.36
  109.77  109.91     110  110.04  110.07  111.77  111.86  114.46  115.57  116.42
  116.46  117.33  117.77  118.22  118.67  119.58
  114.51  112.87  111.03  109.89  109.03  107.26  106.45  106.29  105.24  105.37
  105.38  104.39  104.09  104.57  103.81  104.34   104.2  108.22  108.22  108.25
  108.26  108.26  108.17  108.16  108.15  108.14  108.11  108.08  104.47  105.19
  105.11  105.11  106.39  106.04  105.32   105.3  104.61  104.36  104.23  104.09
  104.96  105.86  107.29  108.28  108.33  111.77  111.86  114.46  115.57  116.42
  116.46  117.33  117.77  118.22  118.67  119.58
  4385.6  4495.6  4555.6    4584  4605.6  4635.6    4694  4705.6  4725.6    4754
  4755.6    4794  4805.6  4875.6  4915.6  4965.6 4972.41  4972.5    4975  4982.5
    4984    4985    5015  5017.5  5020.8  5021.3    5025 5027.39  5027.5  5041.3
  5060.8  5061.3  5091.3  5100.8  5120.8  5121.3  5131.3  5150.8  5160.8  5171.3
  5200.8  5231.3  5251.3  5260.8  5261.3  5280.8  5281.3  5301.3  5321.3  5330.8
  5331.3  5350.8  5360.8  5370.8  5380.8  5401.3
  114.46  112.82  110.98  109.85  109.42  109.27  108.97  108.94   108.9  108.83
  108.86  109.47  109.52  109.79  109.94  110.14  110.16  110.17  110.17   110.2
  110.21  110.21  110.12  110.11   110.1  110.09  110.06  110.03  110.03  109.89
  109.69  109.69  109.48  109.41  108.99  108.99  108.96  108.91  109.21  109.36
  109.77  109.91     110  110.04  110.07  111.73  111.82  114.42  115.53  116.38
  116.42  117.29  117.73  118.18  118.63  119.53
  114.41  112.77  110.93  109.79  108.93  107.16  106.35  106.19  105.14  105.27
  105.28  104.29  103.99  104.47  103.71  104.24   104.1  108.12  108.12  108.15
  108.16  108.16  108.07  108.06  108.05  108.04  108.01  107.98  104.37  105.09
  105.01  105.01  106.29  105.94  105.22   105.2  104.51  104.26  104.13  103.99
  104.86  105.76  107.19  108.18  108.23  111.67  111.76  114.36  115.47  116.32
  116.36  117.23  117.67  118.12  118.57  119.48
Pier Skew, UpSta & Num, DnSta & Num=  ,4987.5, 2 ,4987.5, 2 , 0 , 0 , 0 ,,
       1       1
      98  109.25
       1       1
    97.9  109.15
Pier Skew, UpSta & Num, DnSta & Num=  ,5012.5, 2 ,5012.5, 2 , 0 , 0 , 0 ,,
       1       1
      98  109.18
       1       1
    97.9  109.08
Abutment Skew #Up #Dn= , 2 , 2
  4972.3    4975
  108.22  104.15
  4972.3    4975
  108.12  104.05
Abutment Skew #Up #Dn= , 2 , 2
    5025 5027.59
  104.33  108.08
    5025 5027.59
  104.23  107.98
BR Coef= 1 , 1 , 0 ,1.25, 0 ,,,0.8,0,2,0,
WSPro=,,,, 1 ,,,, 0 ,,,, 0 ,,,,-1 ,-1 ,-1 , 0 , 0 , 0 , 0 , 0
BR U #Sta/Elev= 56
  4385.6  114.51  4495.6  112.87  4555.6  111.03    4584  109.89  4605.6  109.03
  4635.6  107.26    4694  106.45  4705.6  106.29  4725.6  105.24    4754  105.37
  4755.6  105.38    4794  104.39  4805.6  104.09  4875.6  104.57  4915.6  103.81
  4965.6  104.34 4972.41   104.2  4972.5   104.2    4975  104.15  4982.5     104
    4984     101    4985      99    5015      99  5017.5     104  5020.8  104.12
  5021.3  104.14    5025  104.33 5027.39  104.46  5027.5  104.47  5041.3  105.19
  5060.8  105.11  5061.3  105.11  5091.3  106.39  5100.8  106.04  5120.8  105.32
  5121.3   105.3  5131.3  104.61  5150.8  104.36  5160.8  104.23  5171.3  104.09
  5200.8  104.96  5231.3  105.86  5251.3  107.29  5260.8  108.28  5261.3  108.33
  5280.8  111.77  5281.3  111.86  5301.3  114.46  5321.3  115.57  5330.8  116.42
  5331.3  116.46  5350.8  117.33  5360.8  117.77  5370.8  118.22  5380.8  118.67
  5401.3  119.58
BR U #Mann= 3
  4385.6     .15  4982.5    .049  5017.5     .15
BR U Banks=4982.5,5017.5
BR D #Sta/Elev= 56
  4385.6  114.41  4495.6  112.77  4555.6  110.93    4584  109.79  4605.6  108.93
  4635.6  107.16    4694  106.35  4705.6  106.19  4725.6  105.14    4754  105.27
  4755.6  105.28    4794  104.29  4805.6  103.99  4875.6  104.47  4915.6  103.71
  4965.6  104.24 4972.41   104.1  4972.5   104.1    4975  104.05  4982.5   103.9
    4984   100.9    4985    98.9    5015    98.9  5017.5   103.9  5020.8  104.02
  5021.3  104.04    5025  104.23 5027.39  104.36  5027.5  104.37  5041.3  105.09
  5060.8  105.01  5061.3  105.01  5091.3  106.29  5100.8  105.94  5120.8  105.22
  5121.3   105.2  5131.3  104.51  5150.8  104.26  5160.8  104.13  5171.3  103.99
  5200.8  104.86  5231.3  105.76  5251.3  107.19  5260.8  108.18  5261.3  108.23
  5280.8  111.67  5281.3  111.76  5301.3  114.36  5321.3  115.47  5330.8  116.32
  5331.3  116.36  5350.8  117.23  5360.8  117.67  5370.8  118.12  5380.8  118.57
  5401.3  119.48
BR D #Mann= 3
  4385.6     .15  4982.5    .049  5017.5     .15
BR D Banks=4982.5,5017.5
BC Design=,, 0 ,, 0 ,,,,,,
BC HTab HWMax=119.59
BC Use User HTab Curves=0
BC User HTab FreeFlow(D)= 0

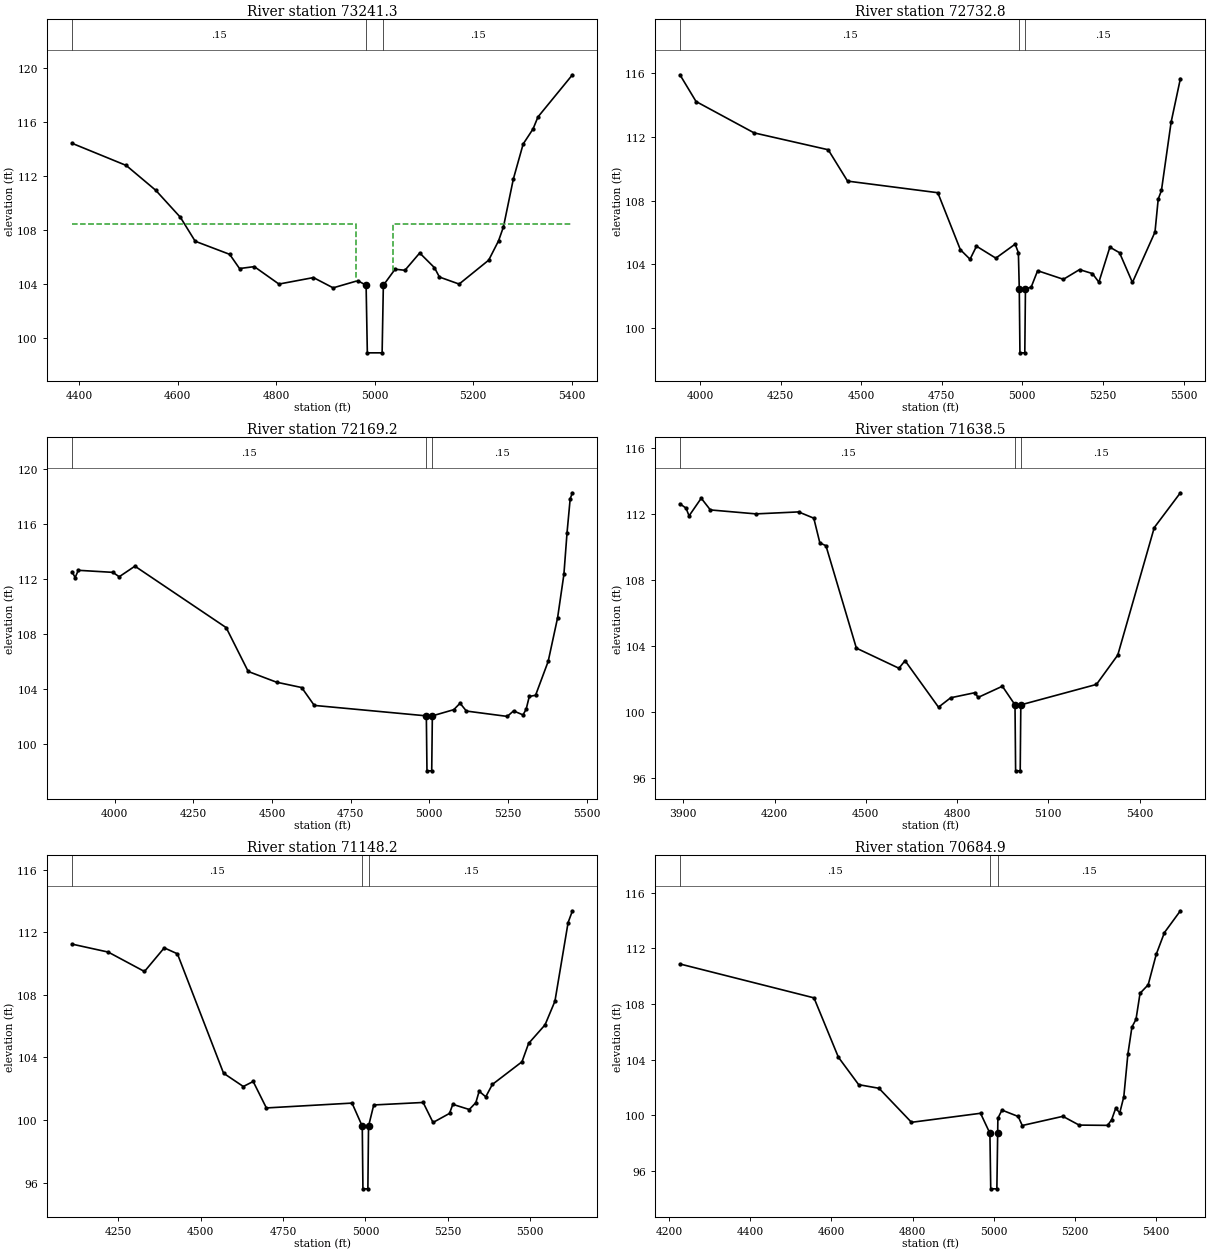
Type RM Length L Ch R = 1 ,73241.3 ,508.5,508.5,508.5
BEGIN DESCRIPTION:
Downstream Section of Bridge/Culvert/Weir
END DESCRIPTION:
#Sta/Elev= 30
  4385.6   114.4  4495.6  112.76  4555.6  110.92  4605.6  108.92  4635.6  107.15
  4705.6  106.18  4725.6  105.13  4755.6  105.27  4805.6  103.98  4875.6  104.46
  4915.6   103.7  4965.6  104.23  4982.5  103.89    4985   98.89    5015   98.89
  5017.5  103.89  5041.3  105.08  5061.3     105  5091.3  106.28  5121.3  105.19
  5131.3   104.5  5171.3  103.98  5231.3  105.75  5251.3  107.18  5261.3  108.22
  5281.3  111.75  5301.3  114.35  5321.3  115.46  5331.3  116.35  5401.3  119.47
#Mann= 3 , 1 , 0
  4385.6     .15       0  4982.5    .049       0  5017.5     .15       0
#XS Ineff= 2 , 0
       0    4962   108.4    5038       0   108.4
Permanent Ineff=
       F       F
Bank Sta=4982.5,5017.5
XS Rating Curve= 0 ,0
Exp/Cntr=0.5,0.3

Type RM Length L Ch R = 1 ,72732.8 ,563.6,563.6,563.6
BEGIN DESCRIPTION:
Black Creek US 69.0
END DESCRIPTION:
#Sta/Elev= 30
  3937.7  115.91  3987.7  114.23  4167.7  112.26  4397.7   111.2  4457.7  109.23
  4737.7   108.5  4807.7  104.92  4837.7  104.32  4857.7  105.14  4917.7  104.39
  4977.7  105.27  4987.7  104.73  4990.5  102.44  4992.5   98.44  5007.6   98.44
  5009.6  102.44  5027.4  102.57  5047.4   103.6  5127.4  103.06  5177.4  103.67
  5217.4  103.42  5237.4  102.88  5271.5  105.08  5301.5  104.73  5341.5  102.86
  5411.5  106.03  5421.5   108.1  5431.5  108.64  5461.5  112.93  5490.3  115.67
#Mann= 3 , 1 , 0
  3937.7     .15       0  4990.5    .049       0  5009.6     .15       0
Bank Sta=4990.5,5009.6
XS Rating Curve= 0 ,0
Exp/Cntr=0.3,0.1

Type RM Length L Ch R = 1 ,72169.2 ,530.7,530.7,530.7
BEGIN DESCRIPTION:
Black Creek US 68.0
END DESCRIPTION:
#Sta/Elev= 30
  3864.3  112.54  3874.3  112.11  3884.3  112.64  3994.3  112.49  4014.3  112.17
  4064.3  112.94  4354.3  108.47  4424.3  105.28  4514.3   104.5  4594.3  104.11
  4634.3  102.81  4990.5  102.05  4992.5   98.05  5007.6   98.05  5009.6  102.05
  5077.7   102.5  5097.7  102.97  5117.7   102.4  5247.7  102.01  5267.7  102.41
  5297.7  102.12  5307.7  102.53  5317.7  103.46  5337.7  103.55  5377.7  106.01
  5407.7  109.19  5427.7  112.34  5437.7  115.38  5447.7  117.85  5454.9  118.28
#Mann= 3 , 1 , 0
  3864.3     .15       0  4990.5    .049       0  5009.6     .15       0
Bank Sta=4990.5,5009.6
XS Rating Curve= 0 ,0
Exp/Cntr=0.3,0.1

Type RM Length L Ch R = 1 ,71638.5 ,490.3,490.3,490.3
BEGIN DESCRIPTION:
Black Creek US 67.0
END DESCRIPTION:
#Sta/Elev= 26
    3889  112.62    3909  112.36    3919  111.89    3959  112.96    3989  112.25
    4139  112.01    4279  112.13    4329  111.75    4349  110.25    4369  110.08
    4469  103.87    4609  102.65    4629  103.11    4739  100.29    4779  100.86
    4859  101.17    4869  100.88    4949  101.56  4990.5  100.43  4992.5   96.43
  5007.6   96.43  5009.6  100.43  5258.3  101.67  5328.3  103.45  5448.3  111.18
  5534.2  113.29
#Mann= 3 , 1 , 0
    3889     .15       0  4990.5    .049       0  5009.6     .15       0
Bank Sta=4990.5,5009.6
XS Rating Curve= 0 ,0
Exp/Cntr=0.3,0.1

Type RM Length L Ch R = 1 ,71148.2 ,463.3,463.3,463.3
BEGIN DESCRIPTION:
Black Creek US 66.0
END DESCRIPTION:
#Sta/Elev= 30
  4109.4  111.24  4219.4  110.73  4329.4  109.49  4389.4     111  4429.4  110.62
  4569.4  102.99  4629.4  102.14  4659.4  102.46  4699.4  100.77  4959.4  101.08
  4990.5    99.6  4992.5    95.6  5007.5    95.6  5009.5    99.6  5025.3  100.96
  5175.3  101.12  5205.3   99.84  5255.3  100.42  5265.3     101  5315.3  100.67
  5335.3  101.11  5345.3  101.84  5365.3  101.48  5385.3  102.27  5475.3  103.72
  5495.3  104.89  5545.3  106.08  5575.3  107.59  5615.3  112.62  5628.5  113.37
#Mann= 3 , 1 , 0
  4109.4     .15       0  4990.5    .049       0  5009.5     .15       0
Bank Sta=4990.5,5009.5
XS Rating Curve= 0 ,0
Exp/Cntr=0.3,0.1

Type RM Length L Ch R = 1 ,70684.9 ,437.7,437.7,437.7
BEGIN DESCRIPTION:
Black Creek US 65.0
END DESCRIPTION:
#Sta/Elev= 30
  4227.3  110.88  4557.3  108.44  4617.3  104.17  4667.3  102.19  4717.3  101.93
  4797.3   99.48  4967.3  100.13  4990.4   98.69  4992.4   94.69  5007.5   94.69
  5009.5   98.69    5010   99.77    5020  100.36    5060    99.9    5070   99.25
    5170   99.91    5210   99.28    5280   99.26    5290   99.66    5300  100.49
    5310  100.16    5320  101.32    5330  104.38    5340  106.34    5350  106.89
    5360  108.77    5380  109.38    5400  111.59    5420  113.14  5459.3  114.71
#Mann= 3 , 1 , 0
  4227.3     .15       0  4990.4    .049       0  5009.5     .15       0
Bank Sta=4990.4,5009.5
XS Rating Curve= 0 ,0
Exp/Cntr=0.3,0.1

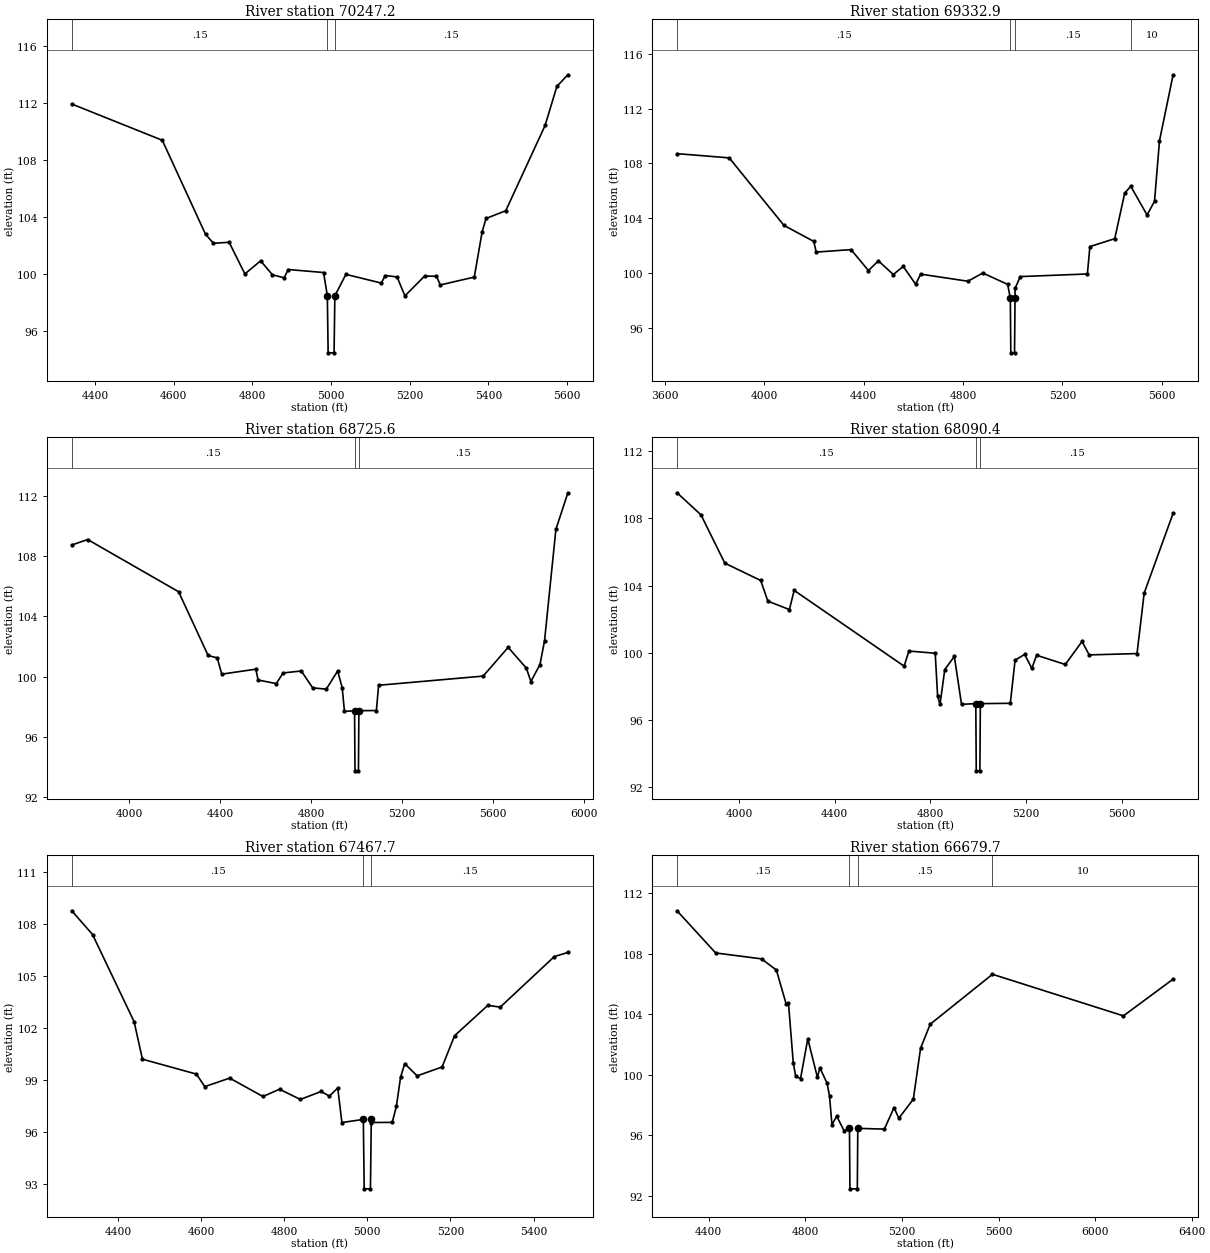
Type RM Length L Ch R = 1 ,70247.2 ,914.3,914.3,914.3
BEGIN DESCRIPTION:
Black Creek US 64.0
END DESCRIPTION:
#Sta/Elev= 30
  4340.8  111.92  4570.8  109.38  4680.8  102.79  4700.8  102.16  4740.8  102.23
  4780.8  100.01  4820.8  100.93  4850.8   99.95  4880.8   99.74  4890.8  100.32
  4980.8  100.11  4990.4   98.48  4992.4   94.48  5007.5   94.48  5009.5   98.48
  5037.6   99.98  5127.6   99.37  5137.6    99.9  5167.6    99.8  5187.6   98.47
  5237.6   99.86  5267.6   99.85  5277.6   99.24  5363.9   99.79  5383.9  102.97
  5393.9   103.9  5443.9  104.44  5543.9  110.42  5573.9  113.16  5601.8  113.97
#Mann= 3 , 1 , 0
  4340.8     .15       0  4990.4    .049       0  5009.5     .15       0
Bank Sta=4990.4,5009.5
XS Rating Curve= 0 ,0
Exp/Cntr=0.3,0.1

Type RM Length L Ch R = 1 ,69332.9 ,607.3,607.3,607.3
BEGIN DESCRIPTION:
Black Creek US 63.5
END DESCRIPTION:
#Sta/Elev= 30
  3649.8  108.72  3859.8  108.41  4079.8  103.48  4199.8  102.31  4209.8  101.53
  4349.8  101.71  4419.8  100.18  4459.8  100.89  4519.8   99.89  4559.8  100.48
  4609.8   99.18  4629.8   99.92  4819.8    99.4  4879.8     100  4979.8   99.17
  4990.5   98.17  4992.5   94.17  5007.5   94.17  5009.5   98.17  5009.8   98.88
  5030.6   99.74  5300.6   99.93  5310.6  101.93  5410.6  102.51  5450.6  105.83
  5474.9  106.34  5540.6  104.24  5570.6  105.24  5590.6  109.66  5645.4  114.48
#Mann= 4 , 1 , 0
  3649.8     .15       0  4990.5    .049       0  5009.5     .15       0
  5474.9      10       0
Bank Sta=4990.5,5009.5
XS Rating Curve= 0 ,0
Exp/Cntr=0.3,0.1

Type RM Length L Ch R = 1 ,68725.6 ,635.2,635.2,635.2
BEGIN DESCRIPTION:
Black Creek US 63.0
END DESCRIPTION:
#Sta/Elev= 30
  3746.1  108.75  3816.1  109.11  4216.1  105.64  4346.1   101.4  4386.1  101.24
  4406.1  100.16  4556.1  100.49  4566.1   99.77  4646.1   99.53  4676.1  100.24
  4756.1  100.37  4806.1   99.25  4866.1   99.16  4916.1  100.37  4936.1   99.26
  4946.1   97.68  4990.5   97.73  4992.5   93.73  5007.6   93.73  5009.6   97.73
  5086.5   97.74  5096.5   99.42  5556.5  100.03  5666.5  101.94  5746.5  100.56
  5766.5   99.67  5806.5   100.8  5826.5  102.37  5876.5  109.78  5929.3  112.22
#Mann= 3 , 1 , 0
  3746.1     .15       0  4990.5    .049       0  5009.6     .15       0
Bank Sta=4990.5,5009.6
XS Rating Curve= 0 ,0
Exp/Cntr=0.3,0.1

Type RM Length L Ch R = 1 ,68090.4 ,622.7,622.7,622.7
BEGIN DESCRIPTION:
Black Creek US 62.0
END DESCRIPTION:
#Sta/Elev= 30
  3740.7  109.52  3840.7  108.21  3940.7  105.33  4090.7   104.3  4120.7  103.07
  4210.7  102.57  4230.7  103.71  4690.7    99.2  4710.7   100.1  4820.7   99.97
  4830.7   97.43  4840.7   96.92  4860.7      99  4900.7   99.78  4930.7   96.93
  4990.4   96.97  4992.4   92.97  5007.5   92.97  5009.5   96.97  5134.8   96.99
  5154.8   99.56  5194.8    99.9  5224.8   99.07  5244.8   99.85  5364.8    99.3
  5434.8  100.67  5464.8   99.87  5664.8   99.95  5694.8  103.55  5815.8   108.3
#Mann= 3 , 1 , 0
  3740.7     .15       0  4990.4    .049       0  5009.5     .15       0
Bank Sta=4990.4,5009.5
XS Rating Curve= 0 ,0
Exp/Cntr=0.3,0.1

Type RM Length L Ch R = 1 ,67467.7 ,788,788,788
BEGIN DESCRIPTION:
Black Creek US 61.0
END DESCRIPTION:
#Sta/Elev= 30
  4288.9  108.76  4338.9  107.39  4438.9  102.37  4458.9  100.21  4588.9   99.35
  4608.9   98.63  4668.9   99.12  4748.9   98.06  4788.9   98.48  4838.9   97.89
  4888.9   98.35  4908.9   98.08  4928.9   98.55  4938.9   96.56  4990.5   96.74
  4992.5   92.74  5007.6   92.74  5009.6   96.74    5010   96.56    5060   96.57
    5070   97.49    5080   99.16    5090   99.95    5120   99.25    5180   99.76
    5210  101.56    5290  103.31    5320  103.21    5450  106.12  5482.7  106.36
#Mann= 3 , 1 , 0
  4288.9     .15       0  4990.5    .049       0  5009.6     .15       0
Bank Sta=4990.5,5009.6
XS Rating Curve= 0 ,0
Exp/Cntr=0.3,0.1

Type RM Length L Ch R = 1 ,66679.7 ,539,539,539
BEGIN DESCRIPTION:
Black Creek US 60.0
END DESCRIPTION:
#Sta/Elev= 30
  4268.6  110.84  4428.6  108.05  4618.6  107.66  4680.1  106.92  4720.1   104.7
  4730.1  104.74  4750.1  100.77  4760.1    99.9  4780.1   99.74  4810.1  102.37
  4850.1   99.82  4860.1  100.46  4890.1   99.43  4900.1   98.59  4910.1    96.7
  4930.1   97.25  4960.1    96.3  4982.7   96.45  4984.7   92.45  5015.2   92.45
  5017.2   96.45  5127.2    96.4  5167.2   97.82  5187.2   97.12  5247.2   98.38
  5277.2  101.75  5317.2  103.34  5574.9  106.64  6117.2  103.89    6323  106.32
#Mann= 4 , 1 , 0
  4268.6     .15       0  4982.7    .049       0  5017.2     .15       0
  5574.9      10       0
Bank Sta=4982.7,5017.2
XS Rating Curve= 0 ,0
Exp/Cntr=0.3,0.1

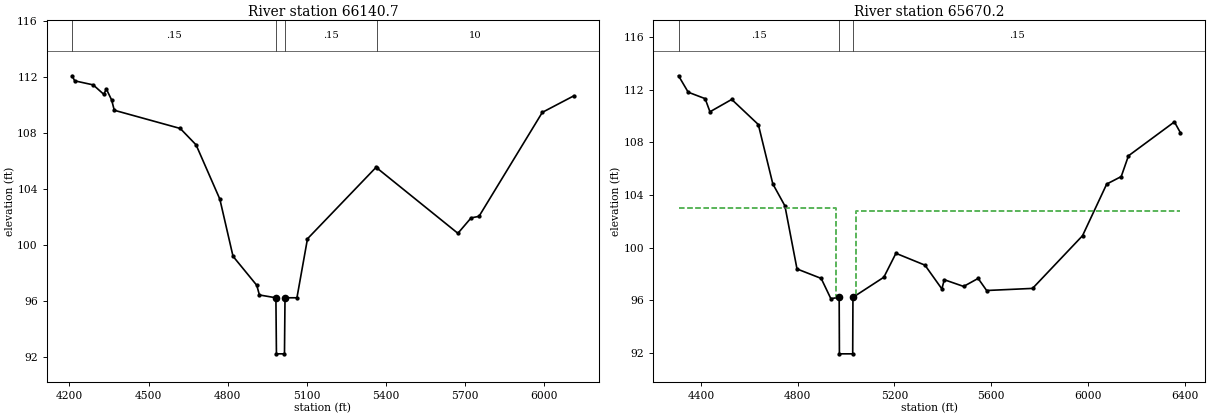
Type RM Length L Ch R = 1 ,66140.7 ,470.5,470.5,470.5
BEGIN DESCRIPTION:
Black Creek US 59.0
END DESCRIPTION:
#Sta/Elev= 26
  4210.2  112.09  4220.2  111.73  4290.2  111.44  4330.2  110.77  4340.2  111.14
  4360.2  110.36  4370.2  109.63  4620.2  108.33  4680.2  107.16  4770.2  103.29
  4820.2   99.21  4910.2   97.14  4920.2   96.45  4982.7   96.25  4984.7   92.25
  5015.2   92.25  5017.2   96.25  5062.4   96.25  5102.4  100.46  5362.4  105.56
  5364.9  105.52  5672.4  100.85  5722.4  101.95  5752.4  102.06  5992.4  109.48
  6111.9  110.66
#Mann= 4 , 1 , 0
  4210.2     .15       0  4982.7    .049       0  5017.2     .15       0
  5364.9      10       0
Bank Sta=4982.7,5017.2
XS Rating Curve= 0 ,0
Exp/Cntr=0.5,0.3

Type RM Length L Ch R = 1 ,65670.2 ,44,44,44
BEGIN DESCRIPTION:
Upstream Section of Bridge/Culvert/Weir
END DESCRIPTION:
#Sta/Elev= 30
  4307.1  113.07  4347.1  111.82  4417.1  111.33  4437.1  110.33  4527.1  111.27
  4637.1  109.36  4697.1  104.84  4747.1  103.17  4797.1   98.37  4897.1   97.65
  4937.1   96.11  4971.5   96.21  4972.5   91.91  5027.5   91.91  5028.5   96.21
  5156.3   97.74  5206.3   99.56  5326.3   98.66  5396.3   96.85  5406.3   97.55
  5486.3   97.04  5546.3   97.65  5581.4   96.73  5771.4   96.89  5978.1   100.9
  6078.1  104.83  6138.1   105.4  6168.1  106.98  6358.1  109.56  6382.6  108.75
#Mann= 3 , 1 , 0
  4307.1     .15       0  4971.5    .049       0  5028.5     .15       0
#XS Ineff= 2 , 0
       0    4959     103    5041       0   102.8
Permanent Ineff=
       F       F
Bank Sta=4971.5,5028.5
XS Rating Curve= 0 ,0
Exp/Cntr=0.5,0.3