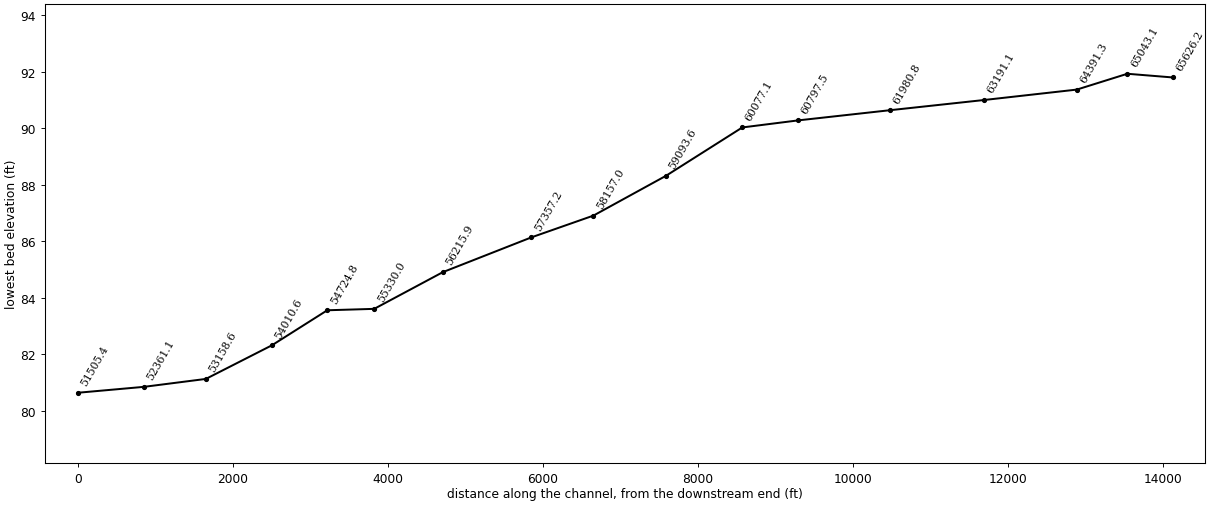
HEC-RAS study Black_Creek_US_FINAL.prj: Black Creek US

--- Black_Creek_US_FINAL.g01 (geometry) --- (continued)

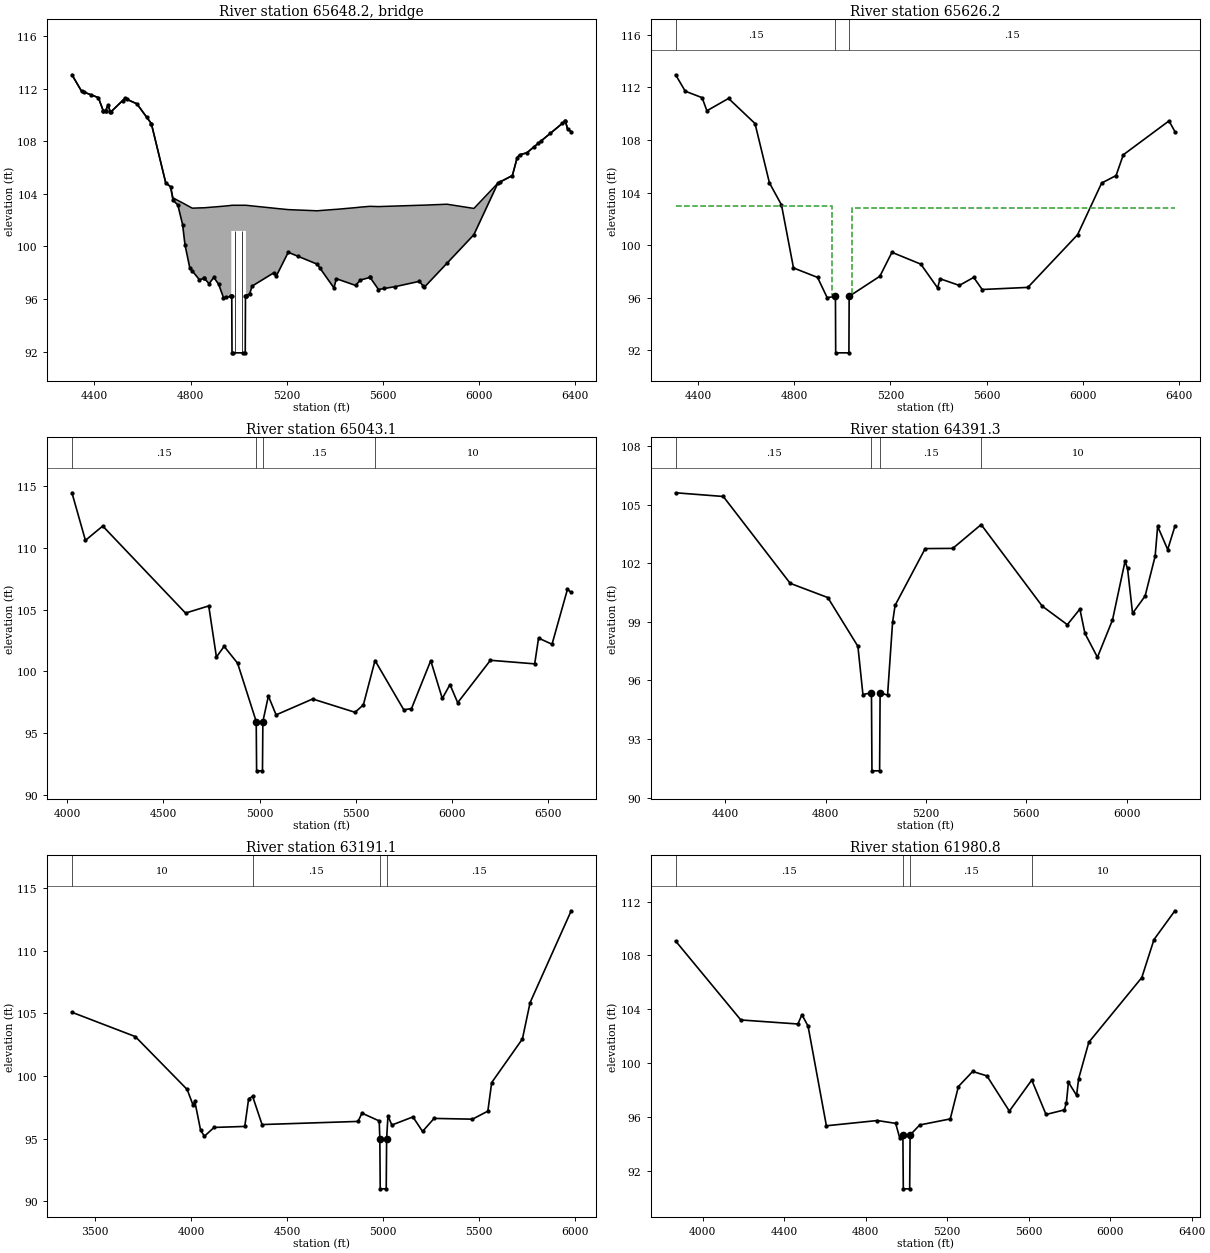
Type RM Length L Ch R = 3 ,65648.2 ,,,
BEGIN DESCRIPTION:
Little Rock Church Rd-TOR
Structure ID: Little Rock Church Rd
Approximate Survey Structure
END DESCRIPTION:
Bridge Culvert--1,0,-1,-1, 0
Deck Dist Width WeirC Skew NumUp NumDn MinLoCord MaxHiCord MaxSubmerge Is_Ogee
10,24,2.6,0, 53, 53, , , 0.95, 0, 1,1,,
  4307.1  4347.1  4417.1  4437.1  4447.1  4457.1  4467.1  4527.1  4577.1  4637.1
  4697.1  4717.1  4727.1  4747.1  4767.1  4777.1  4797.1  4807.4  4837.1  4857.1
  4877.1  4897.1  4917.1  4937.1 4969.41  4969.5  4971.5 5030.39  5030.5  5046.3
  5056.3  5146.3  5156.3  5206.3  5326.3  5396.3  5406.3  5486.3  5506.3  5546.3
  5581.4  5751.4  5771.4  5866.4  5978.1  6078.1  6138.1  6158.1  6168.1  6198.1
  6358.1  6368.1  6382.6
  113.06  111.81  111.32  110.32  110.32  110.76   110.2  111.26  110.85  109.35
  104.83  104.54   103.7   103.5  103.31  103.21  103.01  102.91  102.93  102.94
  102.97     103  103.03  103.06  103.12  103.12  103.13  103.13  103.13   103.1
  103.08  102.91  102.89   102.8  102.71  102.81  102.82  102.95  102.99  103.05
  103.03  103.13  103.14  103.21  102.89  104.82  105.39  106.76  106.97  107.12
  109.55   108.9  108.74
  113.06  111.81  111.32  110.32  110.32  110.76   110.2  111.26  110.85  109.35
  104.83  104.54  103.51  103.16  101.66  100.11   98.36   98.13   97.46   97.58
   97.16   97.64   97.11    96.1   96.19  101.17  101.18  101.18   96.22   96.41
   96.98   97.99   97.73   99.55   98.65   96.84   97.54   97.03   97.44   97.64
   96.72   97.34   96.88   98.72  100.89  104.82  105.39  106.76  106.97  107.12
  109.55   108.9  108.74
  4307.1  4347.1  4417.1  4437.1  4447.1  4457.1  4467.1  4527.1  4577.1  4637.1
  4697.1  4717.1  4727.1  4747.1  4767.1  4777.1  4797.1  4807.4  4837.1  4857.1
  4877.1  4897.1  4917.1  4937.1 4969.41  4969.5  4971.5 5030.39  5030.5  5046.3
  5056.3  5146.3  5156.3  5206.3  5326.3  5396.3  5406.3  5486.3  5506.3  5546.3
  5581.4  5751.4  5771.4  5866.4  5978.1  6078.1  6138.1  6158.1  6168.1  6198.1
  6358.1  6368.1  6382.6
  113.01  111.76  111.28  110.28  110.28  110.72  110.16  111.22  110.81  109.31
  104.79   104.5   103.7   103.5  103.31  103.21  103.01  102.91  102.93  102.94
  102.97     103  103.03  103.06  103.12  103.12  103.13  103.13  103.13   103.1
  103.08  102.91  102.89   102.8  102.71  102.81  102.82  102.95  102.99  103.05
  103.03  103.13  103.14  103.21  102.89  104.78  105.35  106.72  106.93  107.08
   109.5  108.85  108.69
  112.96  111.71  111.22  110.22  110.22  110.66   110.1  111.16  110.75  109.25
  104.73  104.44  103.41  103.06  101.56  100.01   98.26   98.03   97.36   97.48
   97.06   97.54   97.01      96   96.09  101.07  101.08  101.08   96.12   96.31
   96.88   97.89   97.63   99.45   98.55   96.74   97.44   96.93   97.34   97.54
   96.62   97.24   96.78   98.62  100.79  104.72  105.29  106.66  106.87  107.02
  109.45   108.8  108.64
Pier Skew, UpSta & Num, DnSta & Num=  ,4984.8, 2 ,4984.8, 2 , 0 , 0 , 0 ,,
       1       1
    90.9  102.19
       1       1
    90.8  102.09
Pier Skew, UpSta & Num, DnSta & Num=  ,5015.3, 2 ,5015.3, 2 , 0 , 0 , 0 ,,
       1       1
    90.9  102.21
       1       1
    90.8  102.11
BR Coef= 1 , 1 , 0 ,1.25, 0 ,,,0.8,0,2,0,
WSPro=,,,, 1 ,,,, 0 ,,,, 0 ,,,,-1 ,-1 ,-1 , 0 , 0 , 0 , 0 , 0
BR U #Sta/Elev= 84
  4307.1  113.06  4347.1  111.81  4357.4  111.74  4387.4  111.53  4417.1  111.32
  4437.1  110.32  4437.4  110.32  4447.1  110.32  4447.4  110.33  4457.1  110.76
  4467.1   110.2  4467.4  110.21  4517.4  111.09  4527.1  111.26  4537.4  111.18
  4577.1  110.85  4617.4  109.84  4637.1  109.35  4637.4  109.33  4697.1  104.83
  4717.1  104.54  4727.1  103.51  4747.1  103.16  4767.1  101.66  4777.1  100.11
  4797.1   98.36  4807.4   98.13  4837.1   97.46  4857.1   97.58  4857.4   97.57
  4877.1   97.16  4897.1   97.64  4917.1   97.11  4937.1    96.1  4947.4   96.13
 4969.41   96.19  4969.5   96.19  4969.6   96.19  4971.5    96.2  4972.5    91.9
  4977.4    91.9  5016.4    91.9  5027.5    91.9  5028.5    96.2  5030.3   96.22
 5030.39   96.22  5030.5   96.22  5046.3   96.41  5056.3   96.98  5146.3   97.99
  5156.3   97.73  5206.3   99.55  5246.4   99.25  5326.3   98.65  5336.4   98.39
  5396.3   96.84  5406.3   97.54  5486.3   97.03  5506.3   97.44  5546.3   97.64
  5546.4   97.64  5581.4   96.72  5606.4    96.8  5651.4   96.94  5751.4   97.34
  5766.4      97  5771.4   96.88  5866.4   98.72  5978.1  100.89  6078.1  104.82
  6086.4   104.9  6138.1  105.39  6158.1  106.76  6168.1  106.97  6198.1  107.12
  6226.4  107.55  6246.4  107.85  6256.4  108.01  6296.4  108.61  6346.4  109.37
  6356.4  109.52  6358.1  109.55  6368.1   108.9  6382.6  108.74
BR U #Mann= 3
  4307.1     .15  4971.5    .049  5028.5     .15
BR U Banks=4971.5,5028.5
BR D #Sta/Elev= 84
  4307.1  112.96  4347.1  111.71  4357.4  111.64  4387.4  111.43  4417.1  111.22
  4437.1  110.22  4437.4  110.22  4447.1  110.22  4447.4  110.23  4457.1  110.66
  4467.1   110.1  4467.4  110.11  4517.4  110.99  4527.1  111.16  4537.4  111.08
  4577.1  110.75  4617.4  109.74  4637.1  109.25  4637.4  109.23  4697.1  104.73
  4717.1  104.44  4727.1  103.41  4747.1  103.06  4767.1  101.56  4777.1  100.01
  4797.1   98.26  4807.4   98.03  4837.1   97.36  4857.1   97.48  4857.4   97.47
  4877.1   97.06  4897.1   97.54  4917.1   97.01  4937.1      96  4947.4   96.03
 4969.41   96.09  4969.5   96.09  4969.6   96.09  4971.5    96.1  4972.5    91.8
  4977.4    91.8  5016.4    91.8  5027.5    91.8  5028.5    96.1  5030.3   96.12
 5030.39   96.12  5030.5   96.12  5046.3   96.31  5056.3   96.88  5146.3   97.89
  5156.3   97.63  5206.3   99.45  5246.4   99.15  5326.3   98.55  5336.4   98.29
  5396.3   96.74  5406.3   97.44  5486.3   96.93  5506.3   97.34  5546.3   97.54
  5546.4   97.54  5581.4   96.62  5606.4    96.7  5651.4   96.84  5751.4   97.24
  5766.4    96.9  5771.4   96.78  5866.4   98.62  5978.1  100.79  6078.1  104.72
  6086.4   104.8  6138.1  105.29  6158.1  106.66  6168.1  106.87  6198.1  107.02
  6226.4  107.45  6246.4  107.75  6256.4  107.91  6296.4  108.51  6346.4  109.27
  6356.4  109.42  6358.1  109.45  6368.1   108.8  6382.6  108.64
BR D #Mann= 3
  4307.1     .15  4971.5    .049  5028.5     .15
BR D Banks=4971.5,5028.5
BC Design=,, 0 ,, 0 ,,,,,,
BC HTab HWMax=113.07
BC Use User HTab Curves=0
BC User HTab FreeFlow(D)= 0

Type RM Length L Ch R = 1 ,65626.2 ,583.1,583.1,583.1
BEGIN DESCRIPTION:
Downstream Section of Bridge/Culvert/Weir
END DESCRIPTION:
#Sta/Elev= 30
  4307.1  112.96  4347.1  111.71  4417.1  111.22  4437.1  110.22  4527.1  111.16
  4637.1  109.25  4697.1  104.73  4747.1  103.06  4797.1   98.26  4897.1   97.54
  4937.1      96  4971.5    96.1  4972.5    91.8  5027.5    91.8  5028.5    96.1
  5156.3   97.63  5206.3   99.45  5326.3   98.55  5396.3   96.74  5406.3   97.44
  5486.3   96.93  5546.3   97.54  5581.4   96.62  5771.4   96.78  5978.1  100.79
  6078.1  104.72  6138.1  105.29  6168.1  106.87  6358.1  109.45  6382.6  108.64
#Mann= 3 , 1 , 0
  4307.1     .15       0  4971.5    .049       0  5028.5     .15       0
#XS Ineff= 2 , 0
       0    4959     103    5041       0   102.8
Permanent Ineff=
       F       F
Bank Sta=4971.5,5028.5
XS Rating Curve= 0 ,0
Exp/Cntr=0.5,0.3

Type RM Length L Ch R = 1 ,65043.1 ,651.8,651.8,651.8
BEGIN DESCRIPTION:
Black Creek US 58.0
END DESCRIPTION:
#Sta/Elev= 30
  4025.6  114.49  4095.6  110.63  4185.6  111.79  4615.6  104.73  4736.1  105.31
  4776.1  101.16  4816.1  102.03  4886.1  100.66  4982.8   95.93  4984.8   91.93
  5015.3   91.93  5017.3   95.93    5046      98    5086   96.47    5276   97.76
    5496   96.68  5539.3   97.28  5599.9  100.88  5749.3   96.88  5789.3   96.98
  5889.3  100.87  5949.3    97.8  5989.3   98.93  6029.3   97.46  6199.3   100.9
  6429.3  100.61  6449.3   102.7  6519.3   102.2  6599.3  106.65  6618.9  106.41
#Mann= 4 , 1 , 0
  4025.6     .15       0  4982.8    .049       0  5017.3     .15       0
  5599.9      10       0
Bank Sta=4982.8,5017.3
XS Rating Curve= 0 ,0
Exp/Cntr=0.3,0.1

Type RM Length L Ch R = 1 ,64391.3 ,1200.2,1200.2,1200.2
BEGIN DESCRIPTION:
Black Creek US 57.0
END DESCRIPTION:
#Sta/Elev= 30
  4202.1  105.62  4392.1  105.43  4658.7  100.98  4808.7  100.25  4928.7   97.75
  4948.7   95.28  4982.7   95.37  4984.7   91.37  5015.2   91.37  5017.2   95.37
  5046.9   95.25  5066.9   98.98  5076.9   99.85  5196.9  102.76  5306.9  102.77
  5419.9  103.99  5663.5   99.81  5763.5   98.86  5813.5   99.66  5833.5   98.42
  5883.5   97.19  5943.5    99.1  5993.5  102.11  6003.5  101.74  6023.5   99.44
  6073.5  100.33  6113.5  102.37  6123.5   103.9  6163.5  102.71  6192.2   103.9
#Mann= 4 , 1 , 0
  4202.1     .15       0  4982.7    .049       0  5017.2     .15       0
  5419.9      10       0
Bank Sta=4982.7,5017.2
XS Rating Curve= 0 ,0
Exp/Cntr=0.3,0.1

Type RM Length L Ch R = 1 ,63191.1 ,1210.3,1210.3,1210.3
BEGIN DESCRIPTION:
Black Creek US 55.0
END DESCRIPTION:
#Sta/Elev= 30
    3379  105.09    3709  103.15    3979   98.93    4009   97.71    4019   97.97
    4049   95.67    4069    95.2    4119    95.9    4279   95.98    4299   98.18
  4319.9   98.38    4369   96.13    4869   96.38    4889   97.04    4979   96.42
  4982.3      95  4984.3      91  5015.6      91  5017.6      95  5024.7   96.83
  5044.7   96.09  5154.7   96.74  5204.7   95.58  5264.7   96.62  5464.7   96.56
  5544.7    97.2  5564.7   99.48  5724.7  102.96  5764.7  105.86  5978.8  113.19
#Mann= 4 , 1 , 0
    3379      10       0  4319.9     .15       0  4982.3    .049       0
  5017.6     .15       0
Bank Sta=4982.3,5017.6
XS Rating Curve= 0 ,0
Exp/Cntr=0.3,0.1

Type RM Length L Ch R = 1 ,61980.8 ,1183.3,1183.3,1183.3
BEGIN DESCRIPTION:
Black Creek US 54.0
END DESCRIPTION:
#Sta/Elev= 30
  3866.9  109.07  4186.9   103.2  4466.9   102.9  4486.9  103.59  4516.9  102.74
  4606.9   95.33  4856.9   95.72  4946.9   95.51  4966.9   94.42  4982.4   94.64
  4984.4   90.64  5015.7   90.64  5017.7   94.64  5064.9   95.39  5214.9   95.84
  5254.9   98.25  5324.9   99.37  5394.9   99.04  5504.9   96.42  5614.9   98.73
  5684.9   96.17  5774.9   96.51  5784.9   97.04  5794.9   98.57  5834.9   97.59
  5844.9   98.83  5894.9  101.54  6154.9  106.35  6214.9  109.18  6317.4  111.32
#Mann= 4 , 1 , 0
  3866.9     .15       0  4982.4    .049       0  5017.7     .15       0
  5614.9      10       0
Bank Sta=4982.4,5017.7
XS Rating Curve= 0 ,0
Exp/Cntr=0.3,0.1

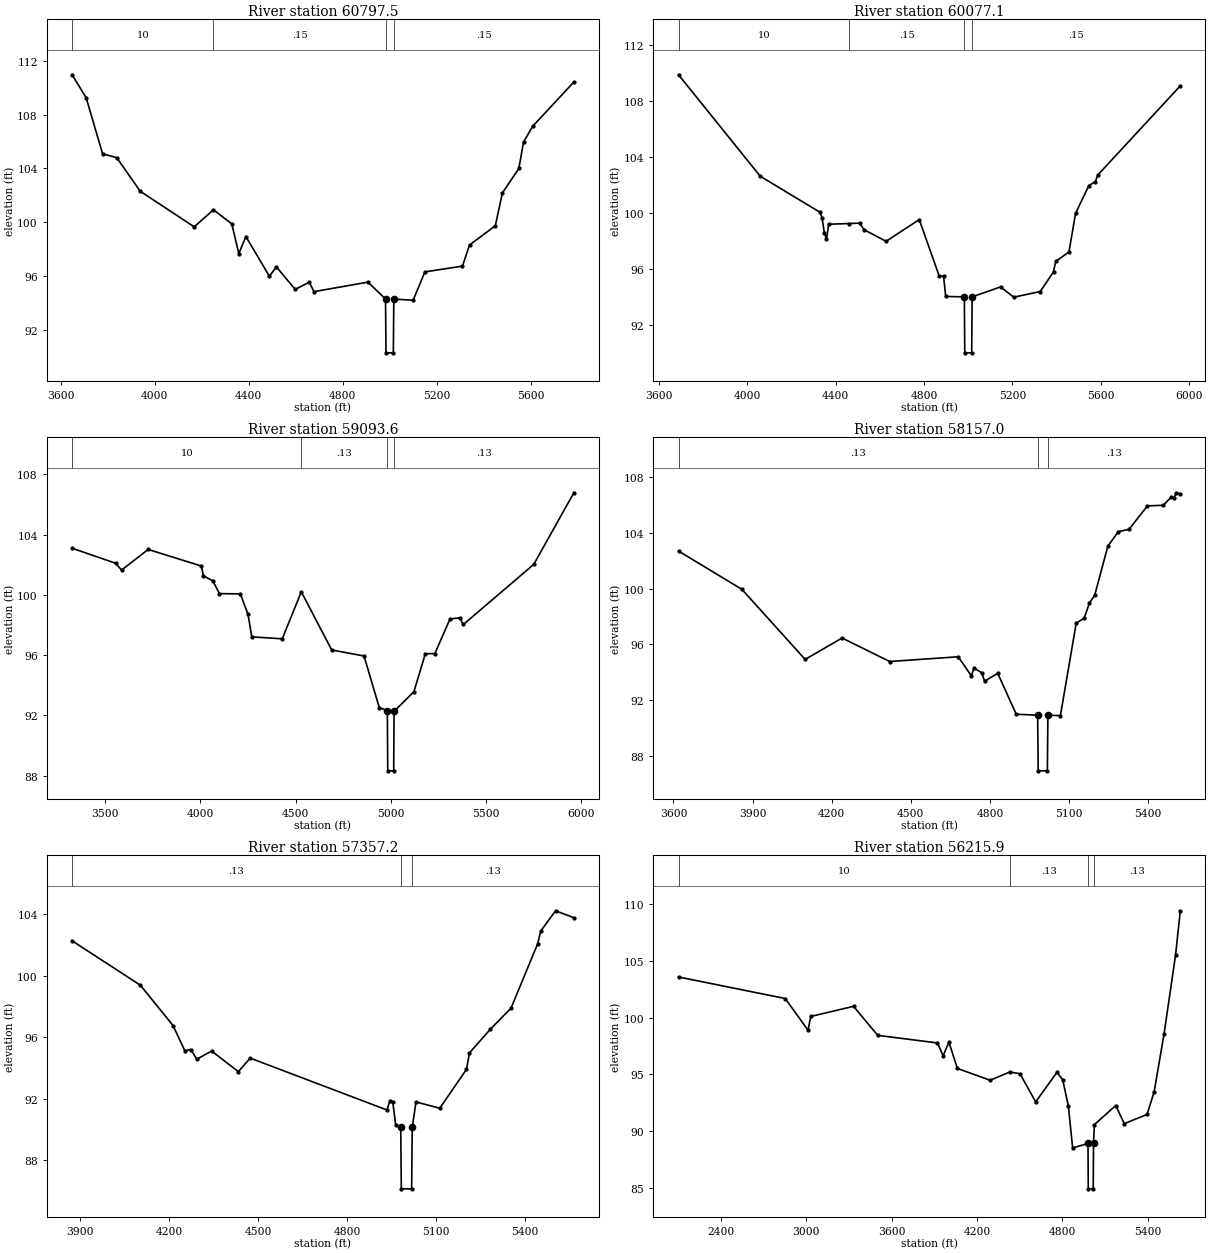
Type RM Length L Ch R = 1 ,60797.5 ,720.4,720.4,720.4
BEGIN DESCRIPTION:
Black Creek US 52.0
END DESCRIPTION:
#Sta/Elev= 30
  3647.8  110.96  3707.8  109.25  3777.8  105.08  3837.8   104.8  3937.8   102.3
  4167.8   99.65  4249.9  100.92  4327.8   99.87  4357.8   97.66  4387.8   98.93
  4487.8   95.98  4517.8   96.67  4597.8      95  4657.8   95.53  4677.8   94.83
  4907.8   95.54  4982.4   94.28  4984.4   90.28  5015.7   90.28  5017.7   94.28
    5100   94.19    5150    96.3    5310   96.73    5340    98.3    5450   99.73
    5480  102.17    5550  103.99    5570  105.96    5610  107.15  5784.3  110.42
#Mann= 4 , 1 , 0
  3647.8      10       0  4249.9     .15       0  4982.4    .049       0
  5017.7     .15       0
Bank Sta=4982.4,5017.7
XS Rating Curve= 0 ,0
Exp/Cntr=0.3,0.1

Type RM Length L Ch R = 1 ,60077.1 ,983.5,983.5,983.5
BEGIN DESCRIPTION:
Black Creek US 51.0
END DESCRIPTION:
#Sta/Elev= 30
  3688.2   109.9  4058.2  102.65  4328.2  100.08  4338.2   99.68  4348.2   98.62
  4358.2   98.16  4368.2   99.22  4459.9   99.27  4508.2    99.3  4528.2   98.83
  4628.2      98  4778.2   99.55  4868.2   95.54  4888.2    95.5  4898.2   94.06
  4982.4   94.03  4984.4   90.03  5015.7   90.03  5017.7   94.03  5146.2   94.74
  5206.2   94.01  5326.2   94.41  5386.2   95.82  5396.2   96.56  5456.2   97.24
  5486.2     100  5546.2  101.98  5576.2  102.27  5586.2  102.73  5960.5  109.11
#Mann= 4 , 1 , 0
  3688.2      10       0  4459.9     .15       0  4982.4    .049       0
  5017.7     .15       0
Bank Sta=4982.4,5017.7
XS Rating Curve= 0 ,0
Exp/Cntr=0.3,0.1

Type RM Length L Ch R = 1 ,59093.6 ,936.6,936.6,936.6
BEGIN DESCRIPTION:
Black Creek US 50.0
END DESCRIPTION:
#Sta/Elev= 29
    3325  103.09    3555  102.09    3585  101.64    3725  103.01    4005  101.91
    4015  101.27    4065  100.92  4099.8  100.08  4209.8  100.06  4249.8    98.7
  4269.8   97.21  4429.8   97.08  4529.9   100.2  4689.8   96.34  4859.8   95.94
  4939.8   92.52  4982.3   92.32  4984.3   88.32  5015.6   88.32  5017.6   92.32
  5021.9   92.32  5121.9   93.57  5181.9   96.09  5231.9    96.1  5311.9    98.4
  5361.9   98.47  5381.9   98.03  5751.9  102.02  5962.7  106.77
#Mann= 4 , 1 , 0
    3325      10       0  4529.9     .13       0  4982.3    .047       0
  5017.6     .13       0
Bank Sta=4982.3,5017.6
XS Rating Curve= 0 ,0
Exp/Cntr=0.3,0.1

Type RM Length L Ch R = 1 ,58157.0 ,799.8,799.8,799.8
BEGIN DESCRIPTION:
Black Creek US 49.0
END DESCRIPTION:
#Sta/Elev= 30
  3619.3  102.71  3859.3   99.96  4099.3   94.92  4239.3   96.46  4419.3   94.77
  4679.3   95.11  4729.3   93.74  4739.3    94.3  4769.3   93.95  4779.3   93.35
  4829.3   93.92  4899.3   90.98  4980.6   90.91  4982.6   86.91  5017.4   86.91
  5019.4   90.91  5066.8   90.88  5126.8   97.53  5156.8   97.88  5176.8   98.97
  5196.8   99.53  5246.8  103.07  5286.8  104.11  5326.8  104.27  5396.8  105.96
  5456.8     106  5486.8  106.59  5496.8  106.52  5506.8   106.9  5521.4  106.81
#Mann= 3 , 1 , 0
  3619.3     .13       0  4980.6    .047       0  5019.4     .13       0
Bank Sta=4980.6,5019.4
XS Rating Curve= 0 ,0
Exp/Cntr=0.3,0.1

Type RM Length L Ch R = 1 ,57357.2 ,1141.3,1141.3,1141.3
BEGIN DESCRIPTION:
Black Creek US 47.0
END DESCRIPTION:
#Sta/Elev= 27
  3873.8  102.27  4103.8   99.38  4213.8   96.76  4253.8   95.11  4273.8    95.2
  4293.8   94.57  4343.8    95.1  4433.8   93.76  4473.8   94.64  4933.8   91.27
  4943.8   91.82  4953.8    91.8  4963.8   90.27  4980.6   90.14  4982.6   86.14
  5017.4   86.14  5019.4   90.14  5032.1   91.79  5112.1   91.38  5202.1   93.91
  5212.1   94.98  5282.1   96.51  5352.1   97.89  5442.1  102.09  5452.1   102.9
  5502.1  104.22  5563.7  103.77
#Mann= 3 , 1 , 0
  3873.8     .13       0  4980.6    .047       0  5019.4     .13       0
Bank Sta=4980.6,5019.4
XS Rating Curve= 0 ,0
Exp/Cntr=0.3,0.1

Type RM Length L Ch R = 1 ,56215.9 ,885.9,885.9,885.9
BEGIN DESCRIPTION:
Black Creek US 46.0
END DESCRIPTION:
#Sta/Elev= 30
  2102.7   103.6  2852.7   101.7  3012.7   98.91  3032.7  100.12  3332.7  101.01
  3502.7   98.45  3922.7   97.78  3962.7   96.64  4002.7   97.86  4062.7   95.53
  4292.7   94.49  4429.9   95.21  4502.7   95.07  4612.7   92.58  4762.7   95.19
  4802.7   94.54  4842.7   92.21  4872.7   88.52  4980.6   88.91  4982.6   84.91
  5017.4   84.91  5019.4   88.91  5025.7   90.58  5175.7   92.26  5235.7   90.66
  5395.7   91.47  5445.7   93.47  5515.7   98.61  5595.7   105.5  5629.6  109.44
#Mann= 4 , 1 , 0
  2102.7      10       0  4429.9     .13       0  4980.6    .047       0
  5019.4     .13       0
Bank Sta=4980.6,5019.4
XS Rating Curve= 0 ,0
Exp/Cntr=0.3,0.1

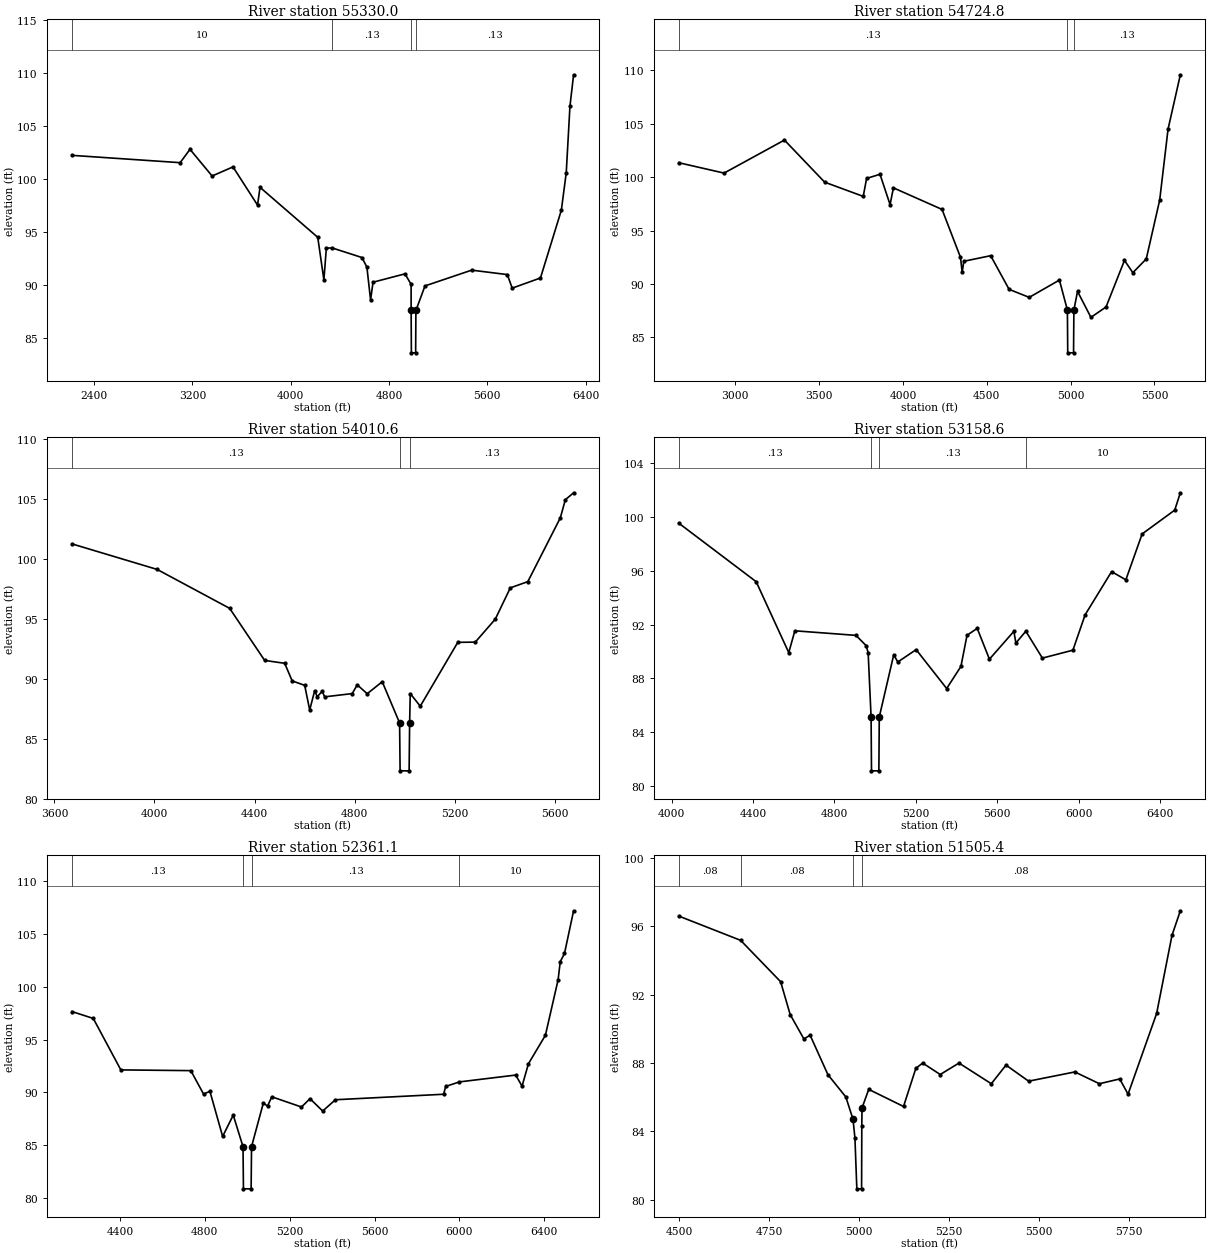
Type RM Length L Ch R = 1 ,55330.0 ,605.2,605.2,605.2
BEGIN DESCRIPTION:
Black Creek US 45.0
END DESCRIPTION:
#Sta/Elev= 30
  2220.5  102.26  3100.5  101.57  3180.5  102.83  3360.5  100.31  3530.5  101.17
  3730.5   97.56  3750.5   99.24  4220.5   94.52  4270.5    90.5  4290.5   93.51
  4339.9   93.51  4580.5   92.61  4620.5    91.7  4650.5   88.61  4670.5   90.28
  4930.5   91.07  4980.5   90.08  4980.6   87.61  4982.6   83.61  5017.4   83.61
  5019.4   87.61  5093.4   89.93  5473.4   91.42  5763.4      91  5803.4   89.72
  6033.4   90.68  6203.4   97.08  6243.4  100.64  6273.4   106.9  6303.1  109.87
#Mann= 4 , 1 , 0
  2220.5      10       0  4339.9     .13       0  4980.6    .047       0
  5019.4     .13       0
Bank Sta=4980.6,5019.4
XS Rating Curve= 0 ,0
Exp/Cntr=0.3,0.1

Type RM Length L Ch R = 1 ,54724.8 ,714.2,714.2,714.2
BEGIN DESCRIPTION:
Black Creek US 44.0
END DESCRIPTION:
#Sta/Elev= 30
  2663.1  101.35  2933.1  100.38  3293.1  103.47  3533.1   99.53  3763.1    98.2
  3783.1   99.88  3863.1  100.27  3923.1   97.43  3943.1      99  4233.1   96.98
  4343.1    92.5  4353.1    91.1  4363.1   92.13  4523.1   92.65  4633.1    89.5
  4753.1   88.75  4933.1   90.37  4980.7   87.56  4982.7   83.56  5017.4   83.56
  5019.4   87.56  5041.1   89.31  5121.1   86.88  5211.1   87.85  5321.1   92.21
  5371.1   91.06  5451.1   92.35  5531.1   97.85  5581.1   104.5  5654.3  109.58
#Mann= 3 , 1 , 0
  2663.1     .13       0  4980.7    .047       0  5019.4     .13       0
Bank Sta=4980.7,5019.4
XS Rating Curve= 0 ,0
Exp/Cntr=0.3,0.1

Type RM Length L Ch R = 1 ,54010.6 ,852,852,852
BEGIN DESCRIPTION:
Black Creek US 43.0
END DESCRIPTION:
#Sta/Elev= 30
  3670.5  101.27  4010.5   99.14  4300.5   95.89  4440.5   91.54  4520.5    91.3
  4550.5   89.83  4600.5   89.46  4620.5    87.4  4640.5   89.02  4650.5   88.51
  4670.5   88.96  4680.5    88.5  4790.5   88.77  4810.5    89.5  4850.5   88.76
  4910.5   89.76  4979.9   86.32  4981.9   82.32    5018   82.32    5020   86.32
  5022.5   88.77  5062.5   87.72  5212.5   93.05  5282.5   93.07  5362.5   94.99
  5422.5    97.6  5492.5   98.12  5622.5  103.45  5642.5  104.96  5675.5  105.54
#Mann= 3 , 1 , 0
  3670.5     .13       0  4979.9    .047       0    5020     .13       0
Bank Sta=4979.9,5020
XS Rating Curve= 0 ,0
Exp/Cntr=0.3,0.1

Type RM Length L Ch R = 1 ,53158.6 ,797.5,797.5,797.5
BEGIN DESCRIPTION:
Black Creek US 42.0
END DESCRIPTION:
#Sta/Elev= 30
  4035.5   99.54  4415.5   95.19  4575.5   89.92  4605.5   91.54  4905.5    91.2
  4955.5   90.44  4965.5   89.91  4979.9   85.13  4981.9   81.13  5018.1   81.13
  5020.1   85.13  5091.1   89.76  5111.1   89.22  5201.1   90.14  5351.1   87.25
  5421.1   88.89  5451.1   91.21  5501.1   91.72  5561.1   89.43  5681.1    91.5
  5691.1   90.63  5739.9   91.51  5821.1   89.51  5971.1    90.1  6031.1   92.73
  6161.1   95.94  6231.1   95.33  6311.1   98.74  6471.1  100.51  6498.7   101.8
#Mann= 4 , 1 , 0
  4035.5     .13       0  4979.9    .047       0  5020.1     .13       0
  5739.9      10       0
Bank Sta=4979.9,5020.1
XS Rating Curve= 0 ,0
Exp/Cntr=0.3,0.1

Type RM Length L Ch R = 1 ,52361.1 ,855.7,855.7,855.7
BEGIN DESCRIPTION:
Black Creek US 41.0
END DESCRIPTION:
#Sta/Elev= 30
  4173.8   97.66  4273.8   97.01  4403.8   92.13  4733.8   92.06  4793.8   89.84
  4823.8    90.1  4883.8   85.82  4933.8   87.84  4979.9   84.85  4981.9   80.85
  5018.1   80.85  5020.1   84.85  5075.6   88.98  5095.6    88.7  5115.6   89.58
  5255.6   88.61  5295.6    89.4  5355.6   88.23  5415.6    89.3  5925.6   89.82
  5935.6   90.56  5999.9   90.99  6265.6   91.64  6295.6   90.59  6325.6   92.71
  6405.6   95.41  6465.6  100.68  6475.6  102.39  6495.6  103.17  6538.6  107.22
#Mann= 4 , 1 , 0
  4173.8     .13       0  4979.9    .047       0  5020.1     .13       0
  5999.9      10       0
Bank Sta=4979.9,5020.1
XS Rating Curve= 0 ,0
Exp/Cntr=0.3,0.1

Type RM Length L Ch R = 1 ,51505.4 ,0,0,0
BEGIN DESCRIPTION:
Black Creek US 40.0 (Tie-in to Effective Study)
END DESCRIPTION:
#Sta/Elev= 30
 4499.01    96.6 4670.73   95.18 4781.77   92.76 4808.24   90.84 4846.36   89.41
 4863.65   89.63 4913.08   87.32 4962.76   86.02 4982.77   84.71 4988.11   83.61
  4993.4   80.64  5006.6   80.64  5007.2   84.34 5007.76   85.37 5026.41   86.46
 5123.04   85.46 5157.25   87.69 5176.23      88 5224.96   87.33 5277.04      88
 5366.75   86.79 5407.64   87.88 5470.42   86.94 5598.75   87.48 5666.95   86.79
 5723.31   87.07 5746.52   86.18 5825.87    90.9 5868.49   95.47  5891.7   96.91
#Mann= 4 ,-1 , 0
 4499.01     .08       0 4670.73     .08       0 4982.77     .05       0
 5007.76     .08       0
Bank Sta=4982.77,5007.76
XS Rating Curve= 0 ,0
Exp/Cntr=0.3,0.1

Chan Stop Cuts=-1
Use User Specified Reach Order=0