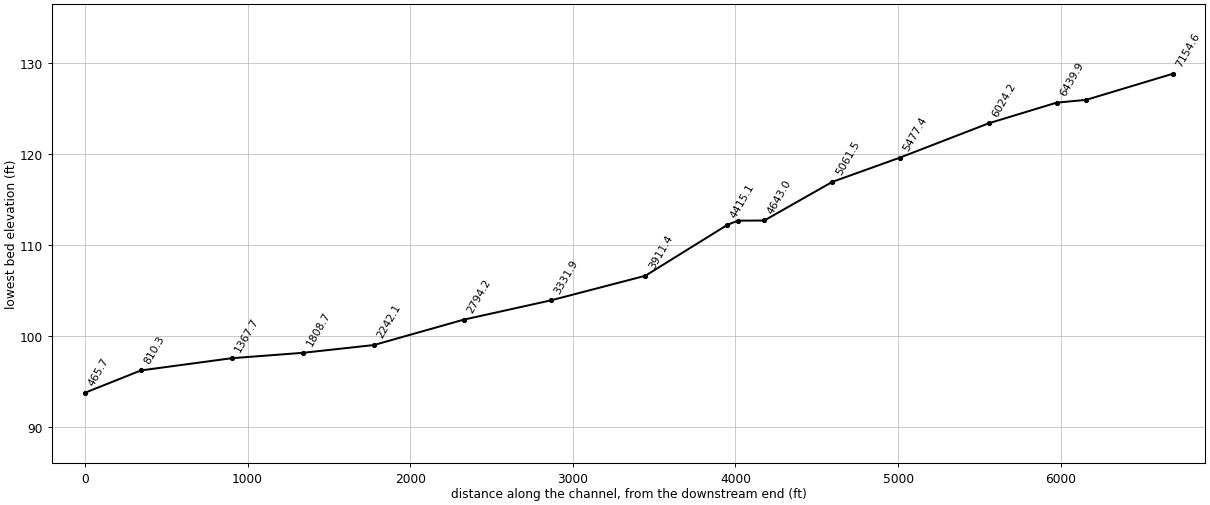
--- Bloomery_Swamp_Trib1_021220.prj (project) ---

Proj Title=Bloomery Trib 1
Current Plan=p02
Default Exp/Contr=0.3,0.1
English Units
Geom File=g01
Flow File=f01
Flow File=f02
Plan File=p01
Plan File=p02
Y Axis Title=Elevation
X Axis Title(PF)=Main Channel Distance
X Axis Title(XS)=Station
BEGIN DESCRIPTION:
NEUSE RIVER BASIN
Little Contentnea Creek Sub-basin
BLOOMERY SWAMP TRIB 1
(Flood Hazard, Floodway) Model
Prepared by: Andrew J. Bonner   Date: 11/6/2002
Watershed Concepts
3333 Regency Pkwy
Cary, North Carolina 27511
END DESCRIPTION:
DSS Export Rating Curves= 0
DSS Export Rating Curve Sorted= 0
DSS Export Volume Flow Curves= 0
DXF OffsetX= 0
DXF OffsetY= 0
DXF ScaleX= 1
DXF ScaleY= 10

--- Bloomery_Swamp_Trib1_021220.p02 (plan) ---

Plan Title=Multi_Profile
Program Version=4.00
Short Identifier=Multi_Profile
Geom File=g01
Flow File=f02
Subcritical Flow
K Sum by GR= 0
Std Step Tol= 0.01
Critical Tol= 0.01
Num of Std Step Trials= 20
Max Error Tol= 0.3
Flow Tol Ratio= 0.001
Split Flow NTrial= 30
Split Flow Tol= 0.02
Split Flow Ratio= 0.02
Log Output Level= 0
Friction Slope Method= 1
Unsteady Friction Slope Method= 2
Unsteady Bridges Friction Slope Method= 1
Parabolic Critical Depth
Global Vel Dist= 0 , 0 , 0
Global Log Level= 0
CheckData=True
Encroach Param=-1 ,10,10, 2
Computation Interval=1HOUR
Output Interval=1HOUR
Run HTab= 0
Run UNet= 0
Run PostProcess= 0
Run WQNet= 0
UNET Theta= 1
UNET Theta Warmup= 1
UNET ZTol= 0.02
UNET ZSATol= 0.1
UNET MxIter= 20
UNET MaxInSteps= 20
UNET DtIC= 0
UNET DtMin= 0
UNET MaxCRTS= 20
UNET WFStab= 2
UNET SFStab= 1
UNET WFX= 1
UNET SFX= 1
UNET DSS MLevel= 4
UNET DZMax Abort= 100
UNET Convert EG Bridges=-1
UNET Use Existing IB Tables=-1
UNET Froude Reduction=False
UNET Froude Limit= 1
UNET Froude Power= 10
UNET Time Slicing=0,0, 5
Instantaneous Interval=1HOUR
Write IC File= 0
Echo Input=False
Echo Output=False
Write Detailed= 0
Detailed Automatic Start=False, 10
WQ ULTIMATE=-1
WQ Max Comp Step=1HOUR
WQ Output Interval=15MIN
WQ Output Selected Increments= 0
WQ Output face flow=0
WQ Output face velocity=0
WQ Output face area=0
WQ Output face dispersion=0
WQ Output cell volume=0
WQ Output cell surface area=0
WQ Output cell continuity=0
WQ Output face conc=0
WQ Output face dconc_dx=0
WQ Output face courant=0
WQ Output face peclet=0
WQ Output face adv mass=0
WQ Output face disp mass=0
WQ Output cell mass=0
WQ Output cell source sink temp=0
WQ Output cell source sink nsm=0
WQ Output MaxMinRange=-1
WQ Daily Max Min Mean=-1
WQ Daily Range=0
WQ Daily Time=0
WQ Create Restart=0
WQ Fixed Restart=0
WQ System Summary=False
Sorting and Armoring Iterations= 10
XS Update Threshold= 0.02
Hydraulics Update Threshold= 0.02
Energy Slope Method= 1
Volume Change Method= 0
XS Weighting Method= 0
Number of US Weighted Cross Sections= 1
Number of DS Weighted Cross Sections= 1
Upstream XS Weight=0.25
Main XS Weight=0.5
Downstream XS Weight=0.25
Number of DS XS's Weighted with US Boundary= 1
Upstream Boundary Weight= 1
Weight of XSs Associated with US Boundary= 0
Number of US XS's Weighted with DS Boundary= 1
Downstream Boundary Weight= 0.5
Weight of XSs Associated with DS Boundary= 0.5
Sediment Output Level= 4
Mass or Volume Output= 0
Output Increment Type= 1
Profile and TS Output Increment= 10
XS Output Flag= 0
XS Output Increment= 10
Disregard all LS=0
Disregard all Conn=0
Disregard all Breaches=0
Disregard all Pumps=0

--- Bloomery_Swamp_Trib1_021220.p01 (plan) ---

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Plan Title=100 Year Single
Version=Version 3.0.1  Mar 2001
Short Identifier=Plan01
Geom File=g01
Flow File=f01
Encroach River=Bloomery Trib 1
Encroach Reach=Reach - 1
Encroach Node=7154.6
       1    4985    5035
Encroach Node=6621.9
       1    4970    5040
Encroach Node=6530.9
       1    4970    5040
Encroach Node=6439.9
       1    4970    5040
Encroach Node=6024.2
       4      .7
Encroach Node=5477.4
       4      .7
Encroach Node=5061.5
       4      .7
Encroach Node=4643.0
       4      .7
Encroach Node=4480.1
       1    4950    5050
Encroach Node=4447.6
       1    4950    5050
Encroach Node=4415.1
       1    4950    5050
Encroach Node=3911.4
       1    4975    5100
Encroach Node=3331.9
       4      .7
Encroach Node=2794.2
       4      .7
Encroach Node=2242.1
       4      .7
Encroach Node=1808.7
       4      .7
Encroach Node=1367.7
       4      .7
Encroach Node=810.3
       4      .7
Encroach Node=465.7
       4      .7
Write Velocity= 0

--- Bloomery_Swamp_Trib1_021220.f02 (steady flow) ---

Flow Title=Multi_Profile
Program Version=4.00
Number of Profiles= 7
Profile Names=10yr,25yr,50yr,500yr,100yr-10%,100yr-20%,100yr-35%
River Rch & RM=Bloomery Trib 1,Reach - 1       ,7154.6
     169     245     313     622     463     594     725
River Rch & RM=Bloomery Trib 1,Reach - 1       ,4643.0
     395     561     707    1353     991    1271    1553
Boundary for River Rch & Prof#=Bloomery Trib 1,Reach - 1       , 1
Up Type= 0
Dn Type= 3
Dn Slope=0.0071
DSS Import GetInterval= 0
DSS Import GetPeak= 0
DSS Import FillOption= 0

--- Bloomery_Swamp_Trib1_021220.f01 (steady flow) ---

Flow Title= 100 Year Single
Version=Version 3.0.1  Mar 2001
Number of Profiles= 2
Profile Names=100-Year,AFW
River Rch & RM=Bloomery Trib 1,Reach - 1       ,7154.6
     392     392
River Rch & RM=Bloomery Trib 1,Reach - 1       ,4643.0
     873     873
Boundary for River Rch & Prof#=Bloomery Trib 1,Reach - 1       , 1
Up Type= 0
Dn Type= 3
Dn Slope=.0071
Boundary for River Rch & Prof#=Bloomery Trib 1,Reach - 1       , 2
Up Type= 0
Dn Type= 3
Dn Slope=.0071
DSS Import GetInterval= 0
DSS Import GetPeak= 0
DSS Import FillOption= 0

--- Bloomery_Swamp_Trib1_021220.g01 (geometry) ---

Geom Title=Geom 01 by CodeH2 for Windows

River Reach=Bloomery Trib 1,Reach - 1
Reach XY= 30
   .081752840525   .393553995599   .126050310254   .396372616722
   .154158633373   .382851899146   .175507525432   .389256937855
   .212867158806   .371823060766   .233857947600   .379649379791
   .252004320305   .372533700924   .274420100329   .384987530534
   .280112643423   .411672717879   .312846621670   .425904075614
   .314269757443   .441204176771   .342734328369   .471802523629
   .365150108394   .480697586077   .407489789247   .524816650511
   .432224890936   .537159152682   .471820350395   .527961650689
   .555887411182   .478688125787   .564526420518   .438693743002
   .667871682982   .381423197000   .714265538104   .325750199761
   .752018528433   .309752446647   .776976285002   .251201635087
   .786253571661   .262720314202   .800972914674   .246401566970
   .796812979336   .205128774083   .819210204787   .198729301745
   .821768880448   .180171017513   .860482997674   .151376175182
   .897597710681   .099863113281   .932152220902   .093463640944

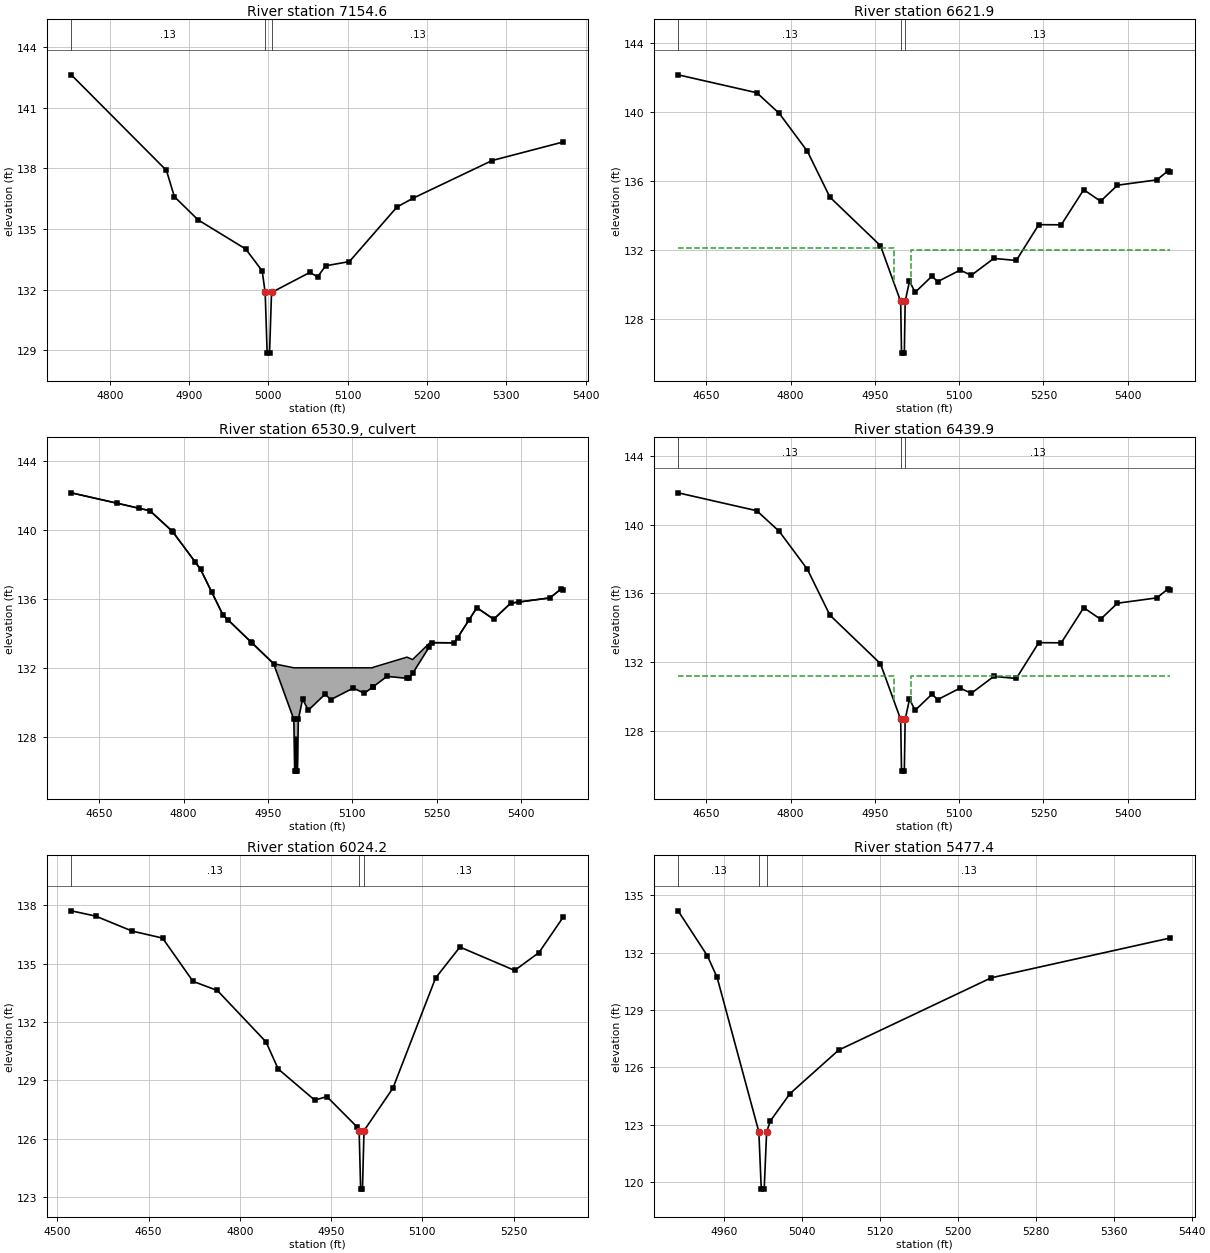
Type RM Length L Ch R = 1 ,7154.6,532.7,532.7,532.7
BEGIN DESCRIPTION:
Bloomery Swamp Trib 1 10.0
END DESCRIPTION:
#Sta/Elev= 18
  4751.5  142.63  4871.5   137.9  4881.5   136.6  4911.5  135.45  4971.5  134.01
  4992.2  132.93    4996  131.86  4998.5  128.86  5001.5  128.86    5004  131.86
  5052.2  132.85  5062.2  132.64  5072.2  133.18  5102.2  133.39  5162.2  136.09
  5182.2  136.52  5282.2  138.39    5372  139.31
#Mann= 3 , 1 , 0
 4751.50    0.13       0    4996   0.048       0    5004    0.13       0
Bank Sta=4996.00,5004.00
Exp/Cntr=0.5,0.3

Type RM Length L Ch R = 1 ,6621.9,182,182,182
BEGIN DESCRIPTION:
Upstream Section of Bridge/Culvert/Weir
END DESCRIPTION:
#Sta/Elev= 26
    4600  142.15    4740  141.11    4780  139.91    4830  137.71    4870  135.05
    4960  132.23    4996  128.99  4997.5  125.99  5002.5  125.99    5004  128.99
  5011.7  130.17  5021.7  129.52  5051.7  130.46  5061.7  130.14  5101.7  130.81
  5121.7  130.51  5161.7  131.49  5201.7  131.37  5241.7  133.45  5281.7  133.44
  5321.7  135.48  5351.7  134.81  5381.7  135.74  5451.7  136.05  5471.7  136.57
  5475.6   136.5
#Mann= 3 , 1 , 0
 4600.00    0.13       0    4996   0.048       0    5004    0.13       0
#XS Ineff= 2 , 0
       0    4985   132.1    5015       0     132
Bank Sta=4996.00,5004.00
Exp/Cntr=0.5,0.3

Type RM Length L Ch R = 2 ,6530.9,,,
BEGIN DESCRIPTION:
Unnamed Rd - TOR
Structure ID: BST1 - Unnamed Rd
Approximate Survey Structure
END DESCRIPTION:
Bridge Culvert--1,0,-1,-1, 0
Deck Dist Width WeirC Skew NumUp NumDn MinLoCord MaxHiCord MaxSubmerge Is_Ogee
10,162,3,,43,43,,,0.95,0,1,1,,
    4600    4681    4721    4740    4780    4781    4821    4830  4849.7    4870
  4879.7  4919.7  4921.1    4960    4996  4997.5    5000  5002.5    5004  5011.7
  5021.7  5051.7  5061.7  5101.7  5121.7  5136.2  5137.3  5161.7  5197.3  5201.7
  5207.3  5237.3  5241.7  5281.7  5287.3  5307.3  5321.7  5351.7  5381.7  5396.6
  5451.7  5471.7  5475.6
  142.16  141.56  141.26  141.12  139.92  139.88  138.12  137.72  136.41  135.06
  134.76   133.5  133.46  132.24     132     132     132     132     132     132
     132     132     132     132     132     132  132.03  132.27  132.62  132.56
  132.48  133.43  133.46  133.45  133.74  134.76  135.49  134.82  135.75  135.82
  136.06  136.58  136.51
  142.16  141.56  141.26  141.12  139.92  139.88  138.12  137.72  136.41  135.06
  134.76   133.5  133.46  132.24     129     126     126     126     129  130.18
  129.53  130.47  130.15  130.82  130.52  130.88   130.9   131.5  131.39  131.38
  131.67  133.23  133.46  133.45  133.74  134.76  135.49  134.82  135.75  135.82
  136.06  136.58  136.51
    4600    4681    4721    4740    4780    4781    4821    4830  4849.7    4870
  4879.7  4919.7  4921.1    4960    4996  4997.5    5000  5002.5    5004  5011.7
  5021.7  5051.7  5061.7  5101.7  5121.7  5136.2  5137.3  5161.7  5197.3  5201.7
  5207.3  5237.3  5241.7  5281.7  5287.3  5307.3  5321.7  5351.7  5381.7  5396.6
  5451.7  5471.7  5475.6
  142.06  141.47  141.17  141.03  139.83  139.79  138.03  137.63  136.32  134.97
  134.67  133.41  133.37  132.15     132     132     132     132     132     132
     132     132     132     132     132     132  132.03  132.27  132.62  132.56
  132.48  133.43  133.37  133.36  133.65  134.67   135.4  134.73  135.66  135.73
  135.96  136.48  136.41
  141.96  141.36  141.06  140.92  139.72  139.68  137.92  137.52  136.21  134.86
  134.56   133.3  133.26  132.04   128.8   125.8   125.8   125.8   128.8  129.98
  129.33  130.27  129.95  130.62  130.32  130.68   130.7   131.3  131.19  131.18
  131.47  133.03  133.26  133.25  133.54  134.56  135.29  134.62  135.55  135.62
  135.86  136.38  136.31
BR Coef= 1 , 0 , 0 ,1.25, 0 ,,,0.8,-1,2,0,
Wspro=,,,, 1 ,,,, 0 ,,,, 0 ,,,,-1 ,-1 ,-1 , 0 , 0 , 0 , 0 , 0
Culvert=1,2.0,,162.0,0.024,0.9,1.0,2,3,126.00,4998.52,125.80,4998.52,Culvert #1  ,0,10
Culvert=1,2.0,,162.0,0.024,0.9,1.0,2,3,126.00,5001.52,125.80,5001.52,Culvert #2  ,0,10
BC Design=,, 0 ,, 0 ,,,,,,
BR U #Sta/Elev= 43
    4600  142.16    4681  141.56    4721  141.26    4740  141.12    4780  139.92
    4781  139.88    4821  138.12    4830  137.72  4849.7  136.41    4870  135.06
  4879.7  134.76  4919.7   133.5  4921.1  133.46    4960  132.24    4996     129
  4997.5     126    5000     126  5002.5     126    5004     129  5011.7  130.18
  5021.7  129.53  5051.7  130.47  5061.7  130.15  5101.7  130.82  5121.7  130.52
  5136.2  130.88  5137.3   130.9  5161.7   131.5  5197.3  131.39  5201.7  131.38
  5207.3  131.67  5237.3  133.23  5241.7  133.46  5281.7  133.45  5287.3  133.74
  5307.3  134.76  5321.7  135.49  5351.7  134.82  5381.7  135.75  5396.6  135.82
  5451.7  136.06  5471.7  136.58  5475.6  136.51
BR U #Mann= 3
 4600.00    0.13    4996   0.048    5004    0.13
BR U Banks=4996.00,5004.00
BR D #Sta/Elev= 43
    4600  141.96    4681  141.36    4721  141.06    4740  140.92    4780  139.72
    4781  139.68    4821  137.92    4830  137.52  4849.7  136.21    4870  134.86
  4879.7  134.56  4919.7   133.3  4921.1  133.26    4960  132.04    4996   128.8
  4997.5   125.8    5000   125.8  5002.5   125.8    5004   128.8  5011.7  129.98
  5021.7  129.33  5051.7  130.27  5061.7  129.95  5101.7  130.62  5121.7  130.32
  5136.2  130.68  5137.3   130.7  5161.7   131.3  5197.3  131.19  5201.7  131.18
  5207.3  131.47  5237.3  133.03  5241.7  133.26  5281.7  133.25  5287.3  133.54
  5307.3  134.56  5321.7  135.29  5351.7  134.62  5381.7  135.55  5396.6  135.62
  5451.7  135.86  5471.7  136.38  5475.6  136.31
BR D #Mann= 3
 4600.00    0.13    4996   0.048    5004    0.13
BR D Banks=4996.00,5004.00

Type RM Length L Ch R = 1 ,6439.9,415.7,415.7,415.7
BEGIN DESCRIPTION:
Downstream Section of Bridge/Culvert/Weir
END DESCRIPTION:
#Sta/Elev= 26
    4600  141.84    4740   140.8    4780   139.6    4830   137.4    4870  134.74
    4960  131.92    4996  128.68  4997.5  125.68  5002.5  125.68    5004  128.68
  5011.7  129.86  5021.7  129.21  5051.7  130.15  5061.7  129.83  5101.7   130.5
  5121.7   130.2  5161.7  131.18  5201.7  131.06  5241.7  133.14  5281.7  133.13
  5321.7  135.17  5351.7   134.5  5381.7  135.43  5451.7  135.74  5471.7  136.26
  5475.6  136.19
#Mann= 3 , 1 , 0
 4600.00    0.13       0    4996   0.048       0    5004    0.13       0
#XS Ineff= 2 , 0
       0    4985   131.2    5015       0   131.2
Bank Sta=4996.00,5004.00
Exp/Cntr=0.5,0.3

Type RM Length L Ch R = 1 ,6024.2,546.8,546.8,546.8
BEGIN DESCRIPTION:
Bloomery Swamp Trib 1 9.5
END DESCRIPTION:
#Sta/Elev= 21
    4523  137.71    4563  137.44    4623  136.67    4673  136.31    4723  134.09
    4763  133.62    4843  130.98    4863  129.59    4923  127.99    4943  128.17
    4993   126.6    4996  126.42  4998.5  123.42  5001.5  123.42    5004  126.42
  5051.6  128.61  5121.6  134.26  5161.6  135.85  5251.6  134.65  5291.6  135.57
  5331.6   137.4
#Mann= 3 , 1 , 0
 4523.00    0.13       0    4996   0.048       0    5004    0.13       0
Bank Sta=4996.00,5004.00
Exp/Cntr=0.3,0.1

Type RM Length L Ch R = 1 ,5477.4,415.9,415.9,415.9
BEGIN DESCRIPTION:
Bloomery Swamp Trib 1 9.0
END DESCRIPTION:
#Sta/Elev= 12
  4913.2  134.19  4943.2  131.84  4953.2  130.71    4996  122.64  4998.5  119.64
  5001.5  119.64    5004  122.64  5007.9  123.21  5027.9  124.63  5077.9  126.91
  5234.5  130.69    5418  132.77
#Mann= 3 , 1 , 0
 4913.20    0.13       0    4996   0.048       0    5004    0.13       0
Bank Sta=4996.00,5004.00
Exp/Cntr=0.3,0.1

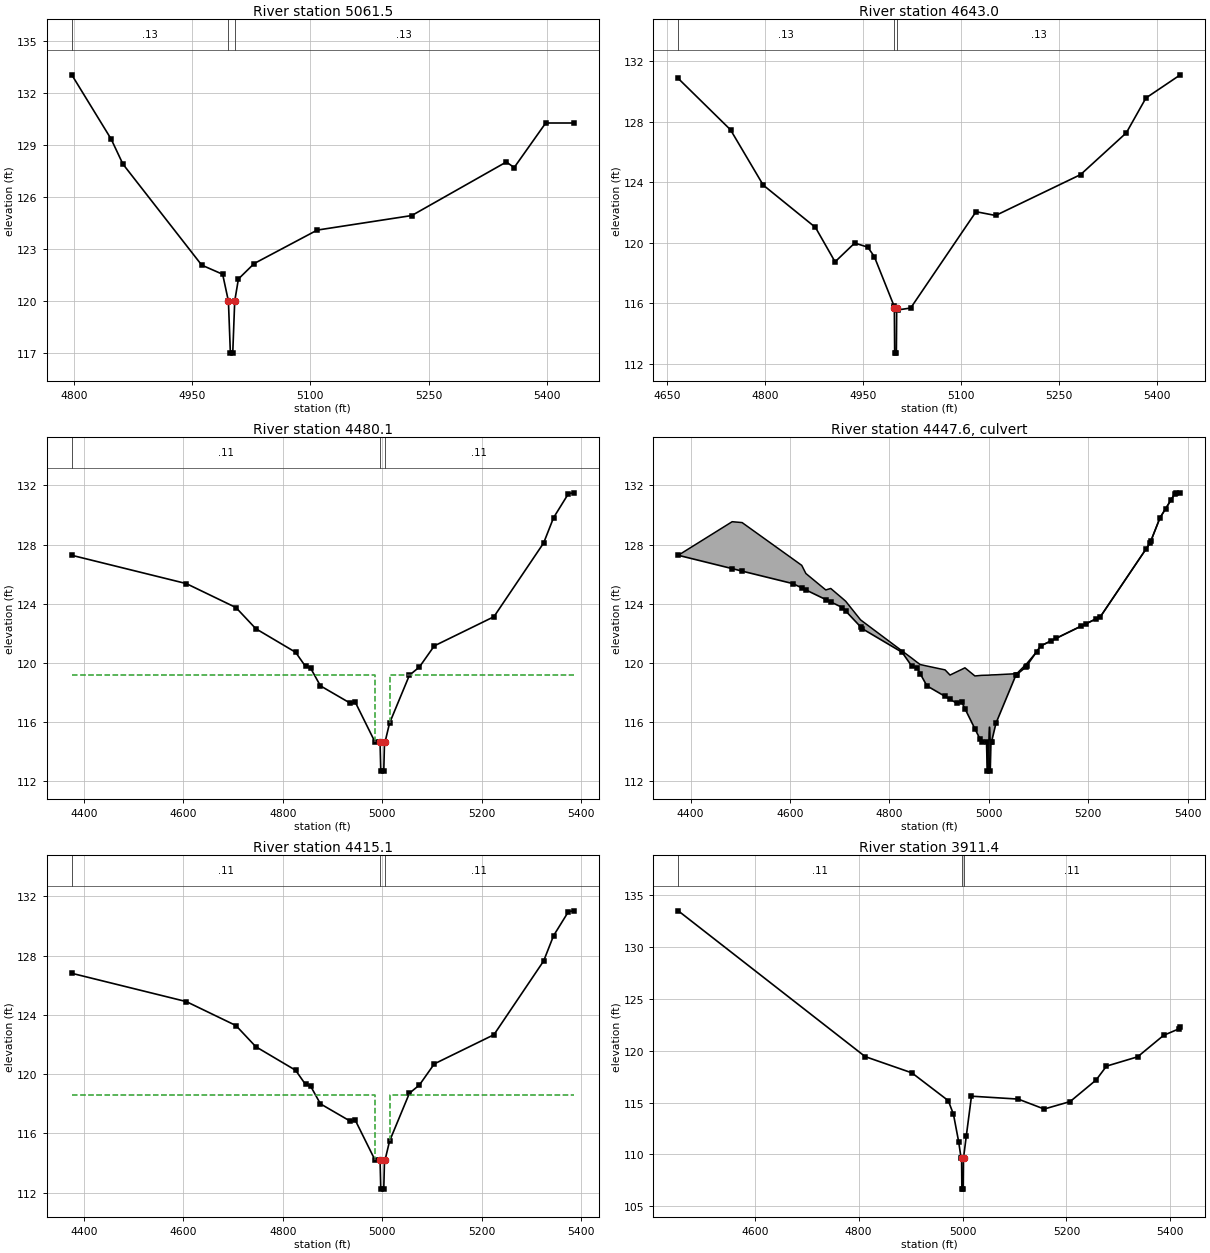
Type RM Length L Ch R = 1 ,5061.5,418.5,418.5,418.5
BEGIN DESCRIPTION:
Bloomery Swamp Trib 1 8.0
END DESCRIPTION:
#Sta/Elev= 17
  4797.2  133.03  4847.2  129.32  4862.1  127.88  4962.1  122.05  4988.7  121.52
    4996  119.97  4998.5  116.97  5001.5  116.97    5004  119.97  5008.7  121.25
  5028.7  122.14  5108.7  124.07  5228.7  124.91  5348.7     128  5358.7  127.68
  5398.7  130.25  5434.4  130.25
#Mann= 3 , 1 , 0
 4797.20    0.13       0    4996   0.048       0    5004    0.13       0
Bank Sta=4996.00,5004.00
Exp/Cntr=0.3,0.1

Type RM Length L Ch R = 1 ,4643.0,162.9,162.9,162.9
BEGIN DESCRIPTION:
Bloomery Swamp Trib 1 7.0
END DESCRIPTION:
#Sta/Elev= 21
  4667.5  130.86  4747.5  127.47  4797.5  123.82  4877.5  121.02  4907.5  118.75
  4937.5  119.99  4957.5  119.72  4967.5   119.1  4997.5  115.86  4998.2  115.72
  4998.7  112.72  5001.3  112.72  5001.8  115.72  5003.2  115.57  5023.2   115.7
  5123.2  122.06  5153.2  121.81  5283.2  124.51  5353.2  127.27  5383.2  129.57
  5435.8   131.1
#Mann= 3 , 1 , 0
 4667.50    0.13       0  4998.2   0.048       0  5001.8    0.13       0
Bank Sta=4998.20,5001.80
Exp/Cntr=0.5,0.3

Type RM Length L Ch R = 1 ,4480.1,65,65,65
BEGIN DESCRIPTION:
Upstream Section of Bridge/Culvert/Weir
END DESCRIPTION:
#Sta/Elev= 25
  4375.3  127.28  4605.6  125.37  4705.6  123.75  4745.6  122.32  4825.6  120.73
  4845.6  119.77  4855.6  119.67  4875.6  118.46  4935.6  117.29  4945.6  117.36
  4985.6  114.65  4995.5   114.7    4997   112.7    5003   112.7  5004.5   114.7
  5005.6  114.67  5014.6  115.94  5054.6  119.18  5074.6  119.73  5104.6  121.16
  5224.6  123.13  5324.6  128.11  5344.6  129.82  5374.6  131.45  5385.4   131.5
#Mann= 3 , 1 , 0
 4375.30    0.11       0  4995.5   0.048       0  5004.5    0.11       0
#XS Ineff= 2 , 0
       0    4985   119.2    5015       0   119.2
Bank Sta=4995.50,5004.50
Exp/Cntr=0.5,0.3

Type RM Length L Ch R = 2 ,4447.6,,,
BEGIN DESCRIPTION:
Wilson Christian Church Rd-TOR
Structure ID: Wilson Christian Church Rd
Approximate Survey Structure
END DESCRIPTION:
Bridge Culvert--1,0,-1,-1, 0
Deck Dist Width WeirC Skew NumUp NumDn MinLoCord MaxHiCord MaxSubmerge Is_Ogee
10,45,3,,52,52,,,0.95,0,1,1,,
  4375.3  4483.8  4503.8  4605.6  4623.8  4632.1  4672.1  4682.1  4705.6  4712.1
  4742.1  4745.6  4825.6  4845.6  4855.6  4862.1  4875.6  4912.1  4922.1  4935.6
  4945.6  4952.1  4972.1  4982.1  4985.6  4995.5    4997    5003  5004.5  5005.6
  5014.6  5054.6  5056.1  5074.6  5076.1  5096.1  5104.6  5126.1  5136.1  5186.1
  5196.1  5216.1  5224.6  5316.1  5324.6  5326.1  5344.6  5356.1  5366.1  5374.6
  5376.1  5385.4
  127.28  129.55  129.49  127.04   126.6  126.05  124.94  125.04  124.37  124.18
  122.92  122.83  120.82  120.32  120.06   119.9   119.8  119.54  119.19  119.41
  119.57  119.68  119.13  119.16  119.17  119.18  119.18  119.19   119.2   119.2
  119.21  119.28  119.28   119.9  119.95  120.75  121.16  121.51  121.68   122.5
  122.66  122.99  123.13  127.69  128.11  128.24  129.82  130.44  130.99  131.45
  131.46   131.5
  127.28  126.38  126.21  125.37  125.08  124.94  124.29  124.13  123.75  123.52
  122.45  122.32  120.73  119.77  119.67  119.28  118.46  117.75  117.55  117.29
  117.36  116.92  115.56  114.89  114.65   114.7   112.7   112.7   114.7  114.67
  115.94  119.18  119.22  119.73   119.8  120.75  121.16  121.51  121.68   122.5
  122.66  122.99  123.13  127.69  128.11  128.24  129.82  130.44  130.99  131.45
  131.46   131.5
  4375.3  4483.8  4503.8  4605.6  4623.8  4632.1  4672.1  4682.1  4705.6  4712.1
  4742.1  4745.6  4825.6  4845.6  4855.6  4862.1  4875.6  4912.1  4922.1  4935.6
  4945.6  4952.1  4972.1  4982.1  4985.6  4995.5    4997    5003  5004.5  5005.6
  5014.6  5054.6  5056.1  5074.6  5076.1  5096.1  5104.6  5126.1  5136.1  5186.1
  5196.1  5216.1  5224.6  5316.1  5324.6  5326.1  5344.6  5356.1  5366.1  5374.6
  5376.1  5385.4
  127.18  129.55  129.49  127.04   126.6  126.05  124.94  125.04  124.37  124.18
  122.92  122.83  120.82  120.32  120.06   119.9   119.8  119.54  119.19  119.41
  119.57  119.68  119.13  119.16  119.17  119.18  119.18  119.19   119.2   119.2
  119.21  119.28  119.28   119.9  119.95  120.66  121.07  121.42  121.59  122.41
  122.57   122.9  123.04   127.6  128.02  128.15  129.73  130.35   130.9  131.36
  131.37   131.4
  127.08  126.18  126.01  125.17  124.88  124.74  124.09  123.93  123.55  123.32
  122.25  122.12  120.53  119.57  119.47  119.08  118.26  117.55  117.35  117.09
  117.16  116.72  115.36  114.69  114.45   114.5   112.5   112.5   114.5  114.47
  115.74  118.98  119.02  119.53   119.6  120.55  120.96  121.31  121.48   122.3
  122.46  122.79  122.93  127.49  127.91  128.04  129.62  130.24  130.79  131.25
  131.26   131.3
BR Coef= 1 , 0 , 0 ,1.25, 0 ,,,0.8,-1,2,0,
Wspro=,,,, 1 ,,,, 0 ,,,, 0 ,,,,-1 ,-1 ,-1 , 0 , 0 , 0 , 0 , 0
Culvert=1,2.0,,45.0,0.024,0.9,1.0,2,3,112.70,4998.05,112.50,4998.05,Culvert #1  ,0,10
Culvert=1,3.0,,45.0,0.024,0.9,1.0,2,3,112.70,5001.55,112.50,5001.55,Culvert #2  ,0,10
BC Design=,, 0 ,, 0 ,,,,,,
BR U #Sta/Elev= 52
  4375.3  127.28  4483.8  126.38  4503.8  126.21  4605.6  125.37  4623.8  125.08
  4632.1  124.94  4672.1  124.29  4682.1  124.13  4705.6  123.75  4712.1  123.52
  4742.1  122.45  4745.6  122.32  4825.6  120.73  4845.6  119.77  4855.6  119.67
  4862.1  119.28  4875.6  118.46  4912.1  117.75  4922.1  117.55  4935.6  117.29
  4945.6  117.36  4952.1  116.92  4972.1  115.56  4982.1  114.89  4985.6  114.65
  4995.5   114.7    4997   112.7    5003   112.7  5004.5   114.7  5005.6  114.67
  5014.6  115.94  5054.6  119.18  5056.1  119.22  5074.6  119.73  5076.1   119.8
  5096.1  120.75  5104.6  121.16  5126.1  121.51  5136.1  121.68  5186.1   122.5
  5196.1  122.66  5216.1  122.99  5224.6  123.13  5316.1  127.69  5324.6  128.11
  5326.1  128.24  5344.6  129.82  5356.1  130.44  5366.1  130.99  5374.6  131.45
  5376.1  131.46  5385.4   131.5
BR U #Mann= 3
 4375.30    0.11  4995.5   0.048  5004.5    0.11
BR U Banks=4995.50,5004.50
BR D #Sta/Elev= 52
  4375.3  127.08  4483.8  126.18  4503.8  126.01  4605.6  125.17  4623.8  124.88
  4632.1  124.74  4672.1  124.09  4682.1  123.93  4705.6  123.55  4712.1  123.32
  4742.1  122.25  4745.6  122.12  4825.6  120.53  4845.6  119.57  4855.6  119.47
  4862.1  119.08  4875.6  118.26  4912.1  117.55  4922.1  117.35  4935.6  117.09
  4945.6  117.16  4952.1  116.72  4972.1  115.36  4982.1  114.69  4985.6  114.45
  4995.5   114.5    4997   112.5    5003   112.5  5004.5   114.5  5005.6  114.47
  5014.6  115.74  5054.6  118.98  5056.1  119.02  5074.6  119.53  5076.1   119.6
  5096.1  120.55  5104.6  120.96  5126.1  121.31  5136.1  121.48  5186.1   122.3
  5196.1  122.46  5216.1  122.79  5224.6  122.93  5316.1  127.49  5324.6  127.91
  5326.1  128.04  5344.6  129.62  5356.1  130.24  5366.1  130.79  5374.6  131.25
  5376.1  131.26  5385.4   131.3
BR D #Mann= 3
 4375.30    0.11  4995.5   0.048  5004.5    0.11
BR D Banks=4995.50,5004.50

Type RM Length L Ch R = 1 ,4415.1,503.7,503.7,503.7
BEGIN DESCRIPTION:
Downstream Section of Bridge/Culvert/Weir
END DESCRIPTION:
#Sta/Elev= 25
  4375.3  126.81  4605.6   124.9  4705.6  123.28  4745.6  121.85  4825.6  120.26
  4845.6   119.3  4855.6   119.2  4875.6  117.99  4935.6  116.82  4945.6  116.89
  4985.6  114.18  4995.5  114.23    4997  112.23    5003  112.23  5004.5  114.23
  5005.6   114.2  5014.6  115.47  5054.6  118.71  5074.6  119.26  5104.6  120.69
  5224.6  122.66  5324.6  127.64  5344.6  129.35  5374.6  130.98  5385.4  131.03
#Mann= 3 , 1 , 0
 4375.30    0.11       0  4995.5   0.048       0  5004.5    0.11       0
#XS Ineff= 2 , 0
       0    4985   118.6    5015       0   118.6
Bank Sta=4995.50,5004.50
Exp/Cntr=0.5,0.3

Type RM Length L Ch R = 1 ,3911.4,579.5,579.5,579.5
BEGIN DESCRIPTION:
Bloomery Swamp Trib 1 6.0
END DESCRIPTION:
#Sta/Elev= 22
  4452.5   133.5  4812.5  119.43  4902.5  117.86  4972.5  115.18  4982.5  113.87
  4992.5  111.23  4997.2  109.64  4998.2  109.64  4998.7  106.64  5001.4  106.64
  5001.9  109.64  5007.2  111.75  5017.2  115.61  5107.2  115.33  5157.2  114.37
  5207.2  115.09  5257.2  117.17  5277.2  118.51  5337.2  119.41  5387.2  121.48
  5417.2  122.12  5419.4  122.25
#Mann= 3 , 1 , 0
 4452.50    0.11       0  4998.2   0.048       0  5001.9    0.11       0
Bank Sta=4998.20,5001.90
Exp/Cntr=0.3,0.1

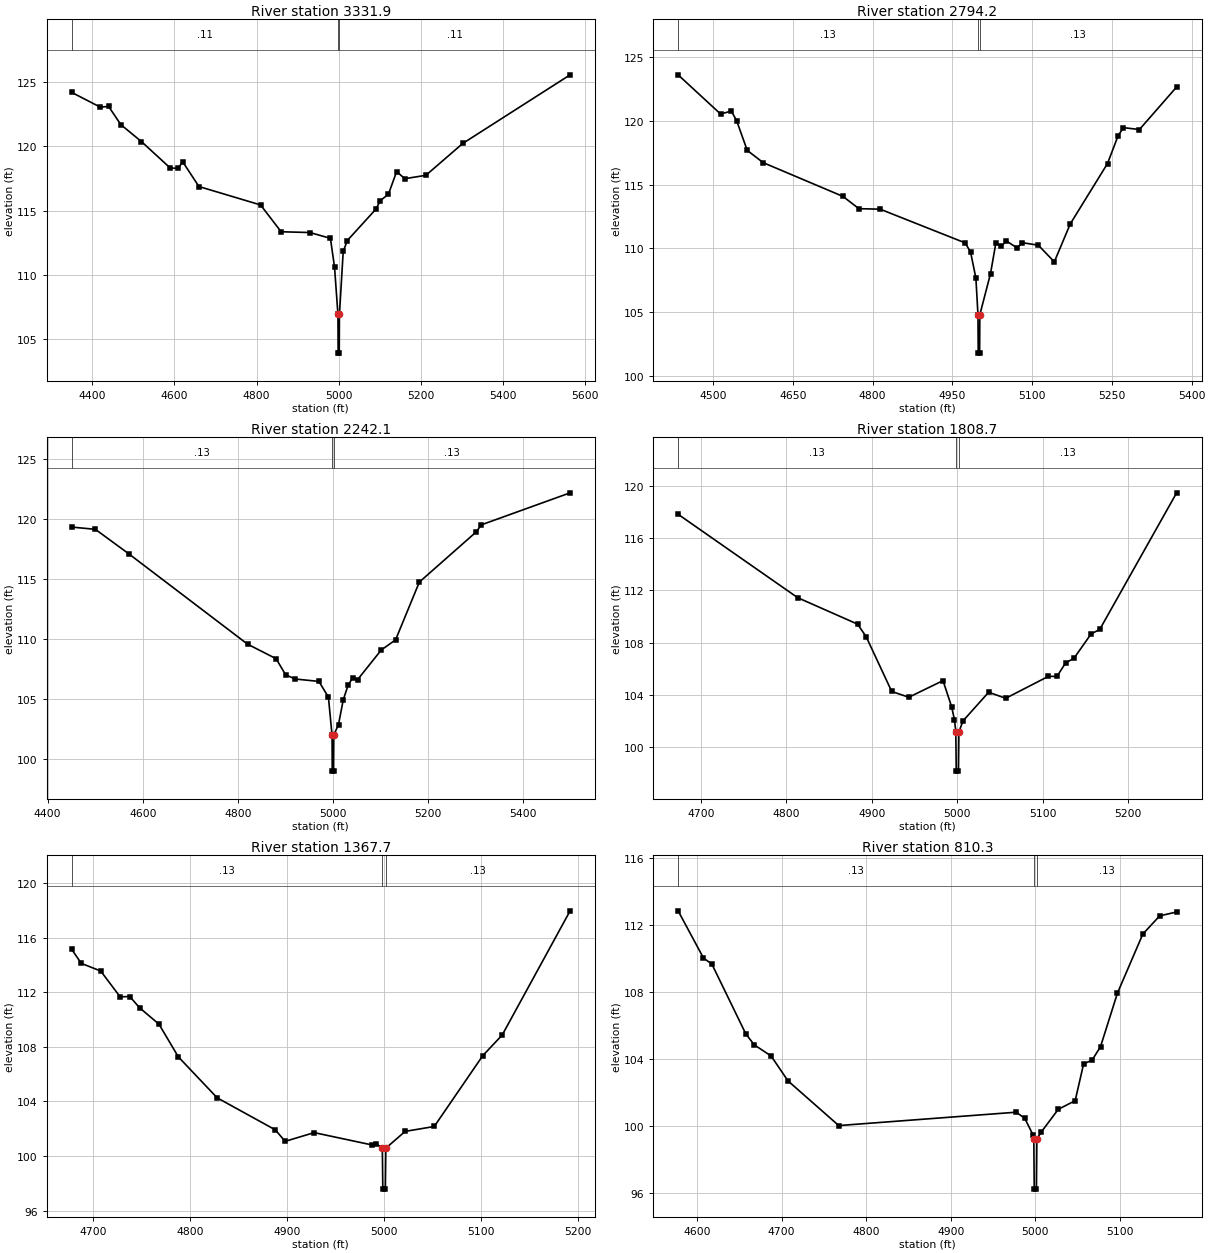
Type RM Length L Ch R = 1 ,3331.9,537.7,537.7,537.7
BEGIN DESCRIPTION:
Bloomery Swamp Trib 1 5.0
END DESCRIPTION:
#Sta/Elev= 28
  4349.9  124.18  4419.9  123.03  4439.9  123.09  4469.9  121.67  4519.9  120.36
  4589.9  118.31  4609.9  118.28  4619.9  118.81  4659.9  116.87  4809.9  115.44
  4859.9  113.36  4929.9   113.3  4979.9  112.85  4989.9  110.61  4998.2  106.94
  4998.7  103.94  5001.3  103.94  5001.8  106.94    5011  111.83    5021  112.68
    5091  115.13    5101  115.77    5121  116.27    5141  118.03    5161  117.48
  5212.2  117.74  5302.2  120.22  5563.3  125.54
#Mann= 3 , 1 , 0
 4349.90    0.11       0  4998.2   0.048       0  5001.8    0.11       0
Bank Sta=4998.20,5001.80
Exp/Cntr=0.3,0.1

Type RM Length L Ch R = 1 ,2794.2,552.1,552.1,552.1
BEGIN DESCRIPTION:
Bloomery Swamp Trib 1 4.0
END DESCRIPTION:
#Sta/Elev= 30
  4434.3  123.58  4514.3  120.51  4534.3  120.75  4544.3     120  4564.3  117.67
  4594.3  116.71  4744.3  114.07  4774.3  113.11  4814.3  113.07  4974.3  110.43
  4984.3  109.71  4994.3  107.68  4998.2  104.81  4998.7  101.81  5001.3  101.81
  5001.7  104.81  5021.8  108.03  5031.8  110.41  5041.8  110.17  5051.8  110.58
  5071.8  110.04  5081.8  110.45  5111.8  110.25  5141.8  108.95  5171.8  111.92
  5241.8  116.64  5261.8  118.82  5271.8  119.45  5301.8   119.3  5371.8  122.63
#Mann= 3 , 1 , 0
 4434.30    0.13       0  4998.2   0.048       0  5001.7    0.13       0
Bank Sta=4998.20,5001.70
Exp/Cntr=0.3,0.1

Type RM Length L Ch R = 1 ,2242.1,433.4,433.4,433.4
BEGIN DESCRIPTION:
Bloomery Swamp Trib 1 3.0
END DESCRIPTION:
#Sta/Elev= 24
  4450.5  119.34  4500.5  119.15  4570.5  117.12  4820.5  109.59  4880.5  108.38
  4900.5  107.04  4920.5  106.69  4970.5  106.49  4990.5  105.18  4998.1  102.02
  4998.6   99.02  5001.3   99.02  5001.8  102.02  5011.7   102.9  5021.7  104.96
  5031.7  106.15  5041.7  106.81  5051.7  106.63  5101.7  109.11  5131.7  109.95
  5181.7  114.76  5301.7  118.95  5311.7  119.52  5498.7  122.19
#Mann= 3 , 1 , 0
 4450.50    0.13       0  4998.1   0.048       0  5001.8    0.13       0
Bank Sta=4998.10,5001.80
Exp/Cntr=0.3,0.1

Type RM Length L Ch R = 1 ,1808.7,441,441,441
BEGIN DESCRIPTION:
Bloomery Swamp Trib 1 2.5
END DESCRIPTION:
#Sta/Elev= 23
  4673.2  117.81  4813.2  111.43  4883.2  109.41  4893.2  108.46  4923.2  104.26
  4943.2  103.82  4983.2  105.09  4993.2  103.11  4996.6  102.11  4998.2  101.17
  4998.7   98.17  5001.3   98.17  5001.8  101.17  5006.6  102.01  5036.6   104.2
  5056.6  103.74  5106.6  105.42  5116.6  105.41  5126.6  106.44  5136.6  106.81
  5156.6  108.67  5166.6     109  5256.6  119.45
#Mann= 3 , 1 , 0
 4673.20    0.13       0  4998.2   0.048       0  5001.8    0.13       0
Bank Sta=4998.20,5001.80
Exp/Cntr=0.3,0.1

Type RM Length L Ch R = 1 ,1367.7,557.4,557.4,557.4
BEGIN DESCRIPTION:
Bloomery Swamp Trib 1 2.0
END DESCRIPTION:
#Sta/Elev= 23
    4678  115.15    4688  114.11    4708  113.55    4728  111.66    4738  111.68
    4748  110.86    4768  109.66    4788  107.26    4828  104.26    4888  101.91
    4898  101.07    4928  101.71    4988   100.8  4991.7   100.9  4998.2  100.57
  4998.7   97.57  5001.3   97.57  5001.8  100.57  5021.7   101.8  5051.7  102.16
  5101.7  107.35  5121.7  108.86  5191.7  117.96
#Mann= 3 , 1 , 0
 4678.00    0.13       0  4998.2   0.048       0  5001.8    0.13       0
Bank Sta=4998.20,5001.80
Exp/Cntr=0.3,0.1

Type RM Length L Ch R = 1 ,810.3,344.6,344.6,344.6
BEGIN DESCRIPTION:
Bloomery Swamp Trib 1 1.0
END DESCRIPTION:
#Sta/Elev= 25
  4577.5  112.87  4607.5  110.05  4617.5  109.68  4657.5  105.52  4667.5  104.86
  4687.5  104.19  4707.5   102.7  4767.5  100.03  4977.5  100.83  4987.5  100.46
  4997.1   99.49  4998.2   99.23  4998.7   96.23  5001.3   96.23  5001.8   99.23
  5007.1   99.65  5027.1     101  5047.1  101.52  5057.1  103.72  5067.1  103.94
  5077.1  104.75  5097.1  107.95  5127.1  111.48  5147.1  112.57  5167.1   112.8
#Mann= 3 , 1 , 0
 4577.50    0.13       0  4998.2   0.048       0  5001.8    0.13       0
Bank Sta=4998.20,5001.80
Exp/Cntr=0.3,0.1

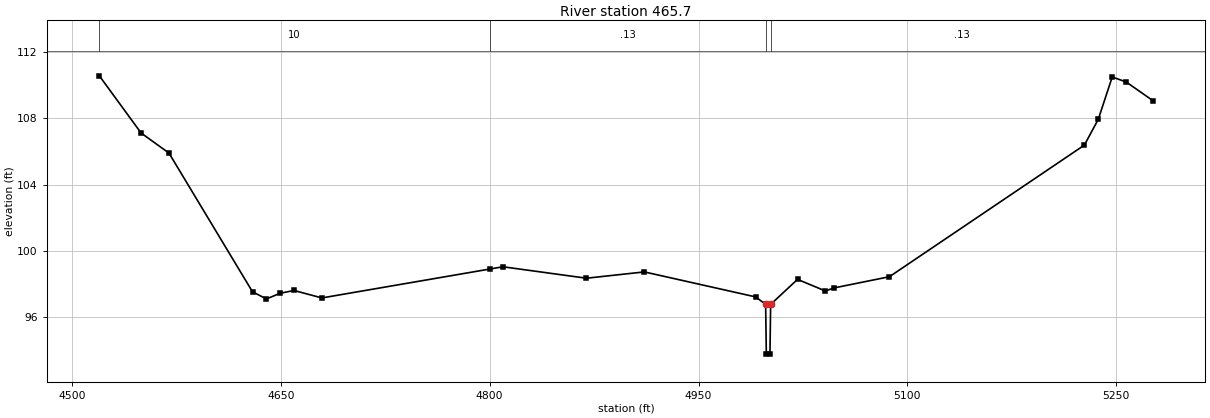
Type RM Length L Ch R = 1 ,465.7,0,0,0
BEGIN DESCRIPTION:
Bloomery Swamp Trib 1 0.5
END DESCRIPTION:
#Sta/Elev= 26
  4519.7  110.56  4549.7  107.11  4569.7   105.9  4629.7   97.53  4639.7    97.1
  4649.5   97.44  4659.5   97.61  4679.5   97.16  4799.9    98.9  4809.5   99.04
  4869.5   98.35  4911.1   98.73  4991.1   97.22  4998.2   96.77  4998.7   93.77
  5001.3   93.77  5001.8   96.77  5021.1   98.28  5041.1   97.58  5047.1   97.76
  5087.1   98.44  5227.1  106.38  5237.1  107.94  5247.1  110.49  5257.1  110.19
  5276.2  109.07
#Mann= 4 , 1 , 0
 4519.70      10       0  4799.9    0.13       0  4998.2   0.048       0
  5001.8    0.13       0
Bank Sta=4998.20,5001.80
Exp/Cntr=0.3,0.1

Chan Stop Cuts=-1