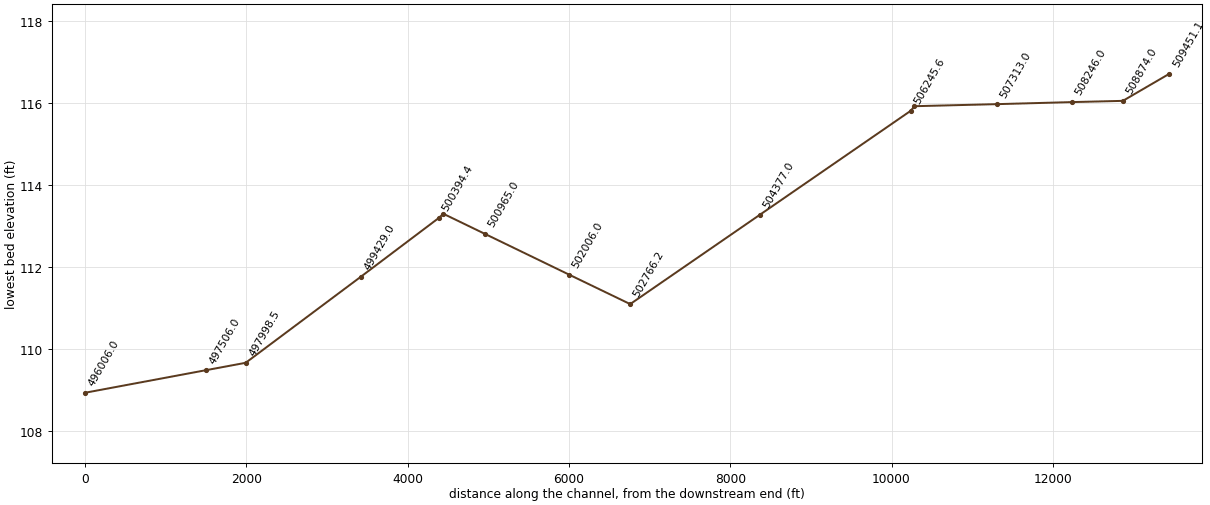
--- CONTENTNEA_FINAL.PRJ (project) ---

Proj Title=Contentnea
Current Plan=p01
Default Exp/Contr=0.3,0.1
English Units
Geom File=g01
Flow File=f05
Flow File=f02
Flow File=f01
Plan File=p05
Plan File=p02
Plan File=p01
Y Axis Title=Elevation
X Axis Title(PF)=Main Channel Distance
X Axis Title(XS)=Station
BEGIN DESCRIPTION:
END DESCRIPTION:
DSS Export Rating Curves= 0
DSS Export Rating Curve Sorted= 0
DSS Export Volume Flow Curves= 0
DXF OffsetX= 0
DXF OffsetY= 0
DXF ScaleX= 1
DXF ScaleY= 10

--- CONTENTNEA_FINAL.p01 (plan) ---

Plan Title=Contentnea
Program Version=4.00
Short Identifier=Base Plan
Geom File=g01
Flow File=f01
Subcritical Flow
K Sum by GR= 0
Std Step Tol= 0.01
Critical Tol= 0.01
Num of Std Step Trials= 20
Max Error Tol= 0.3
Flow Tol Ratio= 0.001
Split Flow NTrial= 30
Split Flow Tol= 0.02
Split Flow Ratio= 0.02
Log Output Level= 0
Friction Slope Method= 1
Unsteady Friction Slope Method= 2
Unsteady Bridges Friction Slope Method= 1
Parabolic Critical Depth
Global Vel Dist= 0 , 0 , 0
Global Log Level= 0
CheckData=True
Encroach Param=-1 ,0,0, 0
Computation Interval=1HOUR
Output Interval=1HOUR
Run HTab= 0
Run UNet= 0
Run PostProcess= 0
Run WQNet= 0
UNET Theta= 1
UNET Theta Warmup= 1
UNET ZTol= 0.02
UNET ZSATol= 0.05
UNET MxIter= 20
UNET MaxInSteps= 0
UNET DtIC= 0
UNET DtMin= 0
UNET MaxCRTS= 20
UNET WFStab= 2
UNET SFStab= 1
UNET WFX= 1
UNET SFX= 1
UNET DSS MLevel= 4
UNET DZMax Abort= 100
UNET Convert EG Bridges=-1
UNET Use Existing IB Tables=-1
UNET Froude Reduction=False
UNET Froude Limit= 1
UNET Froude Power= 10
UNET Time Slicing=0,0, 5
Instantaneous Interval=1HOUR
Write IC File= 0
Echo Input=False
Echo Output=False
Write Detailed= 0
Detailed Automatic Start=False, 10
WQ ULTIMATE=-1
WQ Max Comp Step=1HOUR
WQ Output Interval=15MIN
WQ Output Selected Increments= 0
WQ Output face flow=0
WQ Output face velocity=0
WQ Output face area=0
WQ Output face dispersion=0
WQ Output cell volume=0
WQ Output cell surface area=0
WQ Output cell continuity=0
WQ Output face conc=0
WQ Output face dconc_dx=0
WQ Output face courant=0
WQ Output face peclet=0
WQ Output face adv mass=0
WQ Output face disp mass=0
WQ Output cell mass=0
WQ Output cell source sink temp=0
WQ Output cell source sink nsm=0
WQ Output MaxMinRange=-1
WQ Daily Max Min Mean=-1
WQ Daily Range=0
WQ Daily Time=0
WQ Create Restart=0
WQ Fixed Restart=0
WQ System Summary=False
Sorting and Armoring Iterations= 10
XS Update Threshold= 0.02
Hydraulics Update Threshold= 0.02
Energy Slope Method= 1
Volume Change Method= 0
XS Weighting Method= 0
Number of US Weighted Cross Sections= 1
Number of DS Weighted Cross Sections= 1
Upstream XS Weight=0.25
Main XS Weight=0.5
Downstream XS Weight=0.25
Number of DS XS's Weighted with US Boundary= 1
Upstream Boundary Weight= 1
Weight of XSs Associated with US Boundary= 0
Number of US XS's Weighted with DS Boundary= 1
Downstream Boundary Weight= 0.5
Weight of XSs Associated with DS Boundary= 0.5
Sediment Output Level= 4
Mass or Volume Output= 0
Output Increment Type= 1
Profile and TS Output Increment= 10
XS Output Flag= 0
XS Output Increment= 10
Disregard all LS=0
Disregard all Conn=0
Disregard all Breaches=0
Disregard all Pumps=0

--- CONTENTNEA_FINAL.p02 (plan) ---

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Plan Title=Contentnea Creek Floodway
Short Identifier=100YRFW
Geom File=g01
Flow File=f02
Encroach Param= 0 ,0,0, 2
Encroach River=Main Stem
Encroach Reach=Reach - 1
Encroach Node=509451.1
       1    4065    5350
Encroach Node=508874.0
       1    4300    5569
Encroach Node=508246.0
       1    4370  5659.6
Encroach Node=507313.0
       1    4360    5600
Encroach Node=506290.6
       1    3900    5065
Encroach Node=506245.6
       1    3900    5065
Encroach Node=504377.0
       1 4687.26 6172.39
Encroach Node=502766.2
       1    3700 5132.25
Encroach Node=502006.0
       1    3600 5036.95
Encroach Node=500965.0
       1    3200 5379.76
Encroach Node=500449.4
       1    3000    5075
Encroach Node=500394.4
       1    3000    5075
Encroach Node=499429.0
       1    3800  5393.6
Encroach Node=497998.5
       1    4630 5990.74
Encroach Node=497506.0
       1    4815 6107.74
Encroach Node=496006.0
       1    3580 5133.24
Encroach Node=494506.0
       1    4800 5488.48
Encroach Node=493006.0
       1    4300 5324.17
Encroach Node=492313.0
       1    4175    5200
Encroach Node=491168.0
       1 4818.75    5450
Encroach Node=490137.0
       1 4971.15    5800
Encroach Node=488385.0
       1    4550    5070
Encroach Node=487385.5
       1    4500    5070
Encroach Node=486780.0
       1 4732.54    5300
Encroach Node=486163.0
       1    4750    5500
Encroach Node=485451.9
       1    4600    5650
Encroach Node=484006.0
       1    4500    5200
Encroach Node=482659.0
       1    4650    5530
Encroach Node=481797.5
       1    4900    6200
Encroach Node=481469.6
       1    4900    6200
Encroach Node=481420.6
       1    4900    6200
Encroach Node=479419.4
       1    4930    5955
Encroach Node=477969.9
       1    4874    5170
Encroach Node=477888.9
       1    4874    5170
Encroach Node=477647.1
       1    4835    5132
Encroach Node=477567.1
       1    4835    5132
Encroach Node=474310.0
       1    3050    5048
Encroach Node=472006.0
       1    3800    5570
Encroach Node=470506.0
       1    3500    5449
Encroach Node=469658.0
       1    3650    5500
Encroach Node=468751.2
       1    3200    5150
Encroach Node=468700.2
       1    3200    5150
Encroach Node=466006.0
       1    3435  5415.7
Encroach Node=463720.0
       1    4080    6500
Encroach Node=463006.0
       1    3650    6350
Encroach Node=461506.0
       1    3300    6100
Encroach Node=460006.0
       1    2650    5300
Encroach Node=458059.0
       1    3100    5040
Encroach Node=456022.0
       1    4100    6000
Encroach Node=454809.0
       1    4600    6300
Encroach Node=453590.0
       1    4300    5900
Encroach Node=452506.0
       1    4000    5400
Encroach Node=450666.4
       1    4265    5400
Encroach Node=450518.4
       1    4265    5400
Encroach Node=450107.0
       1    4036    5200
Encroach Node=449186.0
       1    4873    5800
Encroach Node=449135.0
       1    4873  5804.8
Encroach Node=447348.0
       1    4850    6575
Encroach Node=446118.0
       1    4373    6660
Encroach Node=444457.3
       1    4000    6600
Encroach Node=443384.0
       1    3810    6700
Encroach Node=441165.0
       1    4780    7200
Encroach Node=438756.0
       1    4780    7200
Encroach Node=438095.4
       1    4730    7150
Encroach Node=435680.0
       1    4710    7110
Encroach Node=434506.0
       1    4180    7250
Encroach Node=432818.0
       1    3400    6900
Encroach Node=427843.4
       1    2400    5500
Encroach Node=427796.4
       1    2400    5500
Encroach Node=426697.0
       1  2438.1  5050.8
Encroach Node=425351.0
       1 2278.23  5076.2
Encroach Node=423652.0
       1  3882.4  6117.6
Encroach Node=421855.0
       1  4161.8  5838.2
Encroach Node=421006.0
       1    4600    6000
Encroach Node=419820.0
       1    4750    5180
Encroach Node=419644.0
       1    4925    5095
Encroach Node=419537.0
       1    4920    5100
Encroach Node=419158.0
       1    4900    5130
Encroach Node=417825.2
       1    4800    5150
Encroach Node=416837.0
       1    4700    5250
Encroach Node=415675.0
       1    4540    6300
Encroach Node=414744.0
       1    4500    6300
Encroach Node=413457.4
       1    4850    5090
Encroach Node=413410.4
       1    4925    5070
Encroach Node=409909.0
       1    4350    6920
Encroach Node=409351.0
       1    4100    6950
Encroach Node=408852.0
       1    4050    6880
Encroach Node=407855.0
       1    4300    7200
Encroach Node=406324.7
       1    4680    5135
Encroach Node=406256.7
       1    4680    5135
Encroach Node=405306.0
       1    3400 5883.71
Encroach Node=403991.3
       1 2396.28 5591.72
Encroach Node=403924.3
       1 2760.98 5359.11
Encroach Node=401626.0
       1    2805    5430
Encroach Node=399658.0
       1    2480 5662.86
Encroach Node=394476.0
       1     850    5180
UNET ZSATol= 0.1
UNET MaxInSteps= 20

--- CONTENTNEA_FINAL.p05 (plan) ---

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Plan Title=25-yr and Future
Geom File=g01
Flow File=f05
UNET Convert EG Bridges= 0

--- CONTENTNEA_FINAL.f01 (steady flow) ---

Flow Title= Contentnea
Program Version=4.00
Number of Profiles= 4
Profile Names=10-YEAR,50-YEAR,100-YEAR,500-YEAR
River Rch & RM=Main Stem,Reach - 1       ,509451.1
    4140   11000   14800   28300
River Rch & RM=Main Stem,Reach - 1       ,506290.6
    4890   11800   15600   29100
River Rch & RM=Main Stem,Reach - 1       ,497506
    5170   12100   15900   29300
River Rch & RM=Main Stem,Reach - 1       ,479419.4
    6510   13600   17300   30600
River Rch & RM=Main Stem,Reach - 1       ,463720
    7450   14500   18200   31400
River Rch & RM=Main Stem,Reach - 1       ,450107
    7850   14900   18600   31800
River Rch & RM=Main Stem,Reach - 1       ,449186
    8460   15500   19200   32300
River Rch & RM=Main Stem,Reach - 1       ,438756
   11700   18700   22100   34600
River Rch & RM=Main Stem,Reach - 1       ,421855
   12000   19000   22400   34800
River Rch & RM=Main Stem,Reach - 1       ,417825.2
   12700   19700   23100   35500
River Rch & RM=Main Stem,Reach - 1       ,394476.0
   13300   20600   24100   36800
Boundary for River Rch & Prof#=Main Stem,Reach - 1       , 1
Up Type= 0
Dn Type= 1
Dn Known WS=76.75
Boundary for River Rch & Prof#=Main Stem,Reach - 1       , 2
Up Type= 0
Dn Type= 1
Dn Known WS=77.73
Boundary for River Rch & Prof#=Main Stem,Reach - 1       , 3
Up Type= 0
Dn Type= 1
Dn Known WS=78.11
Boundary for River Rch & Prof#=Main Stem,Reach - 1       , 4
Up Type= 0
Dn Type= 1
Dn Known WS=79.27
DSS Import GetInterval= 0
DSS Import GetPeak= 0
DSS Import FillOption= 0

--- CONTENTNEA_FINAL.f02 (steady flow) ---

Flow Title=Contentnea Creek Floodway
Program Version=4.00
Number of Profiles= 2
Profile Names=100-YEAR,100-yr FW
River Rch & RM=Main Stem,Reach - 1       ,509451.1
   14800   14800
River Rch & RM=Main Stem,Reach - 1       ,506290.6
   15600   15600
River Rch & RM=Main Stem,Reach - 1       ,497506
   15900   15900
River Rch & RM=Main Stem,Reach - 1       ,479419.4
   17300   17300
River Rch & RM=Main Stem,Reach - 1       ,463720
   18200   18200
River Rch & RM=Main Stem,Reach - 1       ,450107
   18600   18600
River Rch & RM=Main Stem,Reach - 1       ,449186
   19200   19200
River Rch & RM=Main Stem,Reach - 1       ,438756
   22100   22100
River Rch & RM=Main Stem,Reach - 1       ,421855
   22400   22400
River Rch & RM=Main Stem,Reach - 1       ,417825.2
   23100   23100
River Rch & RM=Main Stem,Reach - 1       ,394476.0
   24100   24100
Boundary for River Rch & Prof#=Main Stem,Reach - 1       , 1
Up Type= 0
Dn Type= 1
Dn Known WS=78.11
Boundary for River Rch & Prof#=Main Stem,Reach - 1       , 2
Up Type= 0
Dn Type= 1
Dn Known WS=79.07
DSS Import GetInterval= 0
DSS Import GetPeak= 0
DSS Import FillOption= 0

--- CONTENTNEA_FINAL.f05 (steady flow) ---

Flow Title=25-yr and Future
Program Version=4.00
Number of Profiles= 4
Profile Names=25-YEAR,100yr-10%,100yr-20%,100yr-35%
River Rch & RM=Main Stem,Reach - 1       ,509451.1
    8030   17300   22100   27000
River Rch & RM=Main Stem,Reach - 1       ,506290.6
    8810   17800   22800   27900
River Rch & RM=Main Stem,Reach - 1       ,497506
    9090   18000   23100   28200
River Rch & RM=Main Stem,Reach - 1       ,479419.4
   10450   18900   24200   29500
River Rch & RM=Main Stem,Reach - 1       ,463720
   11380   19400   24900   30400
River Rch & RM=Main Stem,Reach - 1       ,450107
   11770   19600   25200   30800
River Rch & RM=Main Stem,Reach - 1       ,449186
   12370   20000   25600   31300
River Rch & RM=Main Stem,Reach - 1       ,438756
   15480   21600   27600   33800
River Rch & RM=Main Stem,Reach - 1       ,421855
   15780   21700   27800   34000
River Rch & RM=Main Stem,Reach - 1       ,417825.2
   16460   22200   28400   34700
River Rch & RM=Main Stem,Reach - 1       ,394476.0
   17160   23000   29500   36100
Boundary for River Rch & Prof#=Main Stem,Reach - 1       , 1
Up Type= 0
Dn Type= 1
Dn Known WS=77.31
Boundary for River Rch & Prof#=Main Stem,Reach - 1       , 2
Up Type= 0
Dn Type= 1
Dn Known WS=78
Boundary for River Rch & Prof#=Main Stem,Reach - 1       , 3
Up Type= 0
Dn Type= 1
Dn Known WS=78.65
Boundary for River Rch & Prof#=Main Stem,Reach - 1       , 4
Up Type= 0
Dn Type= 1
Dn Known WS=79.22
DSS Import GetInterval= 0
DSS Import GetPeak= 0
DSS Import FillOption= 0

--- CONTENTNEA_FINAL.g01 (geometry) ---

Geom Title=Geom 01 by CodeH2 for Windows
Program Version=4.00

River Reach=Main Stem       ,Reach - 1
Reach XY= 2
             0.5            0.95             0.5            0.05

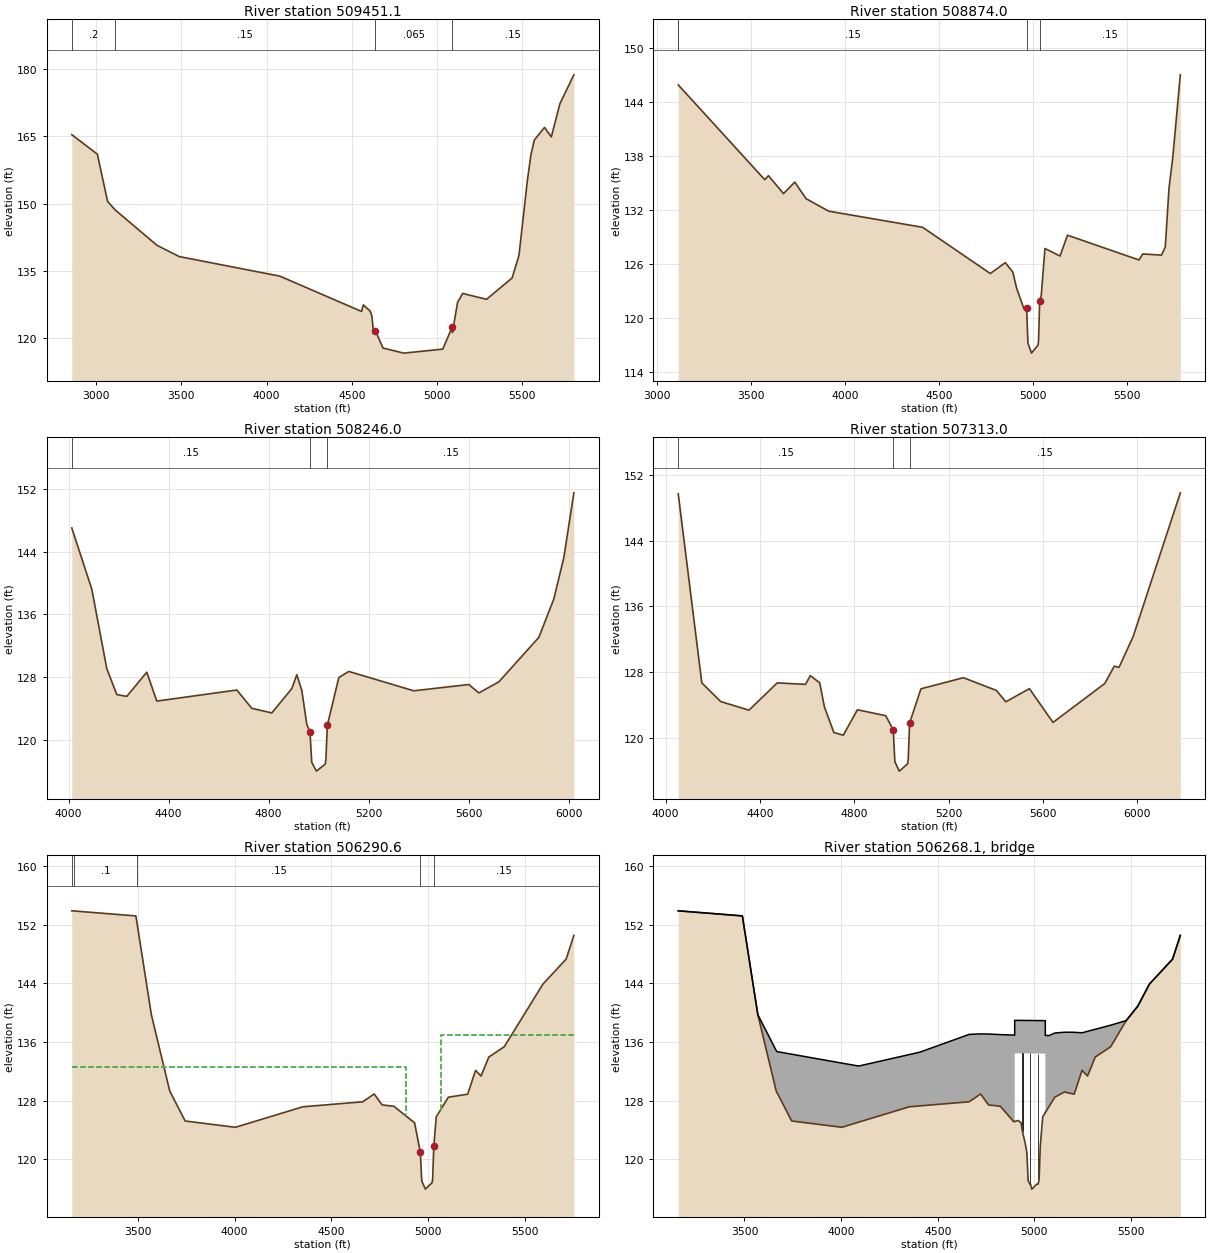
Type RM Length L Ch R = 1 ,509451.1,577.1,577.1,577.1
BEGIN DESCRIPTION:
Cross Section Dam-DS
END DESCRIPTION:
#Sta/Elev= 30
  2857.3  165.37  3007.3  161.03  3067.3  150.52    3112   148.6  3357.3  140.72
  3487.3  138.22  4077.3  133.86  4557.3  125.99  4567.3  127.46  4607.3  126.09
  4617.3  124.99  4627.3  121.31 4637.95  121.72  4682.8  117.84    4805  116.71
 5033.15   117.6 5089.05  122.55  5090.1  121.31  5120.1  128.01  5150.1     130
  5290.1   128.7  5440.1  133.45  5480.1  138.44  5530.1  155.33  5550.1  160.82
  5570.1  164.16  5630.1  166.99  5670.1  164.88  5720.1  172.24  5802.1   178.7
#Mann= 4 , 1 , 0
  2857.3      .2       0    3112     .15       0 4637.95    .065       0
 5089.05     .15       0
Bank Sta=4637.95,5089.05
XS Rating Curve= 0 ,0
Exp/Cntr=0.3,0.1

Type RM Length L Ch R = 1 ,508874.0,628,628,628
BEGIN DESCRIPTION:
Cross Section Contentnea Creek 64.0
END DESCRIPTION:
#Sta/Elev= 30
    3112  145.94    3572  135.38    3592  135.82    3672  133.82    3732  135.11
    3792  133.26    3912  131.87    4412  130.07    4772  124.92    4852  126.13
    4892  125.07    4912  123.28    4952  120.94  4965.3  121.06  4972.2  117.18
    4991  116.05  5026.1  116.94  5028.9  117.53  5034.7  121.89  5042.8  122.44
  5062.8  127.71  5142.8  126.87  5182.8  129.19  5562.8  126.43  5582.8   127.1
  5682.8  126.97  5702.8  127.87  5722.8  134.46  5742.8  137.86  5782.8  147.06
#Mann= 4 , 1 , 0
    3112      .2       0    3112     .15       0  4965.3    .065       0
  5034.7     .15       0
Bank Sta=4965.3,5034.7
XS Rating Curve= 0 ,0
Exp/Cntr=0.3,0.1

Type RM Length L Ch R = 1 ,508246.0,933,933,933
BEGIN DESCRIPTION:
Cross Section Contentnea Creek 63.0
END DESCRIPTION:
#Sta/Elev= 30
  4012.6  147.02  4092.6  139.24  4152.6   129.1  4192.6  125.78  4232.6  125.55
  4312.6  128.63  4352.6  124.95  4672.6  126.36  4732.6  124.03  4812.6  123.44
  4892.6  126.54  4912.6  128.31  4932.6  126.31  4952.6  121.97  4965.3  121.03
  4972.2  117.15    4991  116.02  5026.1  116.91  5028.9   117.5  5034.7  121.86
  5080.5  127.94  5120.5  128.73  5380.5  126.26  5600.5  127.06  5640.5  125.99
  5720.5   127.4  5880.5  133.07  5940.5  137.97  5980.5  143.25  6020.5   151.5
#Mann= 3 , 1 , 0
  4012.6     .15       0  4965.3    .065       0  5034.7     .15       0
Bank Sta=4965.3,5034.7
XS Rating Curve= 0 ,0
Exp/Cntr=0.3,0.1

Type RM Length L Ch R = 1 ,507313.0,1022.4,1022.4,1022.4
BEGIN DESCRIPTION:
Cross Section Contentnea Creek 62.0
END DESCRIPTION:
#Sta/Elev= 30
  4053.4  149.68  4153.4   126.7  4233.4  124.43  4353.4  123.38  4473.4   126.7
  4593.4  126.52  4613.4  127.58  4653.4  126.71  4673.4  123.78  4713.4  120.67
  4753.4  120.34  4813.4  123.43  4933.4  122.71  4965.3  120.98  4972.2   117.1
    4991  115.97  5026.1  116.86  5028.9  117.45  5034.7  121.81  5082.8  125.98
  5262.8  127.33  5402.8  125.78  5442.8   124.4  5542.8     126  5642.8  121.89
  5862.8  126.63  5902.8  128.74  5922.8  128.58  5982.8  132.33  6182.8  149.81
#Mann= 3 , 1 , 0
  4053.4     .15       0  4965.3    .065       0  5034.7     .15       0
Bank Sta=4965.3,5034.7
XS Rating Curve= 0 ,0
Exp/Cntr=0.5,0.3

Type RM Length L Ch R = 1 ,506290.6,45,45,45
BEGIN DESCRIPTION:
Upstream Section of Bridge/Culvert/Weir
END DESCRIPTION:
#Sta/Elev= 30
  3157.4  153.91  3169.2  153.89  3489.2  153.21  3496.7  151.95  3569.2  139.73
  3664.2  129.32  3744.2  125.22  4004.2  124.36    4353  127.16  4662.5  127.84
  4722.3  128.91  4762.6  127.42  4823.7  127.23  4931.1  124.97  4961.1  120.93
    4968  117.05  4986.8  115.92  5021.9  116.81  5024.7   117.4  5030.5  121.76
  5043.2  125.79  5105.9  128.47  5205.9  128.88  5246.6  132.13  5275.1  131.36
  5315.1  133.95  5395.1  135.36  5595.1   143.9  5715.1  147.32  5755.1  150.55
#Mann= 5 , 1 , 0
  3157.4      .2       0  3169.2      .1       0  3496.7     .15       0
  4961.1    .065       0  5030.5     .15       0
#XS Ineff= 2 , 0
       0    4885   132.6    5066       0   136.9
Permanent Ineff=
       F       F
Bank Sta=4961.1,5030.5
XS Rating Curve= 0 ,0
Exp/Cntr=0.5,0.3

Type RM Length L Ch R = 3 ,506268.1,,,
BEGIN DESCRIPTION:
HWY 581
Structure ID: WI_CONCR12
END DESCRIPTION:
Bridge Culvert--1,0,-1,-1, 0
Deck Dist Width WeirC Skew NumUp NumDn MinLoCord MaxHiCord MaxSubmerge Is_Ogee
10,25,2.6,0, 38, 38, , , 0.95, 0, 1,1,,
  3157.4  3489.2  3569.2  3664.2  3668.1  3744.2  4004.2    4091    4353  4406.6
  4662.5  4722.3  4762.6  4823.7  4893.6  4897.2 4898.17 4898.28 4898.39 4898.51
  4898.6 5056.57 5056.68 5056.79  5056.9    5075  5105.9  5155.7  5205.9  5246.6
  5275.1  5315.1  5395.1  5475.1  5535.1  5595.1  5715.1  5755.1
  153.91  153.22  139.74  134.84  134.69  134.34  133.12  132.72  134.29  134.61
  137.04  137.11  137.09  137.01  136.95  136.93  136.96  138.96  138.96  138.96
  138.96  138.92  136.92  136.92  136.91  136.87  137.23  137.34  137.33  137.26
  137.46  137.74   138.3  138.93   140.9  143.91  147.32  150.55
  153.91  153.21  139.73  129.32  129.12  125.22  124.36  125.06  127.16  127.28
  127.84  128.91  127.42  127.23  125.12  125.15  125.15  125.15  125.15  125.16
  134.46  134.42  134.42  134.42  126.38  127.15  128.47  129.18  128.88  132.13
  131.36  133.95  135.36  138.92  140.89   143.9  147.32  150.55
  3157.4  3489.2  3569.2  3664.2  3668.1  3744.2  4004.2    4091    4353  4406.6
  4662.5  4722.3  4762.6  4823.7  4893.6  4897.2 4898.17 4898.28 4898.39 4898.51
  4898.6 5056.57 5056.68 5056.79  5056.9    5075  5105.9  5155.7  5205.9  5246.6
  5275.1  5315.1  5395.1  5475.1  5535.1  5595.1  5715.1  5755.1
  153.91  153.22  139.74  134.84  134.69  134.34  133.12  132.72  134.29  134.61
  137.04  137.11  137.09  137.01  136.95  136.93  136.96  138.96  138.96  138.96
  138.96  138.92  136.92  136.92  136.91  136.87  137.23  137.34  137.33  137.26
  137.46  137.74   138.3  138.93   140.9  143.91  147.32  150.55
  153.81  153.11  139.63  129.22  129.02  125.12  124.26  124.96  127.06  127.18
  127.74  128.81  127.32  127.13  125.02  125.05  125.05  125.05  125.05  125.06
  134.36  134.32  134.32  134.32  126.28  127.05  128.37  129.08  128.78  132.03
  131.26  133.85  135.26  138.82  140.79   143.8  147.22  150.45
Pier Skew, UpSta & Num, DnSta & Num=  ,4938.2, 2 ,4938.2, 2 , 0 , 0 , 0 ,,
     2.5     2.5
  122.67  135.45
     2.5     2.5
  122.57  135.35
Pier Skew, UpSta & Num, DnSta & Num=  ,4977.8, 2 ,4977.8, 2 , 0 , 0 , 0 ,,
     2.5     2.5
  115.64  135.44
     2.5     2.5
  115.54  135.34
Pier Skew, UpSta & Num, DnSta & Num=  ,5017.8, 2 ,5017.8, 2 , 0 , 0 , 0 ,,
     2.5     2.5
  115.64  135.43
     2.5     2.5
  115.54  135.33
Abutment Skew #Up #Dn= , 2 , 2
  4898.4    4917
  134.46  125.29
  4898.4    4917
  134.36  125.19
Abutment Skew #Up #Dn= , 2 , 2
  5043.2 5056.99
  125.79  134.42
  5043.2 5056.99
  125.69  134.32
BR Coef= 1 , 1 , 0 ,1.25, 0 ,,,0.8,0,2,0,
WSPro=,,,, 1 ,,,, 0 ,,,, 0 ,,,,-1 ,-1 ,-1 , 0 , 0 , 0 , 0 , 0
BR U #Sta/Elev= 75
  3157.4  153.91  3169.2  153.89  3489.2  153.21  3496.7  151.95  3569.2  139.73
  3664.2  129.32  3668.1  129.12  3744.2  125.22  4004.2  124.36    4091  125.06
    4353  127.16  4406.6  127.28  4661.9  127.84  4662.5  127.84  4715.6  128.79
  4722.3  128.91  4762.6  127.42  4768.2   127.4  4823.7  127.23  4823.9  127.22
  4880.8  125.51  4893.6  125.12  4896.7  125.14  4897.2  125.15 4898.17  125.15
 4898.28  125.15 4898.39  125.15 4898.51  125.16  4898.6  125.16  4916.9  125.29
    4917  125.29  4931.1  124.97  4938.2  123.81  4952.3  122.23  4961.1  120.93
    4968  117.05  4977.8  116.58    4978  116.81  4986.8  115.92  4995.4  116.13
    5005  116.42  5016.3  116.65  5017.8   116.6  5021.9  116.81  5024.7   117.4
  5030.5  121.76  5043.1  125.76  5043.2  125.79 5056.46  126.36 5056.57  126.36
 5056.68  126.37 5056.79  126.37  5056.9  126.38  5058.7  126.45  5059.1  126.47
    5075  127.15  5105.9  128.47  5107.2  128.49  5155.7  129.18    5156  129.18
  5201.1  128.91  5205.9  128.88  5246.6  132.13  5247.2  132.11  5275.1  131.36
  5315.1  133.95  5395.1  135.36  5475.1  138.92  5535.1  140.89  5549.3   141.6
  5595.1   143.9  5649.3  145.44  5658.3   145.7  5715.1  147.32  5755.1  150.55
BR U #Mann= 5
  3157.4      .2  3169.2      .1  3496.7     .15  4961.1    .065  5030.5     .15
BR U Banks=4961.1,5030.5
BR D #Sta/Elev= 75
  3157.4  153.81  3169.2  153.79  3489.2  153.11  3496.7  151.85  3569.2  139.63
  3664.2  129.22  3668.1  129.02  3744.2  125.12  4004.2  124.26    4091  124.96
    4353  127.06  4406.6  127.18  4661.9  127.74  4662.5  127.74  4715.6  128.69
  4722.3  128.81  4762.6  127.32  4768.2   127.3  4823.7  127.13  4823.9  127.12
  4880.8  125.41  4893.6  125.02  4896.7  125.04  4897.2  125.05 4898.17  125.05
 4898.28  125.05 4898.39  125.05 4898.51  125.06  4898.6  125.06  4916.9  125.19
    4917  125.19  4931.1  124.87  4938.2  123.71  4952.3  122.13  4961.1  120.83
    4968  116.95  4977.8  116.48    4978  116.71  4986.8  115.82  4995.4  116.03
    5005  116.32  5016.3  116.55  5017.8   116.5  5021.9  116.71  5024.7   117.3
  5030.5  121.66  5043.1  125.66  5043.2  125.69 5056.46  126.26 5056.57  126.26
 5056.68  126.27 5056.79  126.27  5056.9  126.28  5058.7  126.35  5059.1  126.37
    5075  127.05  5105.9  128.37  5107.2  128.39  5155.7  129.08    5156  129.08
  5201.1  128.81  5205.9  128.78  5246.6  132.03  5247.2  132.01  5275.1  131.26
  5315.1  133.85  5395.1  135.26  5475.1  138.82  5535.1  140.79  5549.3   141.5
  5595.1   143.8  5649.3  145.34  5658.3   145.6  5715.1  147.22  5755.1  150.45
BR D #Mann= 5
  3157.4      .2  3169.2      .1  3496.7     .15  4961.1    .065  5030.5     .15
BR D Banks=4961.1,5030.5
BC Design=,, 0 ,, 0 ,,,,,,
BC HTab HWMax=153.91
BC Use User HTab Curves=0
BC User HTab FreeFlow(D)= 0

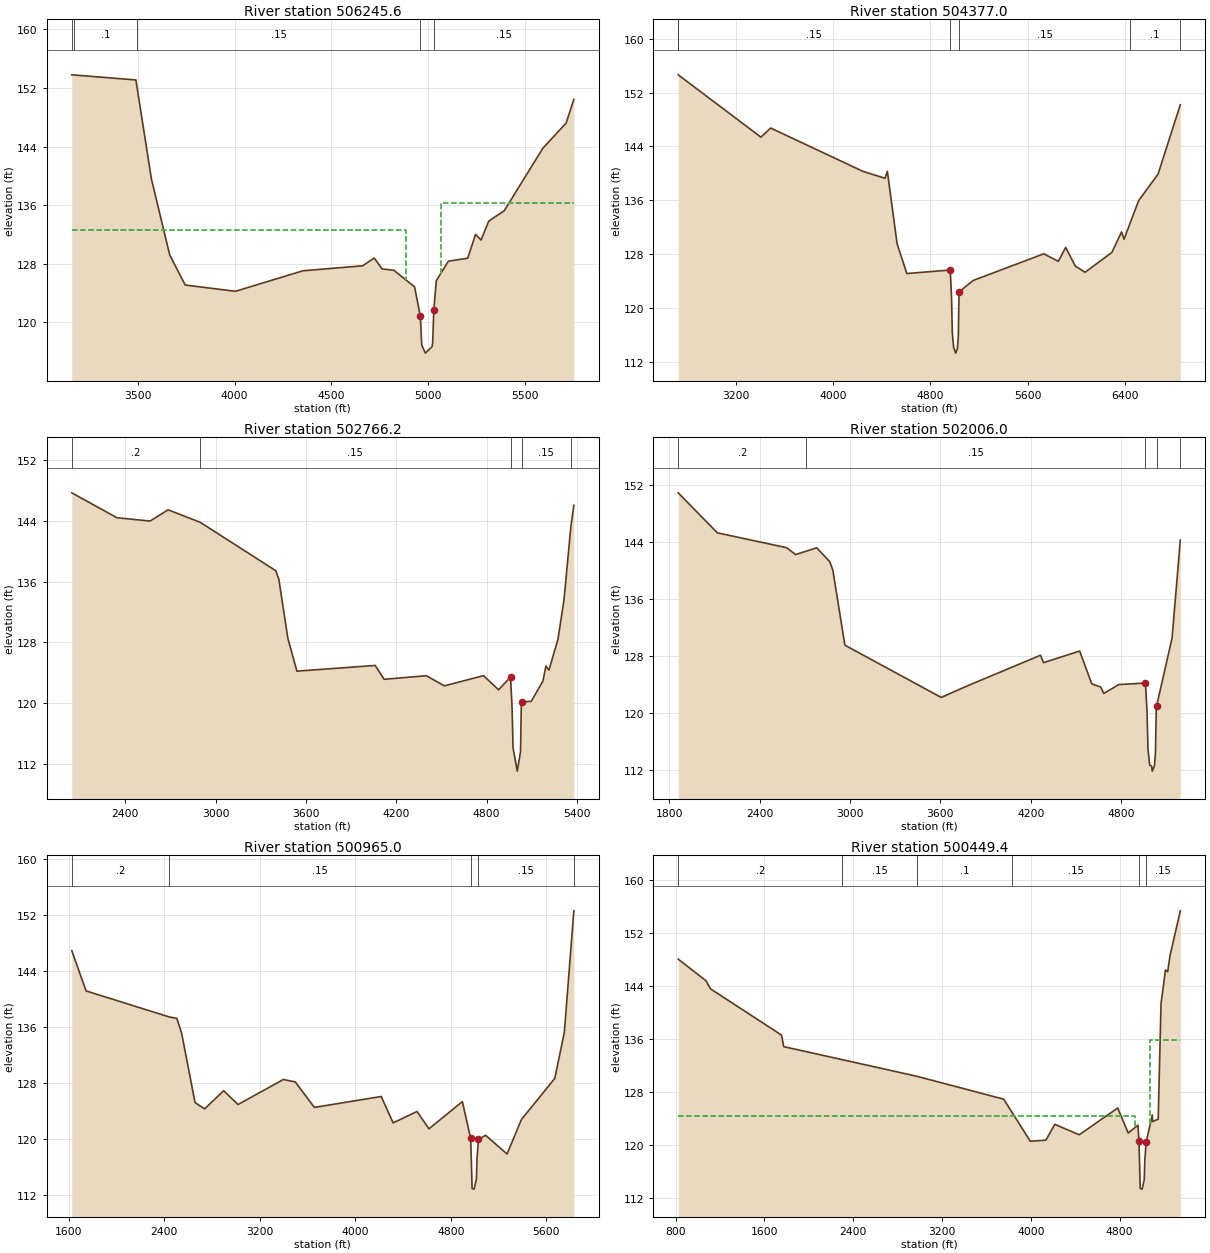
Type RM Length L Ch R = 1 ,506245.6,1868.6,1868.6,1868.6
BEGIN DESCRIPTION:
Downstream Section of Bridge/Culvert/Weir
END DESCRIPTION:
#Sta/Elev= 30
  3157.4   153.8  3169.2  153.78  3489.2   153.1  3496.7  151.84  3569.2  139.62
  3664.2  129.21  3744.2  125.11  4004.2  124.25    4353  127.05  4662.5  127.73
  4722.3   128.8  4762.6  127.31  4823.7  127.12  4931.1  124.86  4961.1  120.82
    4968  116.94  4986.8  115.81  5021.9   116.7  5024.7  117.29  5030.5  121.65
  5043.2  125.68  5105.9  128.36  5205.9  128.77  5246.6  132.02  5275.1  131.25
  5315.1  133.84  5395.1  135.25  5595.1  143.79  5715.1  147.21  5755.1  150.44
#Mann= 5 , 1 , 0
  3157.4      .2       0  3169.2      .1       0  3496.7     .15       0
  4961.1    .065       0  5030.5     .15       0
#XS Ineff= 2 , 0
       0    4885   132.6    5066       0   136.3
Permanent Ineff=
       F       F
Bank Sta=4961.1,5030.5
XS Rating Curve= 0 ,0
Exp/Cntr=0.5,0.3

Type RM Length L Ch R = 1 ,504377.0,1610.8,1610.8,1610.8
BEGIN DESCRIPTION:
Cross Section Contentnea Creek 60.0
END DESCRIPTION:
#Sta/Elev= 30
    2726  154.64    3406  145.38    3486  146.73  4245.8  140.29  4425.8  139.27
  4445.8   140.3  4525.8  129.54  4605.8  125.11 4963.05  125.63 4973.45  121.59
 4979.85  116.34 4990.95  114.13 5007.85  113.28 5022.25  113.98 5029.55  115.85
 5034.25  121.59 5036.95   122.4    5152  124.08    5732  128.04    5852  126.92
    5912  128.99    5992   126.2    6072   125.3    6292  128.24    6372   131.3
    6392   130.2    6441  132.54    6512  135.93    6672  139.89  6854.9  150.19
#Mann= 6 , 1 , 0
    2726      .2       0    2726     .15       0 4963.05    .065       0
 5036.95     .15       0    6441      .1       0  6854.9      .2       0
Bank Sta=4963.05,5036.95
XS Rating Curve= 0 ,0
Exp/Cntr=0.3,0.1

Type RM Length L Ch R = 1 ,502766.2,760.2,760.2,760.2
BEGIN DESCRIPTION:
Cross Section WI_CCX156
Located At: WI_CCX156
END DESCRIPTION:
#Sta/Elev= 30
  2043.9  147.65  2343.9  144.38  2563.9  143.94  2683.9  145.42  2897.3  143.78
  3399.7  137.42  3419.7  136.31  3479.7  128.55  3539.7  124.23  4059.7  124.98
  4119.7  123.16  4399.7  123.63  4519.7   122.3  4779.7  123.64  4879.7  121.78
  4959.2  123.45  4969.6  119.41    4976  114.16    5004   111.1  5025.7  113.67
  5030.4  119.41  5033.1  120.22  5096.5  120.26  5174.4  122.92  5194.4  124.91
  5214.4  124.36  5274.4  128.42  5314.4  133.59  5360.3  143.25  5379.9     146
#Mann= 5 , 1 , 0
  2043.9      .2       0  2897.3     .15       0  4959.2    .065       0
  5033.1     .15       0  5360.3      .2       0
Bank Sta=4959.2,5033.1
XS Rating Curve= 0 ,0
Exp/Cntr=0.3,0.1

Type RM Length L Ch R = 1 ,502006.0,1041,1041,1041
BEGIN DESCRIPTION:
Cross Section Contentnea Creek 59.0
END DESCRIPTION:
#Sta/Elev= 30
  1858.6  150.84  2118.6  145.23  2578.6  143.15  2638.6  142.18  2710.4  142.67
  2778.6  143.14  2865.9  141.17  2885.9     140  2965.9  129.48  3605.9  122.15
  3785.9  123.83  4265.9  128.07  4285.9  127.03  4525.9  128.66  4605.9  124.06
  4665.9   123.6  4685.9  122.71  4785.9  123.96 4963.05  124.17 4973.45  120.13
 4979.85  114.88 4990.95  112.67 5004.35  112.52 5007.85  111.82 5022.25  112.52
 5029.55  114.39 5034.25  120.13 5036.95  120.94    5140  130.51  5194.5  144.21
#Mann= 5 , 1 , 0
  1858.6      .2       0  2710.4     .15       0 4963.05    .065       0
 5036.95     .15       0  5194.5      .2       0
Bank Sta=4963.05,5036.95
XS Rating Curve= 0 ,0
Exp/Cntr=0.3,0.1

Type RM Length L Ch R = 1 ,500965.0,515.6,515.6,515.6
BEGIN DESCRIPTION:
Cross Section Contentnea Creek 58.0
END DESCRIPTION:
#Sta/Elev= 30
  1624.6   146.9  1744.6  141.14  2441.8  137.42  2504.6  137.22  2544.6  135.15
  2657.6  125.18  2737.6  124.28  2897.6  126.88  3017.6   124.9  3397.6  128.48
  3497.6  128.13  3657.6  124.49  4217.6  126.05  4317.6  122.28  4517.6  123.91
  4617.6  121.43  4897.6  125.32 4967.45  120.05 4979.25  112.91 4996.05  112.81
 5015.25  114.24 5020.55  117.25 5032.55  119.91  5092.1  120.51  5272.1  117.83
  5392.1  122.75  5672.1  128.64  5752.1  135.22  5831.6  152.57  5831.7  152.59
#Mann= 5 , 1 , 0
  1624.6      .2       0  2441.8     .15       0 4967.45    .065       0
 5032.55     .15       0  5831.6      .2       0
Bank Sta=4967.45,5032.55
XS Rating Curve= 0 ,0
Exp/Cntr=0.5,0.3

Type RM Length L Ch R = 1 ,500449.4,55,55,55
BEGIN DESCRIPTION:
Upstream Section of Bridge/Culvert/Weir
END DESCRIPTION:
#Sta/Elev= 30
   823.1  148.04  1073.6  144.77  1113.6  143.56  1753.6  136.57  1773.6  134.82
  2302.8  132.85  2971.7  130.35  3754.9  126.89  3830.5  124.89  3994.9  120.53
  4135.5   120.7  4215.5  123.09  4435.5  121.51  4782.4  125.55  4876.8  121.78
  4964.6  122.96  4973.6  120.54  4985.4   113.4  5002.2   113.3  5021.4  114.73
  5026.7  117.74  5038.7   120.4  5093.9  124.51    5097  123.51    5147  123.86
  5172.5  141.31  5212.5   146.4  5232.5  146.14  5252.5  148.49  5346.2  155.34
#Mann= 6 , 1 , 0
   823.1      .2       0  2302.8     .15       0  2971.7      .1       0
  3830.5     .15       0  4973.6    .065       0  5038.7     .15       0
#XS Ineff= 2 , 0
       0    4940   124.3    5075       0   135.8
Permanent Ineff=
       F       F
Bank Sta=4973.6,5038.7
XS Rating Curve= 0 ,0
Exp/Cntr=0.5,0.3

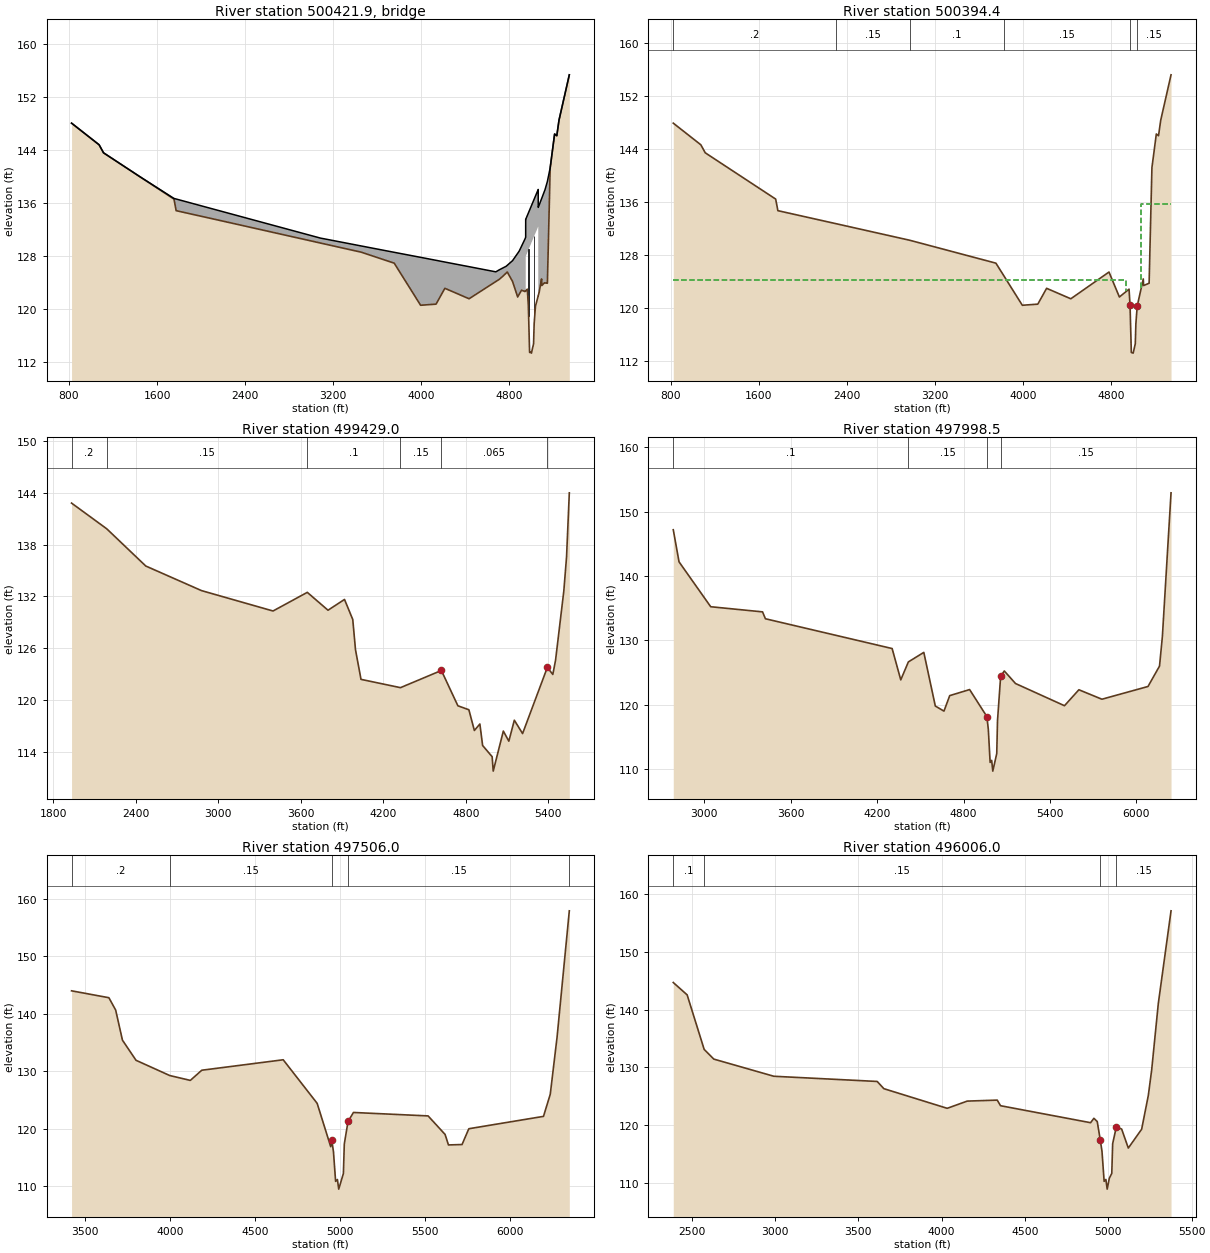
Type RM Length L Ch R = 3 ,500421.9,,,
BEGIN DESCRIPTION:
SADIE RD (SR 1144)
Structure ID: WI_CONCR11
END DESCRIPTION:
Bridge Culvert--1,0,-1,-1, 0
Deck Dist Width WeirC Skew NumUp NumDn MinLoCord MaxHiCord MaxSubmerge Is_Ogee
10,35,2.6,0, 43, 43, , , 0.95, 0, 1,1,,
   823.1  1073.6  1113.6  1434.8  1753.6  1773.6    3084  3454.9  3754.9  3994.9
  4135.5  4215.5  4435.5  4678.3  4710.3  4772.2  4782.4  4830.3  4876.8  4890.6
  4912.3  4942.9 4949.57 4949.68 4949.79 4949.91    4950 5063.49  5063.6 5063.71
 5063.79  5063.9  5072.6  5093.9    5097  5119.6  5125.2    5147  5172.5  5212.5
  5232.5  5252.5  5346.2
  148.05  144.78  143.57  140.06  136.68  136.59  130.69   129.5  128.54  127.78
  127.33  127.07  126.37  125.59   125.9  126.43  126.58  127.28  128.39  128.72
  129.47  130.54  130.81  133.51  133.51  133.51  133.52  138.03  138.03  135.33
  135.33  135.34   135.7  136.63  136.76  137.75  137.99  139.25  141.32  146.41
  146.15   148.5  155.35
  148.05  144.78  143.57  140.06  136.58  134.83  129.94  128.56   126.9  120.54
  120.71   123.1  121.52  124.12  124.46   125.4  125.56  124.13  121.79  122.19
  122.82  122.61  122.72  122.72  122.72  122.73  127.92  132.43  132.43  132.43
  132.43  121.99  122.53  124.52  123.52  123.93  123.92  123.87  141.32  146.41
  146.15   148.5  155.35
   823.1  1073.6  1113.6  1434.8  1753.6  1773.6    3084  3454.9  3754.9  3994.9
  4135.5  4215.5  4435.5  4678.3  4710.3  4772.2  4782.4  4830.3  4876.8  4890.6
  4912.3  4942.9 4949.57 4949.68 4949.79 4949.91    4950 5063.49  5063.6 5063.71
 5063.79  5063.9  5072.6  5093.9    5097  5119.6  5125.2    5147  5172.5  5212.5
  5232.5  5252.5  5346.2
  147.95  144.69  143.48  139.97  136.68  136.59  130.69   129.5  128.54  127.78
  127.33  127.07  126.37  125.59   125.9  126.43  126.58  127.28  128.39  128.72
  129.47  130.54  130.81  133.51  133.51  133.51  133.52  138.03  138.03  135.33
  135.33  135.34   135.7  136.63  136.76  137.75  137.99  139.25  141.23  146.32
  146.06  148.41  155.25
  147.95  144.68  143.47  139.96  136.48  134.73  129.84  128.46   126.8  120.44
  120.61     123  121.42  124.02  124.36   125.3  125.46  124.03  121.69  122.09
  122.72  122.51  122.62  122.62  122.62  122.63  127.82  132.33  132.33  132.33
  132.33  121.89  122.43  124.42  123.42  123.83  123.82  123.77  141.22  146.31
  146.05   148.4  155.25
Pier Skew, UpSta & Num, DnSta & Num=  ,4976.4, 2 ,4976.4, 2 , 0 , 0 , 0 ,,
     2.6     2.6
  117.16  130.02
     2.6     2.6
  117.06  129.92
Pier Skew, UpSta & Num, DnSta & Num=  ,5026.7, 2 ,5026.7, 2 , 0 , 0 , 0 ,,
     2.6     2.6
  116.01  132.02
     2.6     2.6
  115.91  131.92
Abutment Skew #Up #Dn= , 2 , 2
  4949.8  4964.7
  127.92  122.94
  4949.8  4964.7
  127.82  122.84
Abutment Skew #Up #Dn= , 2 , 2
  5021.4 5063.99
  114.74  132.43
  5021.4 5063.99
  114.64  132.33
BR Coef= 1 , 1 , 0 ,1.25, 0 ,,,0.8,0,2,0,
WSPro=,,,, 1 ,,,, 0 ,,,, 0 ,,,,-1 ,-1 ,-1 , 0 , 0 , 0 , 0 , 0
BR U #Sta/Elev= 73
   823.1  148.05  1043.1  145.18  1073.6  144.78  1113.6  143.57  1414.8  140.28
  1434.8  140.06  1753.6  136.58  1773.6  134.83  2302.8  132.86  2971.7  130.36
    3084  129.94  3454.9  128.56  3754.9   126.9  3830.5   124.9  3994.9  120.54
  4135.5  120.71  4215.5   123.1  4435.5  121.52  4678.3  124.12  4710.3  124.46
  4719.2  124.59  4746.2  124.98  4772.2   125.4  4782.4  125.56  4830.3  124.13
  4831.5  124.07  4876.8  121.79  4890.6  122.19  4912.3  122.82  4942.9  122.61
  4947.9  122.69  4948.6   122.7 4949.57  122.72 4949.68  122.72 4949.79  122.72
 4949.91  122.73    4950  122.73  4964.6  122.97  4964.7  122.94  4973.6  120.55
  4976.4  118.98  4983.9  114.25  4985.4  113.41  4996.2  113.43  5002.2  113.31
  5012.8  114.14  5016.2  114.34  5021.3  114.73  5021.4  114.74  5026.7  117.75
  5038.7  120.41 5063.49  121.96  5063.6  121.97 5063.71  121.97 5063.79  121.98
  5063.9  121.99  5065.9  122.11  5066.2  122.13  5072.6  122.53  5093.9  124.52
    5097  123.52  5119.6  123.93  5125.2  123.92  5145.7  123.87    5147  123.87
  5172.5  141.32  5182.9  142.64  5212.5  146.41  5232.5  146.15  5241.4   147.2
  5252.5   148.5  5298.7  151.88  5346.2  155.35
BR U #Mann= 6
   823.1      .2  2302.8     .15  2971.7      .1  3830.5     .15  4973.6    .065
  5038.7     .15
BR U Banks=4973.6,5038.7
BR D #Sta/Elev= 73
   823.1  147.95  1043.1  145.08  1073.6  144.68  1113.6  143.47  1414.8  140.18
  1434.8  139.96  1753.6  136.48  1773.6  134.73  2302.8  132.76  2971.7  130.26
    3084  129.84  3454.9  128.46  3754.9   126.8  3830.5   124.8  3994.9  120.44
  4135.5  120.61  4215.5     123  4435.5  121.42  4678.3  124.02  4710.3  124.36
  4719.2  124.49  4746.2  124.88  4772.2   125.3  4782.4  125.46  4830.3  124.03
  4831.5  123.97  4876.8  121.69  4890.6  122.09  4912.3  122.72  4942.9  122.51
  4947.9  122.59  4948.6   122.6 4949.57  122.62 4949.68  122.62 4949.79  122.62
 4949.91  122.63    4950  122.63  4964.6  122.87  4964.7  122.84  4973.6  120.45
  4976.4  118.88  4983.9  114.15  4985.4  113.31  4996.2  113.33  5002.2  113.21
  5012.8  114.04  5016.2  114.24  5021.3  114.63  5021.4  114.64  5026.7  117.65
  5038.7  120.31 5063.49  121.86  5063.6  121.87 5063.71  121.87 5063.79  121.88
  5063.9  121.89  5065.9  122.01  5066.2  122.03  5072.6  122.43  5093.9  124.42
    5097  123.42  5119.6  123.83  5125.2  123.82  5145.7  123.77    5147  123.77
  5172.5  141.22  5182.9  142.54  5212.5  146.31  5232.5  146.05  5241.4   147.1
  5252.5   148.4  5298.7  151.78  5346.2  155.25
BR D #Mann= 6
   823.1      .2  2302.8     .15  2971.7      .1  3830.5     .15  4973.6    .065
  5038.7     .15
BR D Banks=4973.6,5038.7
BC Design=,, 0 ,, 0 ,,,,,,
BC HTab HWMax=155.34
BC Use User HTab Curves=0
BC User HTab FreeFlow(D)= 0

Type RM Length L Ch R = 1 ,500394.4,965.4,965.4,965.4
BEGIN DESCRIPTION:
Downstream Section of Bridge/Culvert/Weir
END DESCRIPTION:
#Sta/Elev= 30
   823.1  147.94  1073.6  144.67  1113.6  143.46  1753.6  136.47  1773.6  134.72
  2302.8  132.75  2971.7  130.25  3754.9  126.79  3830.5  124.79  3994.9  120.43
  4135.5   120.6  4215.5  122.99  4435.5  121.41  4782.4  125.45  4876.8  121.68
  4964.6  122.86  4973.6  120.44  4985.4   113.3  5002.2   113.2  5021.4  114.63
  5026.7  117.64  5038.7   120.3  5093.9  124.41    5097  123.41    5147  123.76
  5172.5  141.21  5212.5   146.3  5232.5  146.04  5252.5  148.39  5346.2  155.24
#Mann= 6 , 1 , 0
   823.1      .2       0  2302.8     .15       0  2971.7      .1       0
  3830.5     .15       0  4973.6    .065       0  5038.7     .15       0
#XS Ineff= 2 , 0
       0    4940   124.3    5075       0   135.8
Permanent Ineff=
       F       F
Bank Sta=4973.6,5038.7
XS Rating Curve= 0 ,0
Exp/Cntr=0.5,0.3

Type RM Length L Ch R = 1 ,499429.0,1430.5,1430.5,1430.5
BEGIN DESCRIPTION:
Cross Section Contentnea Creek 57.0
END DESCRIPTION:
#Sta/Elev= 30
  1932.3  142.82  2188.5  139.84  2472.3  135.53  2878.1  132.68  3398.1  130.32
  3647.3  132.48  3798.1  130.41  3918.1  131.66  3978.1  129.34  3998.1  125.83
  4038.1   122.4  4325.3  121.44  4622.9  123.43  4742.9  119.34  4822.9  118.88
  4862.9  116.48  4902.9  117.23  4922.9  114.74  4992.2  113.44    5000  111.77
  5073.6  116.41  5113.6  115.24  5153.6  117.67  5213.6  116.12  5393.6  123.78
  5433.6  122.97  5453.6  124.63  5513.6  132.64  5533.6  136.61  5553.6  144.01
#Mann= 6 , 1 , 0
  1932.3      .2       0  2188.5     .15       0  3647.3      .1       0
  4325.3     .15       0  4622.9    .065       0  5393.6     .15       0
Bank Sta=4622.9,5393.6
XS Rating Curve= 0 ,0
Exp/Cntr=0.3,0.1

Type RM Length L Ch R = 1 ,497998.5,492.5,492.5,492.5
BEGIN DESCRIPTION:
Cross Section CCX_W155
Located At: CCX_W155 CNTRL
END DESCRIPTION:
#Sta/Elev= 30
  2784.2   147.2  2824.2  142.21  3044.2  135.23  3404.2  134.43  3424.2  133.36
  4304.2  128.73  4364.2  123.86    4417  126.65  4524.2  128.13  4604.2  119.79
  4664.2     119  4704.2  121.41  4842.4  122.35    4962  118.16  4972.2   116.2
  4984.9  111.02  4995.5  111.34  5003.3  109.67  5030.8   112.4  5036.1  117.52
    5058  124.44  5083.2  125.24  5161.3  123.29  5501.3  119.84  5601.3  122.32
  5761.3  120.85  6081.3  122.83  6161.3     126  6181.3  130.63  6241.3  152.94
#Mann= 4 , 1 , 0
  2784.2      .1       0    4417     .15       0    4962    .065       0
    5058     .15       0
Bank Sta=4962,5058
XS Rating Curve= 0 ,0
Exp/Cntr=0.3,0.1

Type RM Length L Ch R = 1 ,497506.0,1500,1500,1500
BEGIN DESCRIPTION:
Cross Section Contentnea Creek 56.0
END DESCRIPTION:
#Sta/Elev= 30
  3418.7     144  3638.7   142.8  3678.7  140.65  3718.7  135.41  3798.7  131.91
  3997.2  129.26  4118.7  128.41  4186.1  130.18  4666.1     132  4866.1  124.42
  4946.1  116.87    4952  117.98  4962.2  116.02  4974.9  110.84  4985.5  111.16
  4993.3  109.49  5020.8  112.22  5026.1  117.34    5048  121.26    5080  122.83
    5520  122.23    5620  119.01    5640  117.18    5720  117.25    5760     120
    6200  122.15    6240  126.01    6280  135.93  6352.1  157.89  6352.2  157.92
#Mann= 5 , 1 , 0
  3418.7      .2       0  3997.2     .15       0    4952    .065       0
    5048     .15       0  6352.1      .2       0
Bank Sta=4952,5048
XS Rating Curve= 0 ,0
Exp/Cntr=0.3,0.1

Type RM Length L Ch R = 1 ,496006.0,1500,1500,1500
BEGIN DESCRIPTION:
Cross Section Contentnea Creek 55.0
END DESCRIPTION:
#Sta/Elev= 30
  2390.4  144.71  2473.6  142.57  2575.7  133.13  2633.6  131.45  2993.6  128.48
  3613.6  127.58  3653.6  126.33  4033.6  122.93  4153.6  124.18  4333.6  124.35
  4353.6  123.38  4893.6  120.44  4913.6   121.2  4933.6  120.64    4952  117.43
  4962.2  115.47  4974.9  110.29  4985.5  110.61  4993.3  108.94  5006.1  110.83
  5020.8  111.67  5026.1  116.79    5048  119.71    5080  119.34    5120  116.05
    5200  119.31    5240  125.16    5260  129.54    5300  141.09  5376.3  157.12
#Mann= 4 , 1 , 0
  2390.4      .1       0  2575.7     .15       0    4952    .065       0
    5048     .15       0
Bank Sta=4952,5048
XS Rating Curve= 0 ,0
Exp/Cntr=0.3,0.1