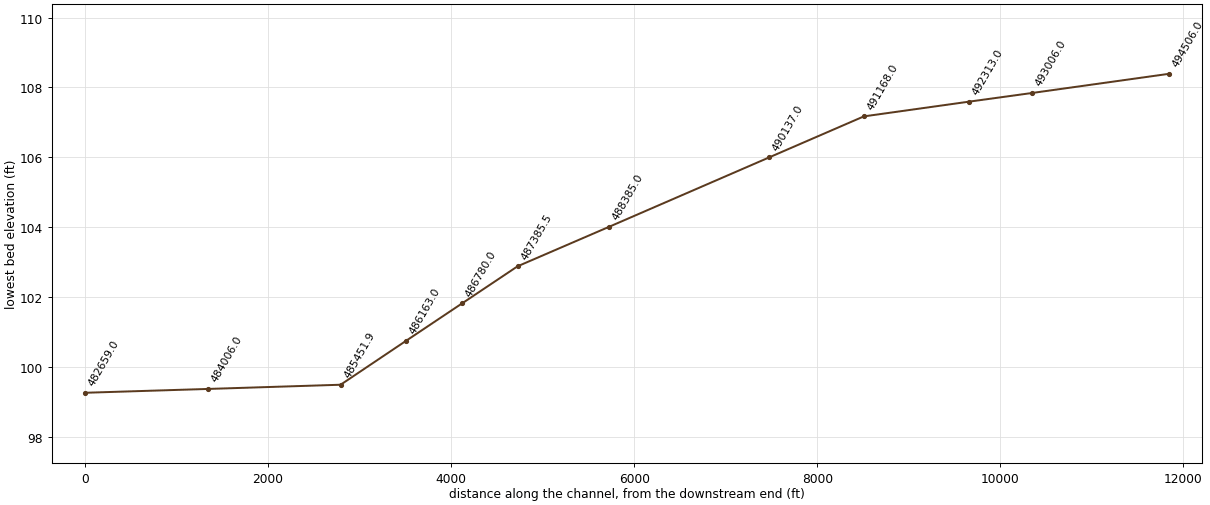
HEC-RAS study CONTENTNEA_FINAL.PRJ: Contentnea

--- CONTENTNEA_FINAL.g01 (geometry) --- (continued)

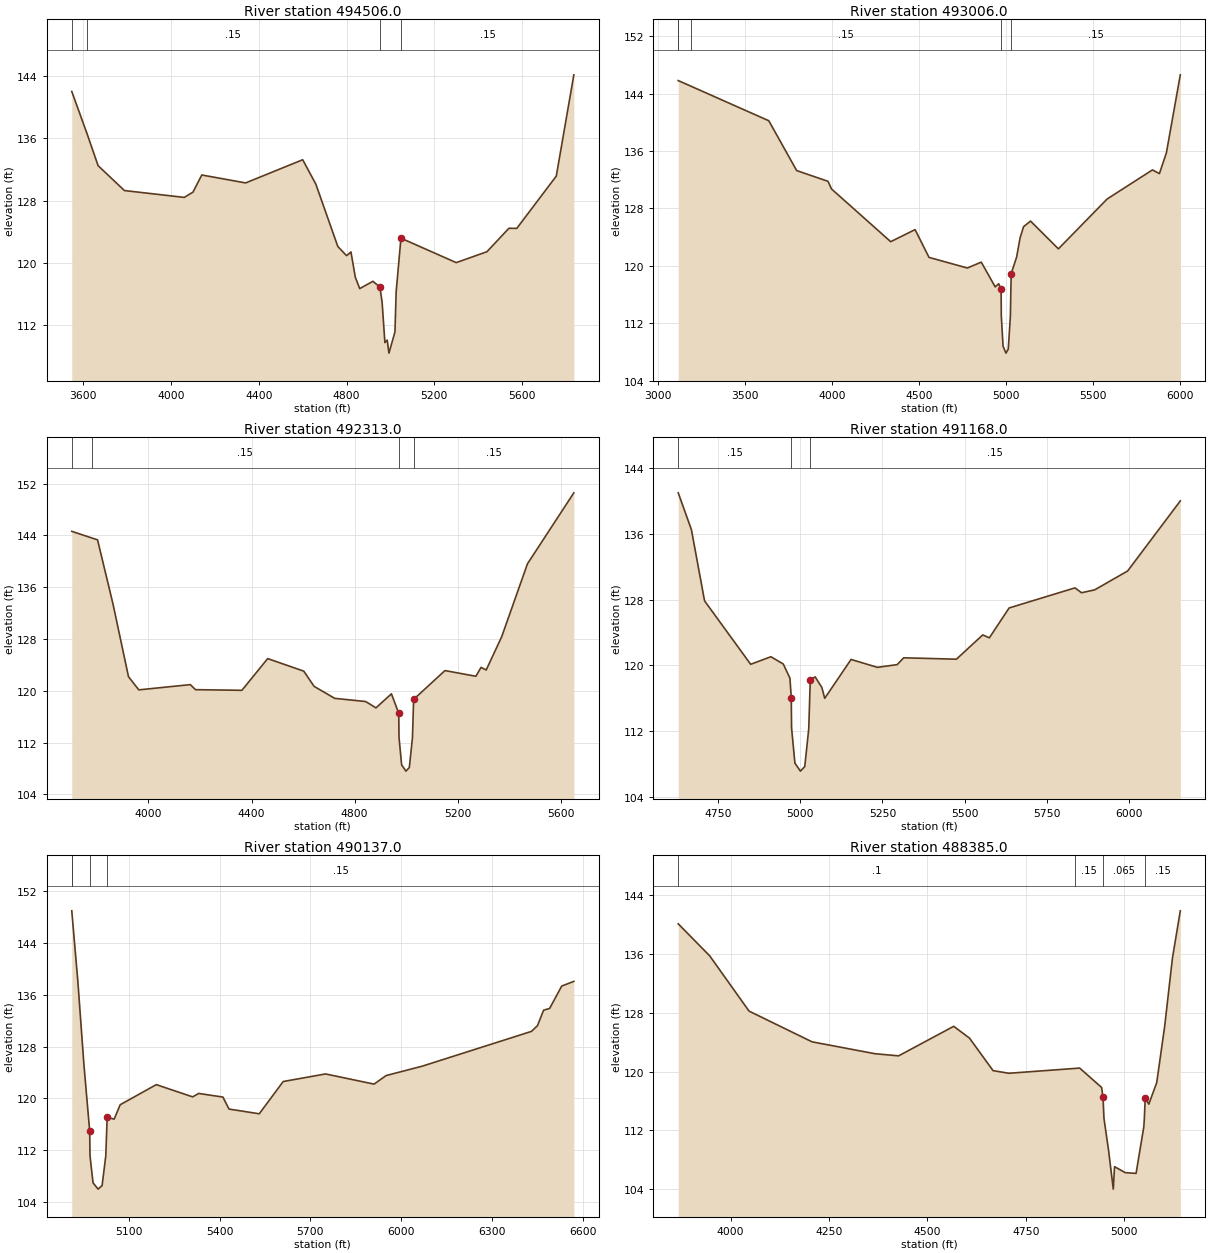
Type RM Length L Ch R = 1 ,494506.0,1500,1500,1500
BEGIN DESCRIPTION:
Cross Section Contentnea Creek 54.0
END DESCRIPTION:
#Sta/Elev= 30
  3547.6  142.01  3616.1  136.68  3667.6  132.48  3787.6  129.28  4060.2   128.4
  4100.2  129.08  4140.2  131.28  4340.2  130.26  4600.2  133.24  4660.2   130.1
  4760.2   122.1  4800.2  120.91  4820.2  121.39  4840.2  118.12  4860.2  116.68
  4920.2  117.62    4952  116.88  4962.2  114.92  4974.9  109.74  4985.5  110.06
  4993.3  108.39  5020.8  111.12  5026.1  116.24    5048  123.16    5300  120.02
    5440  121.42    5540  124.43  5576.1  124.42  5756.1  131.14  5836.1  144.15
#Mann= 4 , 1 , 0
  3547.6      .1       0  3616.1     .15       0    4952    .065       0
    5048     .15       0
Bank Sta=4952,5048
XS Rating Curve= 0 ,0
Exp/Cntr=0.3,0.1

Type RM Length L Ch R = 1 ,493006.0,693,693,693
BEGIN DESCRIPTION:
Cross Section Contentnea Creek 53.0
END DESCRIPTION:
#Sta/Elev= 30
  3117.1  145.82  3188.6  145.05  3637.1  140.22  3797.1  133.28  3977.1  131.78
  3997.1  130.72  4337.1  123.37  4477.1  125.05  4557.1  121.18  4777.1   119.7
  4857.1  120.52  4937.1  117.07  4957.1  117.51 4971.15  116.76 4972.05  113.09
 4982.25  108.81 4998.95  107.84 5012.15   108.4 5024.25  112.98 5028.85  118.92
    5060  121.21    5080   123.9    5100  125.46    5140  126.24    5300  122.37
    5580  129.32    5840  133.37    5880  132.86    5920  135.74    6000  146.62
#Mann= 5 , 1 , 0
  3117.1      .2       0  3117.1      .1       0  3188.6     .15       0
 4971.15    .065       0 5028.85     .15       0
Bank Sta=4971.15,5028.85
XS Rating Curve= 0 ,0
Exp/Cntr=0.3,0.1

Type RM Length L Ch R = 1 ,492313.0,1145,1145,1145
BEGIN DESCRIPTION:
Cross Section Contentnea Creek 52.0
END DESCRIPTION:
#Sta/Elev= 30
  3702.7  144.62  3779.6  143.61  3802.7  143.31  3862.7  133.39  3922.7  122.18
  3962.7  120.14  4162.7  120.95  4182.7  120.17  4362.7  120.07  4462.7  124.97
  4602.7  123.03  4642.7  120.68  4722.7  118.83  4842.7  118.34  4882.7  117.36
  4942.7  119.53 4971.15  116.51 4972.05  112.84 4982.25  108.56 4998.95  107.59
 5012.15  108.15 5024.25  112.73 5028.85  118.67  5150.3  123.12  5270.3  122.24
  5290.3  123.61  5310.3  123.21  5370.3  128.33  5470.3   139.6  5650.3  150.57
#Mann= 4 , 1 , 0
  3702.7      .1       0  3779.6     .15       0 4971.15    .065       0
 5028.85     .15       0
Bank Sta=4971.15,5028.85
XS Rating Curve= 0 ,0
Exp/Cntr=0.3,0.1

Type RM Length L Ch R = 1 ,491168.0,1031,1031,1031
BEGIN DESCRIPTION:
Cross Section CCX_W154
Located At: CCX_W154 CNTL
END DESCRIPTION:
#Sta/Elev= 30
  4629.7  140.96  4669.7  136.49  4709.7  127.84  4849.7  120.14  4911.2  121.06
  4948.8  120.17    4969  118.45    4973  116.09  4973.9  112.42  4984.1  108.14
  5000.8  107.17    5014  107.73  5026.1  112.31  5030.7  118.25  5045.5  118.61
  5065.8  117.34  5074.6  116.01  5154.6  120.73  5234.6  119.77  5294.6   120.1
  5314.6  120.93  5474.6  120.76  5554.6  123.71  5574.6  123.35  5634.6  126.98
  5834.6  129.42  5854.6  128.83  5894.6  129.18  5994.6  131.47  6154.6  139.98
#Mann= 3 , 1 , 0
  4629.7     .15       0    4973    .065       0  5030.7     .15       0
Bank Sta=4973,5030.7
XS Rating Curve= 0 ,0
Exp/Cntr=0.3,0.1

Type RM Length L Ch R = 1 ,490137.0,1752,1752,1752
BEGIN DESCRIPTION:
Cross Section Contentnea Creek 51.0
END DESCRIPTION:
#Sta/Elev= 30
  4911.9  148.96  4931.9  138.14  4951.9   125.3 4971.15  114.92 4972.05  111.25
 4975.25  109.82 4982.25  106.97 4998.95     106 5012.15  106.56 5024.25  111.14
 5028.85  117.08  5051.9  116.81  5071.9  119.03  5191.2  122.13  5311.2  120.24
  5331.2  120.77  5411.2  120.21  5431.2  118.36  5531.2  117.63  5610.3  122.61
  5750.3  123.78  5910.3  122.21  5950.3  123.53  6070.3  124.99  6430.3  130.35
  6450.3  131.24  6470.3  133.62  6490.3  133.89  6530.3  137.35  6570.3  138.07
#Mann= 4 , 1 , 0
  4911.9      .2       0  4911.9     .15       0 4971.15    .065       0
 5028.85     .15       0
Bank Sta=4971.15,5028.85
XS Rating Curve= 0 ,0
Exp/Cntr=0.3,0.1

Type RM Length L Ch R = 1 ,488385.0,999.5,999.5,999.5
BEGIN DESCRIPTION:
Cross Section Contentnea Creek 50.0
END DESCRIPTION:
#Sta/Elev= 28
    3867  140.12    3947  135.76    4047  128.24    4207  124.06    4367  122.44
    4427  122.15    4567  126.17    4607  124.57    4667  120.14    4707  119.78
  4875.5  120.44    4887  120.49  4942.8  117.85  4946.4  116.54  4948.8  113.64
  4960.5  109.29  4972.5  104.01  4975.7  107.07  5002.6  106.26  5030.4  106.15
    5050  112.46  5051.3   113.5  5053.6  116.42  5062.8  115.58  5082.8  118.49
  5102.8  126.05  5122.8  135.45  5142.8  141.89
#Mann= 4 , 1 , 0
    3867      .1       0  4875.5     .15       0  4946.4    .065       0
  5053.6     .15       0
Bank Sta=4946.4,5053.6
XS Rating Curve= 0 ,0
Exp/Cntr=0.3,0.1

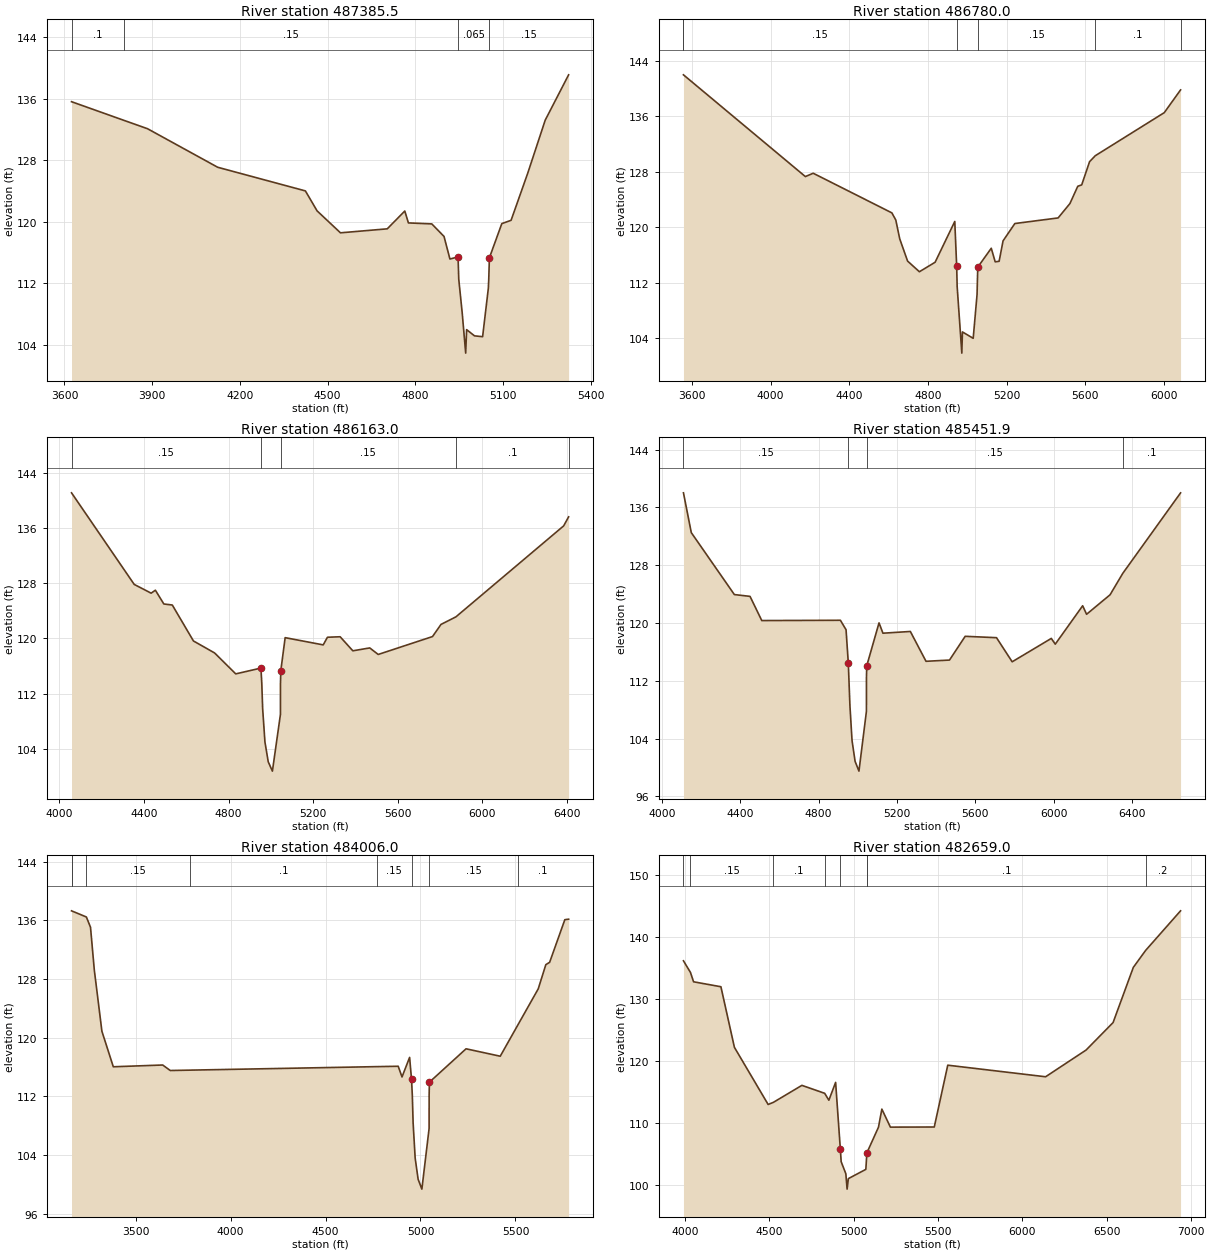
Type RM Length L Ch R = 1 ,487385.5,605.5,605.5,605.5
BEGIN DESCRIPTION:
Cross Section CCX_W153
Located At: CCX_W153 CNTL
END DESCRIPTION:
#Sta/Elev= 28
  3624.2  135.63  3803.5   133.2  3884.2  132.11  4124.2  127.09  4424.2  124.01
  4464.2  121.41  4544.2  118.55  4704.2  119.07  4764.2  121.39  4776.6  119.84
  4856.6  119.71  4898.4  118.08  4918.6  115.14  4946.4  115.41  4948.8  112.51
  4960.5  108.16  4972.5  102.88  4975.7  105.94  5002.6  105.13  5030.4  105.02
    5050  111.33  5051.3  112.37  5053.6  115.29  5096.1  119.75  5127.8  120.18
  5184.6   126.3  5244.6  133.23  5324.6  139.13
#Mann= 4 , 1 , 0
  3624.2      .1       0  3803.5     .15       0  4946.4    .065       0
  5053.6     .15       0
Bank Sta=4946.4,5053.6
XS Rating Curve= 0 ,0
Exp/Cntr=0.3,0.1

Type RM Length L Ch R = 1 ,486780.0,617,617,617
BEGIN DESCRIPTION:
Cross Section Contentnea Creek 49.0
END DESCRIPTION:
#Sta/Elev= 30
  3556.7     142  4176.7  127.31  4216.7  127.79  4616.7  122.07  4636.7  121.04
  4656.7  118.32  4696.7  115.11  4756.7  113.57  4836.7  114.94  4936.7  120.83
  4946.4  114.35  4948.8  111.45  4972.5  101.82  4975.7  104.88  5030.4  103.96
    5050  110.27  5053.6  114.23  5122.3  116.96  5142.3     115  5162.3  115.08
  5182.3  118.03  5242.3  120.53  5462.3  121.34  5522.3  123.41  5562.3  125.91
  5582.3  126.11  5622.3  129.46  5651.3  130.32  6002.3  136.54  6085.1  139.82
#Mann= 6 , 1 , 0
  3556.7      .2       0  3556.7     .15       0  4946.4    .065       0
  5053.6     .15       0  5651.3      .1       0  6085.1      .2       0
Bank Sta=4946.4,5053.6
XS Rating Curve= 0 ,0
Exp/Cntr=0.3,0.1

Type RM Length L Ch R = 1 ,486163.0,711.1,711.1,711.1
BEGIN DESCRIPTION:
Cross Section Contentnea Creek 48.0
END DESCRIPTION:
#Sta/Elev= 30
  4057.5  141.15    4354  127.85    4434  126.58    4454  127.01    4494  125.01
    4534  124.86    4634  119.64    4734   117.9    4834  114.86 4952.95   115.7
 4957.05  113.55 4961.25   109.8 4972.05  104.97 4987.65  102.09 5007.35  100.74
 5045.45  109.01 5045.55   113.5 5047.05  115.32  5067.6  120.12  5247.6  119.07
  5267.6  120.18  5327.6  120.25  5387.6  118.21  5467.6  118.63  5507.6  117.68
  5764.4  120.28  5804.4  122.04    5875  123.14  6384.4  136.35  6407.9  137.66
#Mann= 5 , 1 , 0
  4057.5     .15       0 4952.95    .065       0 5047.05     .15       0
    5875      .1       0  6407.9      .2       0
Bank Sta=4952.95,5047.05
XS Rating Curve= 0 ,0
Exp/Cntr=0.3,0.1

Type RM Length L Ch R = 1 ,485451.9,1445.9,1445.9,1445.9
BEGIN DESCRIPTION:
Cross Section CCX_W152
Located At: CCX_W152 CNTL
END DESCRIPTION:
#Sta/Elev= 30
  4109.8  138.03  4149.8  132.52  4369.8  123.94  4449.8  123.69  4509.8  120.34
  4911.4  120.38  4940.2  119.07  4951.7  114.45    4960  108.55  4970.8  103.72
  4986.4  100.84  5006.1   99.49  5044.2  107.76  5044.3  112.25  5045.8  114.07
  5108.6  120.02  5128.6  118.59  5268.6  118.83  5348.6   114.7  5468.6  114.87
  5548.6  118.16  5708.6  117.97  5788.6  114.63  5988.6  117.87  6008.6  117.07
  6148.6  122.39  6168.6  121.21  6288.6  123.91  6353.3  126.87  6648.6  138.02
#Mann= 4 , 1 , 0
  4109.8     .15       0  4951.7    .065       0  5045.8     .15       0
  6353.3      .1       0
Bank Sta=4951.7,5045.8
XS Rating Curve= 0 ,0
Exp/Cntr=0.3,0.1

Type RM Length L Ch R = 1 ,484006.0,1347,1347,1347
BEGIN DESCRIPTION:
Cross Section Contentnea Creek 47.0
END DESCRIPTION:
#Sta/Elev= 30
  3162.8  137.31    3241  136.47  3262.8  135.07  3282.8  129.24  3322.8  120.89
  3382.8  116.05  3642.8  116.29  3682.8  115.54  3784.8  115.59  4771.8  116.07
  4882.8  116.12  4902.8  114.66  4942.8  117.33 4952.95  114.33 4957.05  112.18
 4961.25  108.43 4972.05   103.6 4987.65  100.72 5007.35   99.37 5045.45  107.64
 5045.55  112.13 5047.05  113.95    5240   118.5    5420  117.49  5511.2  121.68
    5620  126.67    5660  129.97    5680  130.29    5760   136.1    5780  136.17
#Mann= 8 , 1 , 0
  3162.8      .2       0  3162.8      .1       0    3241     .15       0
  3784.8      .1       0  4771.8     .15       0 4952.95    .065       0
 5047.05     .15       0  5511.2      .1       0
Bank Sta=4952.95,5047.05
XS Rating Curve= 0 ,0
Exp/Cntr=0.3,0.1

Type RM Length L Ch R = 1 ,482659.0,861.5,861.5,861.5
BEGIN DESCRIPTION:
Cross Section Contentnea Creek 46.0
END DESCRIPTION:
#Sta/Elev= 30
  3991.2  136.16  4032.6  134.29  4051.2  132.77  4213.2  131.97  4293.2  122.18
  4493.2  112.94  4524.6  113.29  4693.2  116.03  4828.2  114.75  4853.2  113.63
  4893.2  116.51 4921.25   105.7 4926.15  103.69 4953.85  101.74 4961.25   99.26
 4968.75  100.96 5072.25  102.45 5078.75  105.14  5079.3  105.17  5147.3  109.27
  5167.3  112.19    5218  109.28    5478   109.3    5558  119.29    6138  117.42
    6378  121.74    6538  126.18    6658   135.1  6730.9  137.84    6938  144.24
#Mann= 8 , 1 , 0
  3991.2      .1       0  4032.6     .15       0  4524.6      .1       0
  4828.2     .15       0 4921.25    .065       0 5078.75     .15       0
  5079.3      .1       0  6730.9      .2       0
Bank Sta=4921.25,5078.75
XS Rating Curve= 0 ,0
Exp/Cntr=0.5,0.3