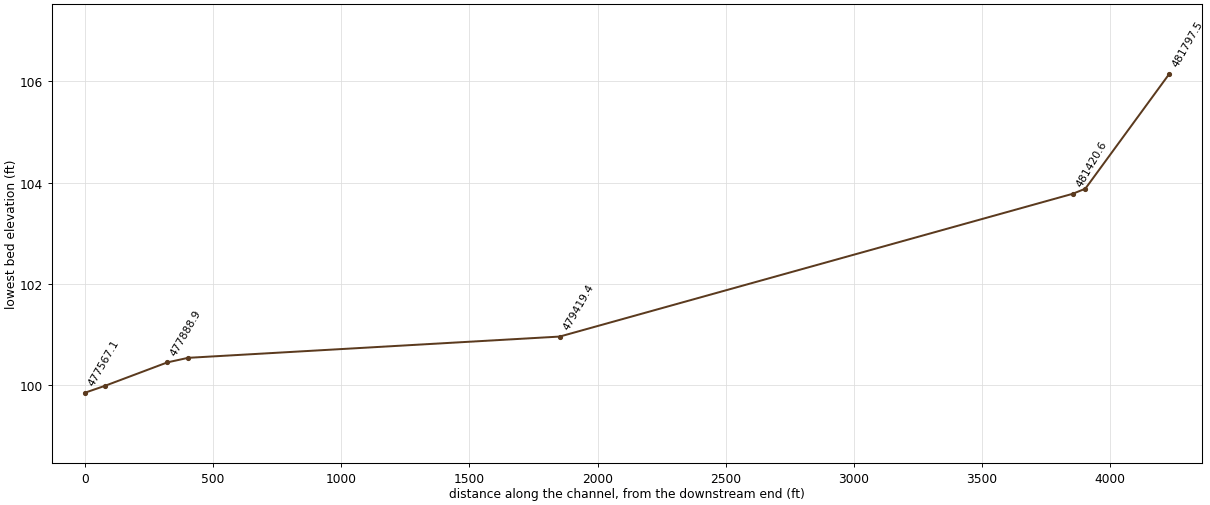
HEC-RAS study CONTENTNEA_FINAL.PRJ: Contentnea

--- CONTENTNEA_FINAL.g01 (geometry) --- (continued)

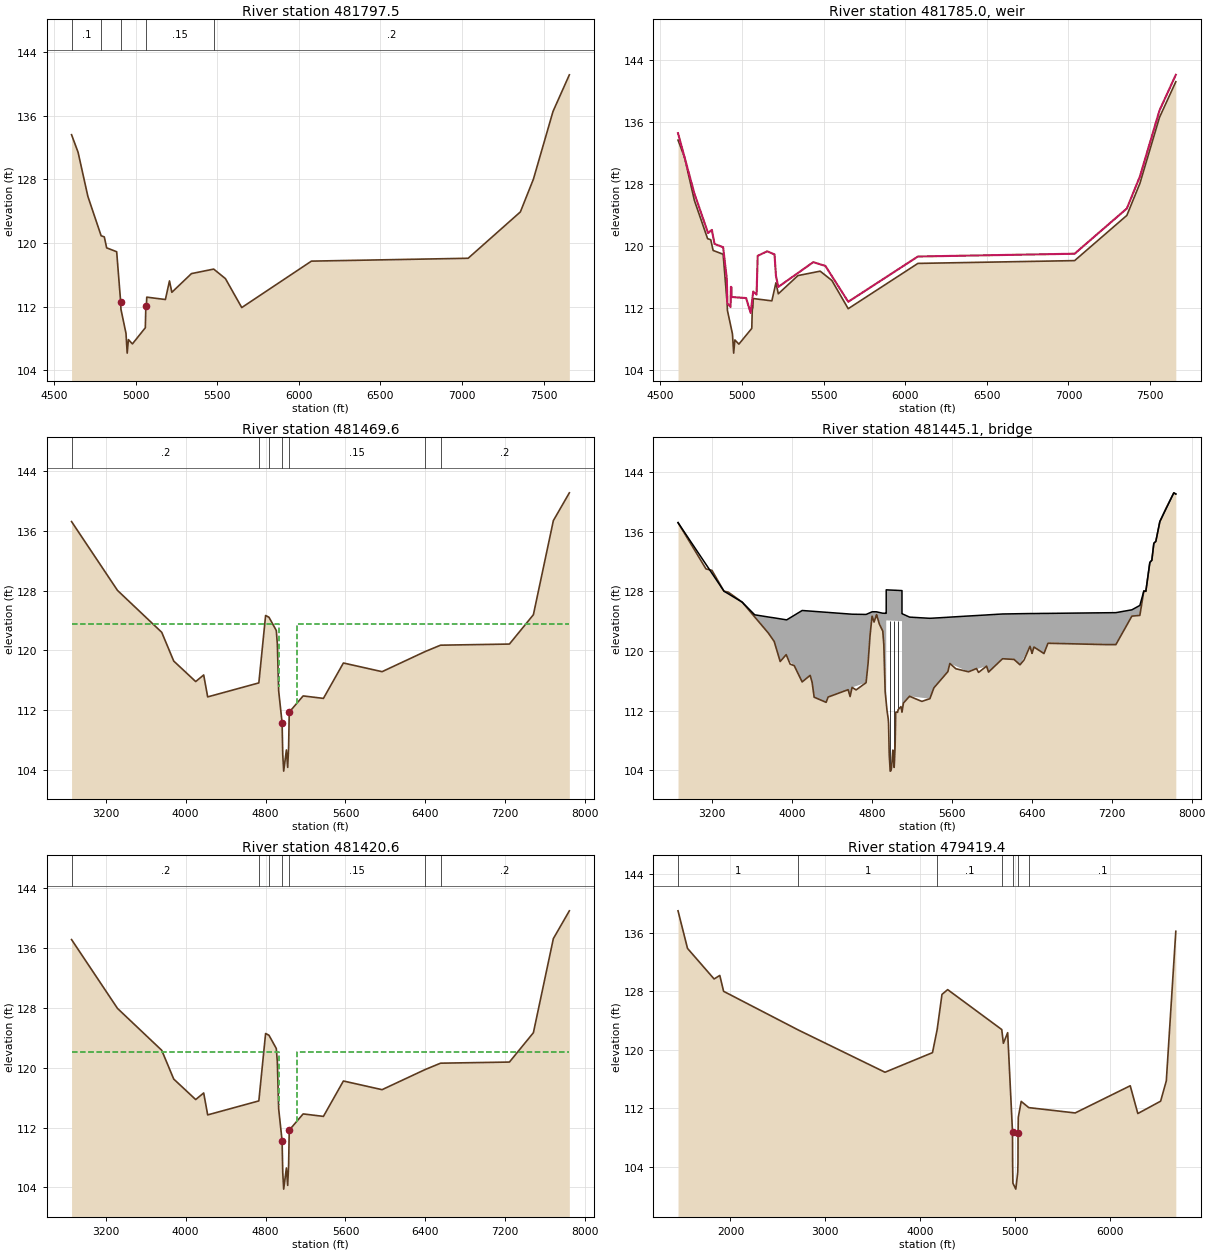
Type RM Length L Ch R = 1 ,481797.5,327.9,327.9,327.9
BEGIN DESCRIPTION:
Upstream Section of Bridge/Culvert/Weir
END DESCRIPTION:
#Sta/Elev= 30
  4608.1  133.62  4648.1  131.41  4708.1  125.86  4789.3  120.91  4808.7  120.77
  4823.1  119.39  4884.5   118.9    4909  112.59  4910.7  111.67  4941.6  108.63
    4949  106.15  4956.5  107.85  4980.9  107.31    5060  109.34  5062.9  111.73
  5066.5  112.03  5068.9  113.19    5183  112.89    5208  115.23  5222.6   113.8
  5342.6  116.15  5478.9  116.72  5550.8  115.52  5650.8  111.88  6077.7  117.72
  7037.7  118.08  7357.7  123.91  7437.7  128.04  7557.7  136.55  7657.7  141.15
#Mann= 5 , 1 , 0
  4608.1      .1       0  4789.3     .15       0    4909    .065       0
  5066.5     .15       0  5478.9      .2       0
#XS Ineff= 2 , 0
       0    4899  113.62  5076.5       0  112.77
Permanent Ineff=
       F       F
Bank Sta=4909,5066.5
XS Rating Curve= 0 ,0
Exp/Cntr=0.5,0.3

Type RM Length L Ch R = 5 ,481785.0,,,
BEGIN DESCRIPTION:
NC 42 DAM
Structure ID: WI_CONCR10A
END DESCRIPTION:
IW Pilot Flow=0
#Inline Weir SE= 30
  4608.1  134.51  4708.1  126.75  4792.1  121.63  4815.5  122.04  4831.4  120.24
  4884.5   119.8  4906.8  115.75  4910.7  112.57  4930.2  112.09    4932   114.7
  4935.7  114.65  4935.9  113.39  5025.3  113.25  5052.9  111.33  5068.9  114.09
  5089.3   113.7  5096.2   118.7  5154.3  119.28  5199.3  118.88    5208  116.12
  5222.6  114.69  5436.4  117.88  5510.8   117.4  5650.8  112.77  6077.7  118.61
  7037.7  118.97  7357.7   124.8  7437.7  128.93  7557.7  137.44  7657.7  142.04
IW Dist,WD,Coef,Skew,MaxSub,Min_El,Is_Ogee,SpillHt,DesHd
10,5,3,0,0.95,, 0 ,,,1,1,

Type RM Length L Ch R = 1 ,481469.6,49,49,49
BEGIN DESCRIPTION:
Upstream Section of Bridge/Culvert/Weir
END DESCRIPTION:
#Sta/Elev= 30
  2857.4  137.23  3317.4  128.03  3760.4  122.43  3880.4  118.59  4100.4  115.85
  4180.4  116.73  4220.4   113.8  4732.6  115.67  4800.4  124.68  4834.2  124.44
  4907.5  122.67  4917.9  120.87  4931.2   114.6  4965.4  110.35  4972.1   106.1
  4981.4  103.88  5008.6  106.71  5021.5  104.38    5031  107.15    5037  111.76
  5176.2  113.93  5379.3   113.6  5579.3  118.33  5966.5  117.17  6397.9  119.86
    6552  120.71  7241.6  120.86  7481.6  124.78  7681.6  137.36  7841.6  141.07
#Mann= 7 , 1 , 0
  2857.4      .2       0  4732.6      .1       0  4834.2     .15       0
  4965.4    .065       0    5037     .15       0  6397.9      .1       0
    6552      .2       0
#XS Ineff= 2 , 0
       0    4930   123.6    5110       0   123.6
Permanent Ineff=
       F       F
Bank Sta=4965.4,5037
XS Rating Curve= 0 ,0
Exp/Cntr=0.5,0.3

Type RM Length L Ch R = 3 ,481445.1,,,
BEGIN DESCRIPTION:
NC 42
Structure ID: WI_CONCR10
END DESCRIPTION:
Bridge Culvert--1,0,-1,-1, 0
Deck Dist Width WeirC Skew NumUp NumDn MinLoCord MaxHiCord MaxSubmerge Is_Ogee
10,29,2.6,0, 60, 60, , , 0.95, 0, 1,1,,
  2857.4  3317.4  3500.4  3625.2  3760.4  3820.4  3880.4  3945.2  4100.4  4180.4
  4220.4  4340.4  4560.4  4580.4  4600.4  4740.4  4800.4  4820.4  4845.1  4907.5
  4917.9  4931.2  4941.5 4941.87 4941.98 4942.21  4942.3 5099.77 5099.88 5099.99
  5100.1  5100.4  5114.6  5176.2  5379.3  5419.3  5559.3  5579.3  5766.5  5946.5
  5966.5  6106.5  6281.6  6381.6  6401.6  6421.6  6521.6  6561.6  7241.6  7401.6
  7481.6  7521.6  7541.6  7581.6  7601.6  7621.6  7641.6  7681.6  7821.6  7841.6
  137.24  128.04  126.56  124.87  124.58  124.46  124.33  124.19  125.45  125.37
  125.33  125.21  124.99  124.97  124.95  124.92  125.27  125.28  125.27  125.08
  125.08  125.07  125.07  125.12  128.22  128.22  128.22  128.12  125.02  125.02
  125.02  125.02  124.93  124.56   124.4  124.43  124.54  124.56  124.71  124.85
  124.87  124.98  125.02  125.04  125.04  125.04  125.06  125.06  125.16  125.54
  126.13  128.07  128.03   131.9   132.2  134.47  134.73  137.38  141.24  141.08
  137.24  128.04  126.56  124.58  122.44  121.29   118.6  119.37  115.86  116.74
  113.81  113.12  114.82   113.9  115.13  115.76  124.69   123.9  124.89  122.68
  120.88  114.61  113.19  113.14  113.12  113.09  124.12  124.02  124.02  124.02
  111.83  111.81  113.03  113.94  113.61  115.06  117.24  118.34  117.22  117.98
  117.18  118.97  118.16  120.64  119.69  120.54  119.67  121.05  120.87  124.69
  124.79  128.06  128.02  131.89  132.19  134.46  134.72  137.37  141.24  141.08
  2857.4  3317.4  3500.4  3625.2  3760.4  3820.4  3880.4  3945.2  4100.4  4180.4
  4220.4  4340.4  4560.4  4580.4  4600.4  4740.4  4800.4  4820.4  4845.1  4907.5
  4917.9  4931.2  4941.5 4941.87 4941.98 4942.21  4942.3 5099.77 5099.88 5099.99
  5100.1  5100.4  5114.6  5176.2  5379.3  5419.3  5559.3  5579.3  5766.5  5946.5
  5966.5  6106.5  6281.6  6381.6  6401.6  6421.6  6521.6  6561.6  7241.6  7401.6
  7481.6  7521.6  7541.6  7581.6  7601.6  7621.6  7641.6  7681.6  7821.6  7841.6
  137.24  128.04  126.56  124.87  124.58  124.46  124.33  124.19  125.45  125.37
  125.33  125.21  124.99  124.97  124.95  124.92  125.27  125.28  125.27  125.08
  125.08  125.07  125.07  125.12  128.22  128.22  128.22  128.12  125.02  125.02
  125.02  125.02  124.93  124.56   124.4  124.43  124.54  124.56  124.71  124.85
  124.87  124.98  125.02  125.04  125.04  125.04  125.06  125.06  125.16  125.54
  126.13  128.07  128.03   131.9   132.2  134.47  134.73  137.38  141.24  141.08
  137.14  127.94  126.46  124.48  122.34  121.19   118.5  119.27  115.76  116.64
  113.71  113.02  114.72   113.8  115.03  115.66  124.59   123.8  124.79  122.58
  120.78  114.51  113.09  113.04  113.02  112.99  124.02  123.92  123.92  123.92
  111.73  111.71  112.93  113.84  113.51  114.96  117.14  118.24  117.12  117.88
  117.08  118.87  118.06  120.54  119.59  120.44  119.57  120.95  120.77  124.59
  124.69  127.96  127.92  131.79  132.09  134.36  134.62  137.27  141.14  140.98
Pier Skew, UpSta & Num, DnSta & Num=  ,4981.4, 2 ,4981.4, 2 , 0 , 0 , 0 ,,
     3.5     3.5
   102.9   125.1
     3.5     3.5
   102.8     125
Pier Skew, UpSta & Num, DnSta & Num=  ,5021.5, 2 ,5021.5, 2 , 0 , 0 , 0 ,,
     3.5     3.5
  103.67  125.07
     3.5     3.5
  103.57  124.97
Pier Skew, UpSta & Num, DnSta & Num=  ,5061, 2 ,5061, 2 , 0 , 0 , 0 ,,
     3.5     3.5
  111.01  125.04
     3.5     3.5
  110.91  124.94
BR Coef= 1 , 1 , 0 ,1.25, 0 ,,,0.8,0,2,0,
WSPro=,,,, 1 ,,,, 0 ,,,, 0 ,,,,-1 ,-1 ,-1 , 0 , 0 , 0 , 0 , 0
BR U #Sta/Elev= 124
  2857.4  137.24  3137.4  131.03  3197.4  130.83  3317.4  128.04  3360.4  127.91
  3500.4  126.56  3625.2  124.58  3760.4  122.44  3820.4  121.29  3880.4   118.6
  3940.4  119.52  3945.2  119.37  3980.4  118.25  4020.4  118.05  4067.6  116.76
  4100.4  115.86  4180.4  116.74  4200.4  115.78  4220.4  113.81  4340.4  113.12
  4360.4  113.83  4560.4  114.82  4580.4   113.9  4600.4  115.13  4640.4  114.79
  4727.8  115.64  4732.6  115.68  4740.4  115.76  4760.4  118.34  4780.4  122.12
  4781.1  122.21  4800.4  124.69  4820.4   123.9  4834.2  124.45  4837.6  124.59
  4845.1  124.89  4874.1  123.61  4894.5  123.04  4907.5  122.68  4917.9  120.88
  4931.2  114.61  4941.5  113.19 4941.87  113.14 4941.98  113.12 4942.09  113.11
 4942.21  113.09  4942.3  113.08  4942.4  113.07  4949.7  112.06  4962.6  110.84
  4965.4  110.36  4972.1  106.11    4975  105.45  4979.8  104.37  4981.4  103.89
  4989.1  103.93    4994  104.23  4999.1  105.02  5003.6  105.86  5008.6  106.72
  5012.9  105.79  5021.5  104.39    5025  105.32    5031  107.16    5037  111.77
  5043.5  111.83  5055.9  111.78  5061.1  112.13  5089.7  112.55  5099.6  111.87
 5099.66  111.86 5099.77  111.85 5099.88  111.85 5099.99  111.84  5100.1  111.83
  5100.4  111.81  5101.2  111.88  5114.6  113.03  5173.3   113.9  5176.2  113.94
  5210.4  113.74    5232  113.62  5287.9  113.31  5299.3  113.25  5344.9  113.46
  5379.3  113.61  5419.3  115.06  5559.3  117.24  5579.3  118.34  5639.3  117.63
  5766.5  117.22  5846.5  117.66  5866.5  117.14  5946.5  117.98  5966.5  117.18
  6106.5  118.97  6133.7  118.95  6221.6  118.88  6281.6  118.16  6321.6   118.8
  6381.6  120.64  6397.9  119.87  6401.6  119.69  6421.6  120.54  6521.6  119.67
    6552  120.72  6561.6  121.05  7141.6  120.87  7241.6  120.87  7353.2  123.53
  7401.6  124.69  7481.6  124.79  7521.6  128.06  7541.6  128.02  7581.6  131.89
  7601.6  132.19  7613.2  133.51  7621.6  134.46  7641.6  134.72  7681.6  137.37
  7741.6  139.11  7813.2  141.02  7821.6  141.24  7841.6  141.08
BR U #Mann= 7
  2857.4      .2  4732.6      .1  4834.2     .15  4965.4    .065    5037     .15
  6397.9      .1    6552      .2
BR U Banks=4965.4,5037
BR D #Sta/Elev= 124
  2857.4  137.14  3137.4  130.93  3197.4  130.73  3317.4  127.94  3360.4  127.81
  3500.4  126.46  3625.2  124.48  3760.4  122.34  3820.4  121.19  3880.4   118.5
  3940.4  119.42  3945.2  119.27  3980.4  118.15  4020.4  117.95  4067.6  116.66
  4100.4  115.76  4180.4  116.64  4200.4  115.68  4220.4  113.71  4340.4  113.02
  4360.4  113.73  4560.4  114.72  4580.4   113.8  4600.4  115.03  4640.4  114.69
  4727.8  115.54  4732.6  115.58  4740.4  115.66  4760.4  118.24  4780.4  122.02
  4781.1  122.11  4800.4  124.59  4820.4   123.8  4834.2  124.35  4837.6  124.49
  4845.1  124.79  4874.1  123.51  4894.5  122.94  4907.5  122.58  4917.9  120.78
  4931.2  114.51  4941.5  113.09 4941.87  113.04 4941.98  113.02 4942.09  113.01
 4942.21  112.99  4942.3  112.98  4942.4  112.97  4949.7  111.96  4962.6  110.74
  4965.4  110.26  4972.1  106.01    4975  105.35  4979.8  104.27  4981.4  103.79
  4989.1  103.83    4994  104.13  4999.1  104.92  5003.6  105.76  5008.6  106.62
  5012.9  105.69  5021.5  104.29    5025  105.22    5031  107.06    5037  111.67
  5043.5  111.73  5055.9  111.68  5061.1  112.03  5089.7  112.45  5099.6  111.77
 5099.66  111.76 5099.77  111.75 5099.88  111.75 5099.99  111.74  5100.1  111.73
  5100.4  111.71  5101.2  111.78  5114.6  112.93  5173.3   113.8  5176.2  113.84
  5210.4  113.64    5232  113.52  5287.9  113.21  5299.3  113.15  5344.9  113.36
  5379.3  113.51  5419.3  114.96  5559.3  117.14  5579.3  118.24  5639.3  117.53
  5766.5  117.12  5846.5  117.56  5866.5  117.04  5946.5  117.88  5966.5  117.08
  6106.5  118.87  6133.7  118.85  6221.6  118.78  6281.6  118.06  6321.6   118.7
  6381.6  120.54  6397.9  119.77  6401.6  119.59  6421.6  120.44  6521.6  119.57
    6552  120.62  6561.6  120.95  7141.6  120.77  7241.6  120.77  7353.2  123.43
  7401.6  124.59  7481.6  124.69  7521.6  127.96  7541.6  127.92  7581.6  131.79
  7601.6  132.09  7613.2  133.41  7621.6  134.36  7641.6  134.62  7681.6  137.27
  7741.6  139.01  7813.2  140.92  7821.6  141.14  7841.6  140.98
BR D #Mann= 7
  2857.4      .2  4732.6      .1  4834.2     .15  4965.4    .065    5037     .15
  6397.9      .1    6552      .2
BR D Banks=4965.4,5037
BC Design=,, 0 ,, 0 ,,,,,,
BC HTab HWMax=141.23
BC Use User HTab Curves=0
BC User HTab FreeFlow(D)= 0

Type RM Length L Ch R = 1 ,481420.6,2001.2,2001.2,2001.2
BEGIN DESCRIPTION:
Downstream Section of Bridge/Culvert/Weir
END DESCRIPTION:
#Sta/Elev= 30
  2857.4  137.13  3317.4  127.93  3760.4  122.33  3880.4  118.49  4100.4  115.75
  4180.4  116.63  4220.4   113.7  4732.6  115.57  4800.4  124.58  4834.2  124.34
  4907.5  122.57  4917.9  120.77  4931.2   114.5  4965.4  110.25  4972.1     106
  4981.4  103.78  5008.6  106.61  5021.5  104.28    5031  107.05    5037  111.66
  5176.2  113.83  5379.3   113.5  5579.3  118.23  5966.5  117.07  6397.9  119.76
    6552  120.61  7241.6  120.76  7481.6  124.68  7681.6  137.26  7841.6  140.97
#Mann= 7 , 1 , 0
  2857.4      .2       0  4732.6      .1       0  4834.2     .15       0
  4965.4    .065       0    5037     .15       0  6397.9      .1       0
    6552      .2       0
#XS Ineff= 2 , 0
       0    4930   122.1    5110       0   122.1
Permanent Ineff=
       F       F
Bank Sta=4965.4,5037
XS Rating Curve= 0 ,0
Exp/Cntr=0.5,0.3

Type RM Length L Ch R = 1 ,479419.4,1449.5,1449.5,1449.5
BEGIN DESCRIPTION:
Cross Section CCX_W151
Located At: CCX_W151 CNTL
END DESCRIPTION:
#Sta/Elev= 30
  1447.8  139.03  1547.8  133.89  1827.8  129.71  1887.8  130.19  1927.8  128.02
  2715.9  122.72  3627.8  116.95  4127.8  119.63  4177.2   122.8  4227.8   127.6
  4287.8  128.25  4857.3  122.79  4874.4  120.91  4919.7  122.36  4970.5   108.8
  4971.8  104.45    4975  101.77  5005.4  100.96  5025.6  103.26  5028.1  104.49
  5029.1  108.68  5031.6  110.78  5062.2  112.96    5142  112.11  5630.5  111.38
  6210.5   115.1  6290.5   111.3  6530.5  112.99  6590.5  115.77  6690.5  136.23
#Mann= 7 , 1 , 0
  1447.8       1       0  2715.9       1       0  4177.2      .1       0
  4857.3     .15       0  4970.5    .065       0  5029.1     .15       0
    5142      .1       0
Bank Sta=4970.5,5029.1
XS Rating Curve= 0 ,0
Exp/Cntr=0.5,0.3

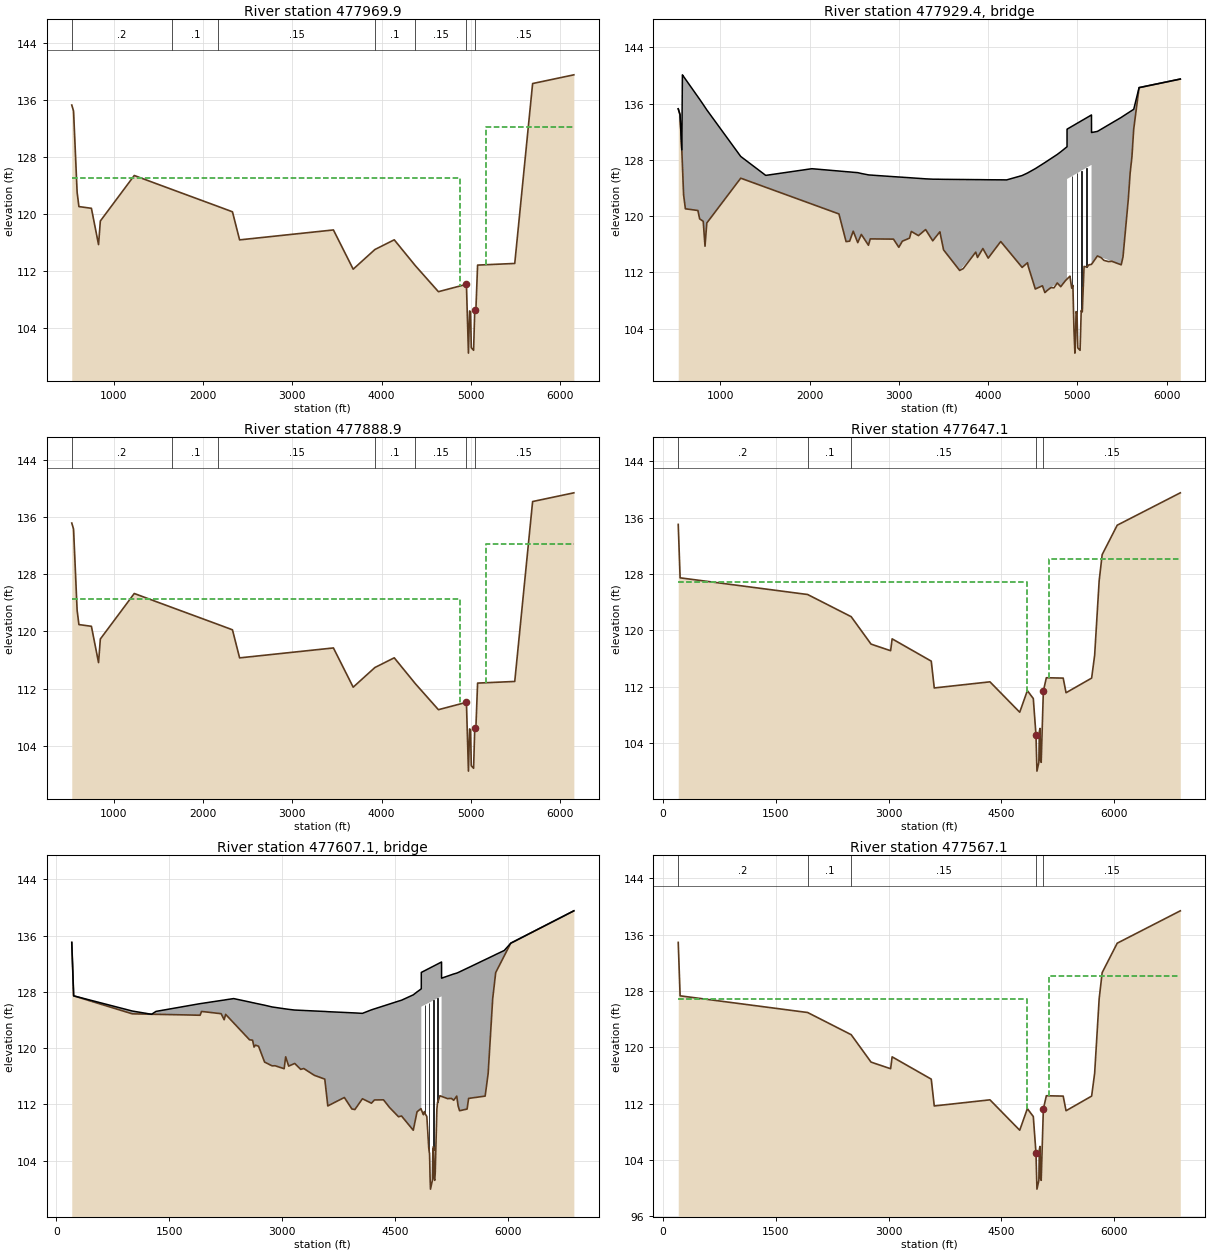
Type RM Length L Ch R = 1 ,477969.9,81,81,81
BEGIN DESCRIPTION:
Upstream Section of Bridge/Culvert/Weir
END DESCRIPTION:
#Sta/Elev= 30
   529.6  135.26   549.6  134.42   589.6  123.05   609.6  121.05   749.6  120.81
   829.6  115.73   849.6  119.03  1229.6   125.4  1655.6  123.43  2170.4  121.06
  2329.6  120.32  2409.6  116.39  3460.5  117.78  3681.9  112.29    3925  115.04
  4141.9   116.4    4378  112.78  4636.5  109.14  4950.4  110.17  4972.8  100.54
  4986.1  106.44  4996.6  106.34  5004.8   101.3  5030.7  100.94  5043.7   106.6
  5055.7   106.4  5075.5  112.86  5491.7  113.09  5691.7  138.27  6153.6  139.49
#Mann= 7 , 1 , 0
   529.6      .2       0  1655.6      .1       0  2170.4     .15       0
    3925      .1       0    4378     .15       0  4950.4    .065       0
  5043.7     .15       0
#XS Ineff= 2 , 0
       0    4875     125    5170       0   132.2
Permanent Ineff=
       F       F
Bank Sta=4950.4,5043.7
XS Rating Curve= 0 ,0
Exp/Cntr=0.5,0.3

Type RM Length L Ch R = 3 ,477929.4,,,
BEGIN DESCRIPTION:
I-95 SB
Structure ID: WI_CONCR9
END DESCRIPTION:
Bridge Culvert--1,0,-1,-1, 0
Deck Dist Width WeirC Skew NumUp NumDn MinLoCord MaxHiCord MaxSubmerge Is_Ogee
10,61,2.6,0, 60, 60, , , 0.95, 0, 1,1,,
   529.6   549.6   569.6   576.2   589.6   609.6   749.6   769.6   809.6   829.6
   849.6  1229.6  1509.6  2026.3  2329.6  2409.6  2449.6  2489.6  2540.5  2580.5
  2660.5  2680.5  2940.5  3000.5  3120.5  3140.5  3220.5  3300.5  3380.5  3460.5
  3501.9  3681.9  3861.9  3881.9  3941.9  4001.9  4141.9  4208.5  4381.9  4441.9
  4529.4  4609.4  4636.5  4775.5  4814.1 4884.67 4884.78 4885.01  4885.1 5158.77
 5158.88 5158.99  5159.1  5225.1  5491.7  5511.7  5611.7  5631.7  5691.7  6153.6
  135.26  134.42  129.43  140.09  139.85  139.49  136.97  136.61  135.87  135.49
  135.11  128.49   125.8  126.75  126.42  126.33  126.29  126.24  126.19  126.07
  125.87  125.85  125.62  125.57  125.47  125.45  125.38  125.31  125.26  125.25
  125.24  125.22   125.2   125.2  125.19  125.18  125.17  125.16  125.78  126.14
  126.76   127.4  127.62  128.78  129.15  129.87  132.37  132.37  132.37  134.39
  131.89  131.89  131.89  132.05  134.04  134.21  135.03  135.19  138.27  139.49
  135.26  134.42  129.43  127.32  123.05  121.05  120.81  119.62  119.27  115.73
  119.03   125.4  124.11  121.72  120.32  116.39  116.45  117.87  116.24  117.41
  115.87  116.77  116.74  115.58  116.88  117.83  117.24   118.1   116.5  117.78
  115.21  112.29  114.89  114.13   115.4  114.04   116.4  115.38  112.72  113.38
  109.65  110.11  109.14  110.51  109.98  111.06  111.07  111.07  125.28   127.3
   127.3   127.3  113.16  114.35  113.09  114.21  128.43  132.37  138.27  139.49
   529.6   549.6   569.6   576.2   589.6   609.6   749.6   769.6   809.6   829.6
   849.6  1229.6  1509.6  2026.3  2329.6  2409.6  2449.6  2489.6  2540.5  2580.5
  2660.5  2680.5  2940.5  3000.5  3120.5  3140.5  3220.5  3300.5  3380.5  3460.5
  3501.9  3681.9  3861.9  3881.9  3941.9  4001.9  4141.9  4208.5  4381.9  4441.9
  4529.4  4609.4  4636.5  4775.5  4814.1 4884.67 4884.78 4885.01  4885.1 5158.77
 5158.88 5158.99  5159.1  5225.1  5491.7  5511.7  5611.7  5631.7  5691.7  6153.6
  135.25  134.41  129.42  140.09  139.85  139.49  136.97  136.61  135.87  135.49
  135.11  128.49   125.8  126.75  126.42  126.33  126.29  126.24  126.19  126.07
  125.87  125.85  125.62  125.57  125.47  125.45  125.38  125.31  125.26  125.25
  125.24  125.22   125.2   125.2  125.19  125.18  125.17  125.16  125.78  126.14
  126.76   127.4  127.62  128.78  129.15  129.87  132.37  132.37  132.37  134.39
  131.89  131.89  131.89  132.05  134.04  134.21  135.03  135.19  138.27  139.48
  135.19  134.35  129.36  127.25  122.98  120.98  120.74  119.55   119.2  115.66
  118.96  125.33  124.04  121.65  120.25  116.32  116.38   117.8  116.17  117.34
   115.8   116.7  116.67  115.51  116.81  117.76  117.17  118.03  116.43  117.71
  115.14  112.22  114.82  114.06  115.33  113.97  116.33  115.31  112.65  113.31
  109.58  110.04  109.07  110.44  109.91  110.99     111     111  125.21  127.23
  127.23  127.23  113.09  114.28  113.02  114.14  128.36   132.3   138.2  139.42
Pier Skew, UpSta & Num, DnSta & Num=  ,4937.2, 2 ,4937.2, 2 , 0 , 0 , 0 ,,
     3.5     3.5
  108.82  126.68
     3.5     3.5
  108.75  126.61
Pier Skew, UpSta & Num, DnSta & Num=  ,4993.7, 2 ,4993.7, 2 , 0 , 0 , 0 ,,
     3.5     3.5
  105.25  127.09
     3.5     3.5
  105.18  127.02
Pier Skew, UpSta & Num, DnSta & Num=  ,5047.1, 2 ,5047.1, 2 , 0 , 0 , 0 ,,
     3.5     3.5
  105.47  127.49
     3.5     3.5
   105.4  127.42
Pier Skew, UpSta & Num, DnSta & Num=  ,5104.1, 2 ,5104.1, 2 , 0 , 0 , 0 ,,
     3.5     3.5
  111.79  127.91
     3.5     3.5
  111.72  127.84
Abutment Skew #Up #Dn= , 2 , 2
  4884.9  4917.3
  125.28  111.47
  4884.9  4917.3
  125.21   111.4
Abutment Skew #Up #Dn= , 2 , 2
  5130.3 5159.19
  113.09   127.3
  5130.3 5159.19
  113.02  127.23
BR Coef= 1 , 1 , 0 ,1.25, 0 ,,,0.8,0,2,0,
WSPro=,,,, 1 ,,,, 0 ,,,, 0 ,,,,-1 ,-1 ,-1 , 0 , 0 , 0 , 0 , 0
BR U #Sta/Elev= 129
   529.6  135.26   549.6  134.42   569.6  129.43   576.2  127.32   589.6  123.05
   609.6  121.05   749.6  120.81   769.6  119.62   793.9  119.41   809.6  119.27
   829.6  115.73   849.6  119.03  1104.6   123.3  1229.6   125.4  1309.6  125.03
  1509.6  124.11  1518.3  124.07  1655.6  123.43  1738.3  123.05  1798.3  122.77
  2026.3  121.72  2170.4  121.06  2329.6  120.32  2409.6  116.39  2449.6  116.45
  2489.6  117.87  2540.5  116.24  2566.3  116.99  2580.5  117.41  2606.3  116.91
  2660.5  115.87  2680.5  116.77  2705.9  116.77  2940.5  116.74  3000.5  115.58
  3040.5  116.45  3120.5  116.88  3140.5  117.83  3220.5  117.24  3300.5   118.1
    3361  116.89  3380.5   116.5  3460.5  117.78  3461.9  117.67  3501.9  115.21
  3681.9  112.29  3721.9  112.55  3861.9  114.89  3881.9  114.13    3925  115.04
  3941.9   115.4  4001.9  114.04  4141.9   116.4  4208.5  115.38  4268.5  114.46
    4378  112.78  4381.9  112.72  4388.5  112.79  4441.9  113.38  4449.4   112.9
    4503  110.72  4529.4  109.65  4609.4  110.11  4629.4  109.42  4636.5  109.14
  4638.9  109.17    4667  109.49  4696.4  109.77  4704.9  109.85  4738.3  109.82
  4751.3  110.06  4775.5  110.51  4806.6  110.08  4814.1  109.98  4858.1   110.7
  4866.3  110.83  4880.2  111.01 4884.67  111.06 4884.78  111.07 4884.89  111.07
 4885.01  111.07  4885.1  111.07  4917.2  111.48  4917.3  111.47  4929.6  110.47
  4937.2  109.77  4950.4  110.17  4962.1  104.03  4968.6  102.02  4972.8  100.54
  4979.8  102.86  4986.1  106.44  4993.7  106.19  4996.6  106.34  5004.8   101.3
  5030.7  100.94  5037.9  103.98  5043.7   106.6  5047.1  106.49  5055.7   106.4
  5075.5  112.86  5104.2  112.79  5114.9  112.86  5130.2  113.09  5130.3  113.09
    5158  113.14 5158.66  113.15 5158.77  113.15 5158.88  113.16 5158.99  113.16
  5159.1  113.16  5163.2  113.23  5219.4  114.25  5225.1  114.35  5266.2  114.11
    5273  114.03  5298.4  113.72  5326.5  113.63  5348.8  113.55  5382.9  113.59
  5386.4  113.59  5491.7  113.09  5511.7  114.21  5571.7  122.48  5591.7  126.13
  5611.7  128.43  5631.7  132.37  5691.7  138.27  6153.6  139.49
BR U #Mann= 7
   529.6      .2  1655.6      .1  2170.4     .15    3925      .1    4378     .15
  4950.4    .065  5043.7     .15
BR U Banks=4950.4,5043.7
BR D #Sta/Elev= 129
   529.6  135.19   549.6  134.35   569.6  129.36   576.2  127.25   589.6  122.98
   609.6  120.98   749.6  120.74   769.6  119.55   793.9  119.34   809.6   119.2
   829.6  115.66   849.6  118.96  1104.6  123.23  1229.6  125.33  1309.6  124.96
  1509.6  124.04  1518.3     124  1655.6  123.36  1738.3  122.98  1798.3   122.7
  2026.3  121.65  2170.4  120.99  2329.6  120.25  2409.6  116.32  2449.6  116.38
  2489.6   117.8  2540.5  116.17  2566.3  116.92  2580.5  117.34  2606.3  116.84
  2660.5   115.8  2680.5   116.7  2705.9   116.7  2940.5  116.67  3000.5  115.51
  3040.5  116.38  3120.5  116.81  3140.5  117.76  3220.5  117.17  3300.5  118.03
    3361  116.82  3380.5  116.43  3460.5  117.71  3461.9   117.6  3501.9  115.14
  3681.9  112.22  3721.9  112.48  3861.9  114.82  3881.9  114.06    3925  114.97
  3941.9  115.33  4001.9  113.97  4141.9  116.33  4208.5  115.31  4268.5  114.39
    4378  112.71  4381.9  112.65  4388.5  112.72  4441.9  113.31  4449.4  112.83
    4503  110.65  4529.4  109.58  4609.4  110.04  4629.4  109.35  4636.5  109.07
  4638.9   109.1    4667  109.42  4696.4   109.7  4704.9  109.78  4738.3  109.75
  4751.3  109.99  4775.5  110.44  4806.6  110.01  4814.1  109.91  4858.1  110.63
  4866.3  110.76  4880.2  110.94 4884.67  110.99 4884.78     111 4884.89     111
 4885.01     111  4885.1     111  4917.2  111.41  4917.3   111.4  4929.6   110.4
  4937.2   109.7  4950.4   110.1  4962.1  103.96  4968.6  101.95  4972.8  100.47
  4979.8  102.79  4986.1  106.37  4993.7  106.12  4996.6  106.27  5004.8  101.23
  5030.7  100.87  5037.9  103.91  5043.7  106.53  5047.1  106.42  5055.7  106.33
  5075.5  112.79  5104.2  112.72  5114.9  112.79  5130.2  113.02  5130.3  113.02
    5158  113.07 5158.66  113.08 5158.77  113.08 5158.88  113.09 5158.99  113.09
  5159.1  113.09  5163.2  113.16  5219.4  114.18  5225.1  114.28  5266.2  114.04
    5273  113.96  5298.4  113.65  5326.5  113.56  5348.8  113.48  5382.9  113.52
  5386.4  113.52  5491.7  113.02  5511.7  114.14  5571.7  122.41  5591.7  126.06
  5611.7  128.36  5631.7   132.3  5691.7   138.2  6153.6  139.42
BR D #Mann= 7
   529.6      .2  1655.6      .1  2170.4     .15    3925      .1    4378     .15
  4950.4    .065  5043.7     .15
BR D Banks=4950.4,5043.7
BC Design=,, 0 ,, 0 ,,,,,,
BC HTab HWMax=139.49
BC Use User HTab Curves=0
BC User HTab FreeFlow(D)= 0

Type RM Length L Ch R = 1 ,477888.9,241.8,241.8,241.8
BEGIN DESCRIPTION:
Downstream Section of Bridge/Culvert/Weir
END DESCRIPTION:
#Sta/Elev= 30
   529.6  135.17   549.6  134.33   589.6  122.96   609.6  120.96   749.6  120.72
   829.6  115.64   849.6  118.94  1229.6  125.31  1655.6  123.34  2170.4  120.97
  2329.6  120.23  2409.6   116.3  3460.5  117.69  3681.9   112.2    3925  114.95
  4141.9  116.31    4378  112.69  4636.5  109.05  4950.4  110.08  4972.8  100.45
  4986.1  106.35  4996.6  106.25  5004.8  101.21  5030.7  100.85  5043.7  106.51
  5055.7  106.31  5075.5  112.77  5491.7     113  5691.7  138.18  6153.6   139.4
#Mann= 7 , 1 , 0
   529.6      .2       0  1655.6      .1       0  2170.4     .15       0
    3925      .1       0    4378     .15       0  4950.4    .065       0
  5043.7     .15       0
#XS Ineff= 2 , 0
       0    4875   124.5    5170       0   132.2
Permanent Ineff=
       F       F
Bank Sta=4950.4,5043.7
XS Rating Curve= 0 ,0
Exp/Cntr=0.5,0.3

Type RM Length L Ch R = 1 ,477647.1,80,80,80
BEGIN DESCRIPTION:
Upstream Section of Bridge/Culvert/Weir
END DESCRIPTION:
#Sta/Elev= 30
   204.6  135.05   229.6  127.46  1924.1  125.09  2502.7  121.94    2767  118.04
    3027   117.1    3047  118.79    3567  115.62    3607  111.81    4347  112.68
  4742.7  108.36    4844  111.43  4923.1  110.31  4958.9   105.1  4971.7   99.99
  4996.9  101.23  5003.5  105.65    5012  106.06    5020  101.49    5028  101.24
  5056.6  111.36  5096.6  113.26  5320.4  113.21  5358.3  111.13  5698.3  113.21
  5738.3  116.45  5798.3  127.04  5838.3  130.76  6038.3  134.94  6876.7  139.54
#Mann= 5 , 1 , 0
   204.6      .2       0  1924.1      .1       0  2502.7     .15       0
  4958.9    .065       0  5056.6     .15       0
#XS Ineff= 2 , 0
       0    4835   126.8    5132       0   130.1
Permanent Ineff=
       F       F
Bank Sta=4958.9,5056.6
XS Rating Curve= 0 ,0
Exp/Cntr=0.5,0.3

Type RM Length L Ch R = 3 ,477607.1,,,
BEGIN DESCRIPTION:
I-95 NB
Structure ID: WI_CONCR8
END DESCRIPTION:
Bridge Culvert--1,0,-1,-1, 0
Deck Dist Width WeirC Skew NumUp NumDn MinLoCord MaxHiCord MaxSubmerge Is_Ogee
10,60,2.6,0, 60, 60, , , 0.95, 0, 1,1,,
   204.6   229.6  1009.6  1264.6  1324.6  1909.6  1929.6  2189.6  2229.6  2249.6
  2356.2    2567    2607    2627    2647    2687    2767    2867    3027    3047
    3087    3167    3247    3287    3427    3567    3607    3827    3927    3967
    4067    4187    4227    4347    4547    4587  4742.7  4793.2    4844 4849.27
 4849.38 4849.61  4849.7 5118.77 5118.88 5118.99  5119.1  5280.5  5320.4  5338.3
  5358.3  5458.3  5478.3  5698.3  5738.3  5798.3  5838.3  5952.1  6038.3  6876.7
  135.03  127.44  125.28  124.82  125.23  126.33  126.36  126.78  126.84  126.88
  127.05  126.57  126.47  126.43  126.38  126.29  126.11  125.86  125.61  125.58
  125.52  125.42  125.38  125.36  125.29  125.22  125.19  125.08  125.03  125.01
  124.95  125.45  125.59     126  126.69  126.82  127.58     128  128.39  128.47
  130.77  130.77  130.77  132.25  129.95  129.95  129.95  130.55  130.67  130.75
  130.85  131.36  131.46  132.59  132.79   133.1  133.31  133.89  134.92  139.52
  135.03  127.44  124.88  124.82  124.81  124.68  125.22   124.9  124.04   124.8
  123.59  121.19  121.14  120.16  120.43  120.27  118.02  117.49  117.08  118.77
  117.45  117.83  116.99  117.11  116.15   115.6  111.79  112.99  111.36  111.28
  112.81  112.18  112.64  112.66  110.25  110.36  108.34  110.96  111.41  111.27
  111.27  111.26   125.9  127.38  127.38  127.38  113.15   112.6  113.19  111.82
  111.11  111.35  112.86  113.19  116.43  127.02  130.74  133.12  134.92  139.52
   204.6   229.6  1009.6  1264.6  1324.6  1909.6  1929.6  2189.6  2229.6  2249.6
  2356.2    2567    2607    2627    2647    2687    2767    2867    3027    3047
    3087    3167    3247    3287    3427    3567    3607    3827    3927    3967
    4067    4187    4227    4347    4547    4587  4742.7  4793.2    4844 4849.27
 4849.38 4849.61  4849.7 5118.77 5118.88 5118.99  5119.1  5280.5  5320.4  5338.3
  5358.3  5458.3  5478.3  5698.3  5738.3  5798.3  5838.3  5952.1  6038.3  6876.7
     135  127.41  125.28   124.8  125.23  126.33  126.36  126.78  126.84  126.88
  127.05  126.57  126.47  126.43  126.38  126.29  126.11  125.86  125.61  125.58
  125.52  125.42  125.38  125.36  125.29  125.22  125.19  125.08  125.03  125.01
  124.95  125.45  125.59     126  126.69  126.82  127.58     128  128.39  128.47
  130.77  130.77  130.77  132.25  129.95  129.95  129.95  130.55  130.67  130.75
  130.85  131.36  131.46  132.59  132.79   133.1  133.31  133.89   134.9  139.49
  134.93  127.34  124.78  124.72  124.71  124.58  125.12   124.8  123.94   124.7
  123.49  121.09  121.04  120.06  120.33  120.17  117.92  117.39  116.98  118.67
  117.35  117.73  116.89  117.01  116.05   115.5  111.69  112.89  111.26  111.18
  112.71  112.08  112.54  112.56  110.15  110.26  108.24  110.86  111.31  111.17
  111.17  111.16   125.8  127.28  127.28  127.28  113.05   112.5  113.09  111.72
  111.01  111.25  112.76  113.09  116.33  126.92  130.64  133.02  134.82  139.42
Pier Skew, UpSta & Num, DnSta & Num=  ,4901.4, 2 ,4901.4, 2 , 0 , 0 , 0 ,,
     3.5     3.5
  109.63   127.2
     3.5     3.5
  109.53   127.1
Pier Skew, UpSta & Num, DnSta & Num=  ,4955.7, 2 ,4955.7, 2 , 0 , 0 , 0 ,,
     3.5     3.5
  104.13  127.49
     3.5     3.5
  104.03  127.39
Pier Skew, UpSta & Num, DnSta & Num=  ,5010, 2 ,5010, 2 , 0 , 0 , 0 ,,
     3.5     3.5
  104.51  127.79
     3.5     3.5
  104.41  127.69
Pier Skew, UpSta & Num, DnSta & Num=  ,5065.3, 2 ,5065.3, 2 , 0 , 0 , 0 ,,
     3.5     3.5
  111.11   128.1
     3.5     3.5
  111.01     128
Abutment Skew #Up #Dn= , 2 , 2
  4849.5  4877.2
   125.9  110.55
  4849.5  4877.2
   125.8  110.45
Abutment Skew #Up #Dn= , 2 , 2
  5096.7 5119.19
  113.24  127.38
  5096.7 5119.19
  113.14  127.28
BR Coef= 1 , 1 , 0 ,1.25, 0 ,,,0.8,0,2,0,
WSPro=,,,, 1 ,,,, 0 ,,,, 0 ,,,,-1 ,-1 ,-1 , 0 , 0 , 0 , 0 , 0
BR U #Sta/Elev= 114
   204.6  135.03   229.6  127.44   960.6  125.04  1009.6  124.88  1020.6  124.88
  1044.6  124.87  1164.6  124.85  1264.6  124.82  1324.6  124.81  1334.2  124.81
  1789.4  124.71  1909.6  124.68  1924.1  125.07  1929.6  125.22  2189.6   124.9
  2229.6  124.04  2249.6   124.8  2356.2  123.59  2502.7  121.92    2567  121.19
    2607  121.14    2627  120.16    2647  120.43    2687  120.27    2767  118.02
  2796.2  117.87  2836.2  117.65    2867  117.49    2907   117.5    3027  117.08
    3047  118.77    3087  117.45  3135.6  117.68    3167  117.83    3247  116.99
    3287  117.11    3427  116.15    3567   115.6    3607  111.79    3687  112.23
    3827  112.99    3927  111.36    3967  111.28    4067  112.81  4095.6  112.66
  4103.9  112.62    4187  112.18    4227  112.64    4347  112.66    4427  111.58
    4547  110.25    4587  110.36  4633.1  109.76  4689.3  109.03  4742.7  108.34
  4744.1  108.41  4793.2  110.96  4799.3  111.01  4841.9  111.39    4844  111.41
 4849.27  111.27 4849.38  111.27 4849.49  111.27 4849.61  111.26  4849.7  111.26
  4877.1  110.55  4877.2  110.55  4891.1     111  4901.4  110.66  4923.1  110.29
  4948.3  105.86  4955.7  105.19  4958.9  105.08  4961.4  104.07  4966.1  101.66
  4971.7   99.97  4996.9  101.21  5003.5  105.63    5010  105.47    5012  106.04
    5020  101.47    5028  101.22  5034.7  102.27  5038.7  104.07  5056.6  111.34
  5065.3   112.3  5075.5  112.55  5096.6  113.24  5096.7  113.24 5118.66  113.15
 5118.77  113.15 5118.88  113.15 5118.99  113.15  5119.1  113.15  5120.9  113.14
  5198.7  112.83  5211.2  112.84    5250  112.86  5270.9  112.68  5280.5   112.6
  5320.4  113.19  5327.3  112.66  5338.3  111.82  5358.3  111.11  5458.3  111.35
  5478.3  112.86  5698.3  113.19  5738.3  116.43  5798.3  127.02  5838.3  130.74
  5952.1  133.12  6038.3  134.92  6649.6  138.27  6876.7  139.52
BR U #Mann= 5
   204.6      .2  1924.1      .1  2502.7     .15  4958.9    .065  5056.6     .15
BR U Banks=4958.9,5056.6
BR D #Sta/Elev= 114
   204.6  134.93   229.6  127.34   960.6  124.94  1009.6  124.78  1020.6  124.78
  1044.6  124.77  1164.6  124.75  1264.6  124.72  1324.6  124.71  1334.2  124.71
  1789.4  124.61  1909.6  124.58  1924.1  124.97  1929.6  125.12  2189.6   124.8
  2229.6  123.94  2249.6   124.7  2356.2  123.49  2502.7  121.82    2567  121.09
    2607  121.04    2627  120.06    2647  120.33    2687  120.17    2767  117.92
  2796.2  117.77  2836.2  117.55    2867  117.39    2907   117.4    3027  116.98
    3047  118.67    3087  117.35  3135.6  117.58    3167  117.73    3247  116.89
    3287  117.01    3427  116.05    3567   115.5    3607  111.69    3687  112.13
    3827  112.89    3927  111.26    3967  111.18    4067  112.71  4095.6  112.56
  4103.9  112.52    4187  112.08    4227  112.54    4347  112.56    4427  111.48
    4547  110.15    4587  110.26  4633.1  109.66  4689.3  108.93  4742.7  108.24
  4744.1  108.31  4793.2  110.86  4799.3  110.91  4841.9  111.29    4844  111.31
 4849.27  111.17 4849.38  111.17 4849.49  111.17 4849.61  111.16  4849.7  111.16
  4877.1  110.45  4877.2  110.45  4891.1   110.9  4901.4  110.56  4923.1  110.19
  4948.3  105.76  4955.7  105.09  4958.9  104.98  4961.4  103.97  4966.1  101.56
  4971.7   99.87  4996.9  101.11  5003.5  105.53    5010  105.37    5012  105.94
    5020  101.37    5028  101.12  5034.7  102.17  5038.7  103.97  5056.6  111.24
  5065.3   112.2  5075.5  112.45  5096.6  113.14  5096.7  113.14 5118.66  113.05
 5118.77  113.05 5118.88  113.05 5118.99  113.05  5119.1  113.05  5120.9  113.04
  5198.7  112.73  5211.2  112.74    5250  112.76  5270.9  112.58  5280.5   112.5
  5320.4  113.09  5327.3  112.56  5338.3  111.72  5358.3  111.01  5458.3  111.25
  5478.3  112.76  5698.3  113.09  5738.3  116.33  5798.3  126.92  5838.3  130.64
  5952.1  133.02  6038.3  134.82  6649.6  138.17  6876.7  139.42
BR D #Mann= 5
   204.6      .2  1924.1      .1  2502.7     .15  4958.9    .065  5056.6     .15
BR D Banks=4958.9,5056.6
BC Design=,, 0 ,, 0 ,,,,,,
BC HTab HWMax=139.54
BC Use User HTab Curves=0
BC User HTab FreeFlow(D)= 0

Type RM Length L Ch R = 1 ,477567.1,3257.1,3257.1,3257.1
BEGIN DESCRIPTION:
Downstream Section of Bridge/Culvert/Weir
END DESCRIPTION:
#Sta/Elev= 30
   204.6  134.91   229.6  127.32  1924.1  124.95  2502.7   121.8    2767   117.9
    3027  116.96    3047  118.65    3567  115.48    3607  111.67    4347  112.54
  4742.7  108.22    4844  111.29  4923.1  110.17  4958.9  104.96  4971.7   99.85
  4996.9  101.09  5003.5  105.51    5012  105.92    5020  101.35    5028   101.1
  5056.6  111.22  5096.6  113.12  5320.4  113.07  5358.3  110.99  5698.3  113.07
  5738.3  116.31  5798.3   126.9  5838.3  130.62  6038.3   134.8  6876.7   139.4
#Mann= 5 , 1 , 0
   204.6      .2       0  1924.1      .1       0  2502.7     .15       0
  4958.9    .065       0  5056.6     .15       0
#XS Ineff= 2 , 0
       0    4835   126.8    5132       0   130.1
Permanent Ineff=
       F       F
Bank Sta=4958.9,5056.6
XS Rating Curve= 0 ,0
Exp/Cntr=0.5,0.3