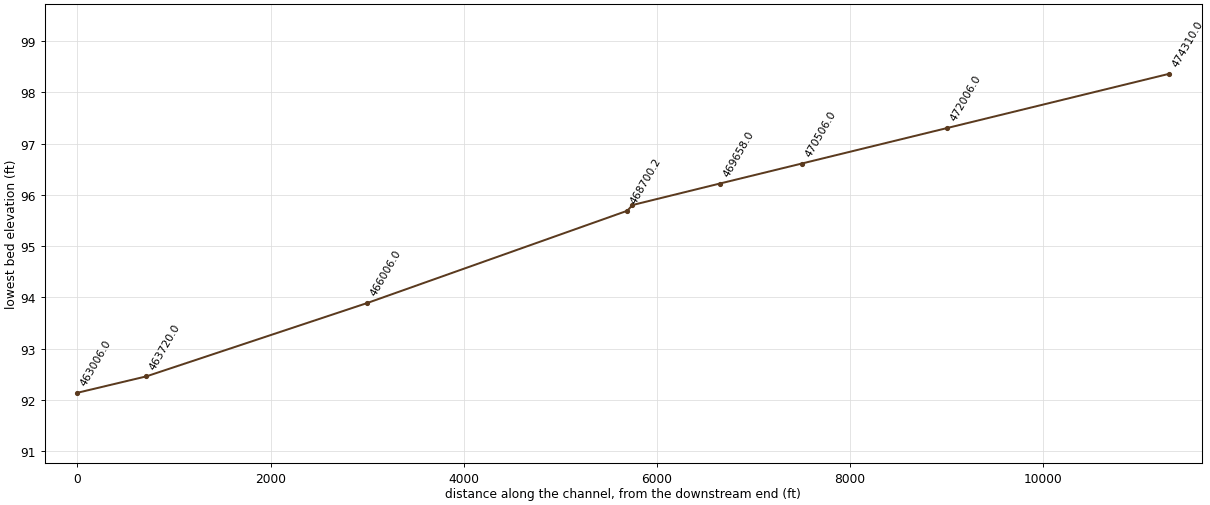
HEC-RAS study CONTENTNEA_FINAL.PRJ: Contentnea

--- CONTENTNEA_FINAL.g01 (geometry) --- (continued)

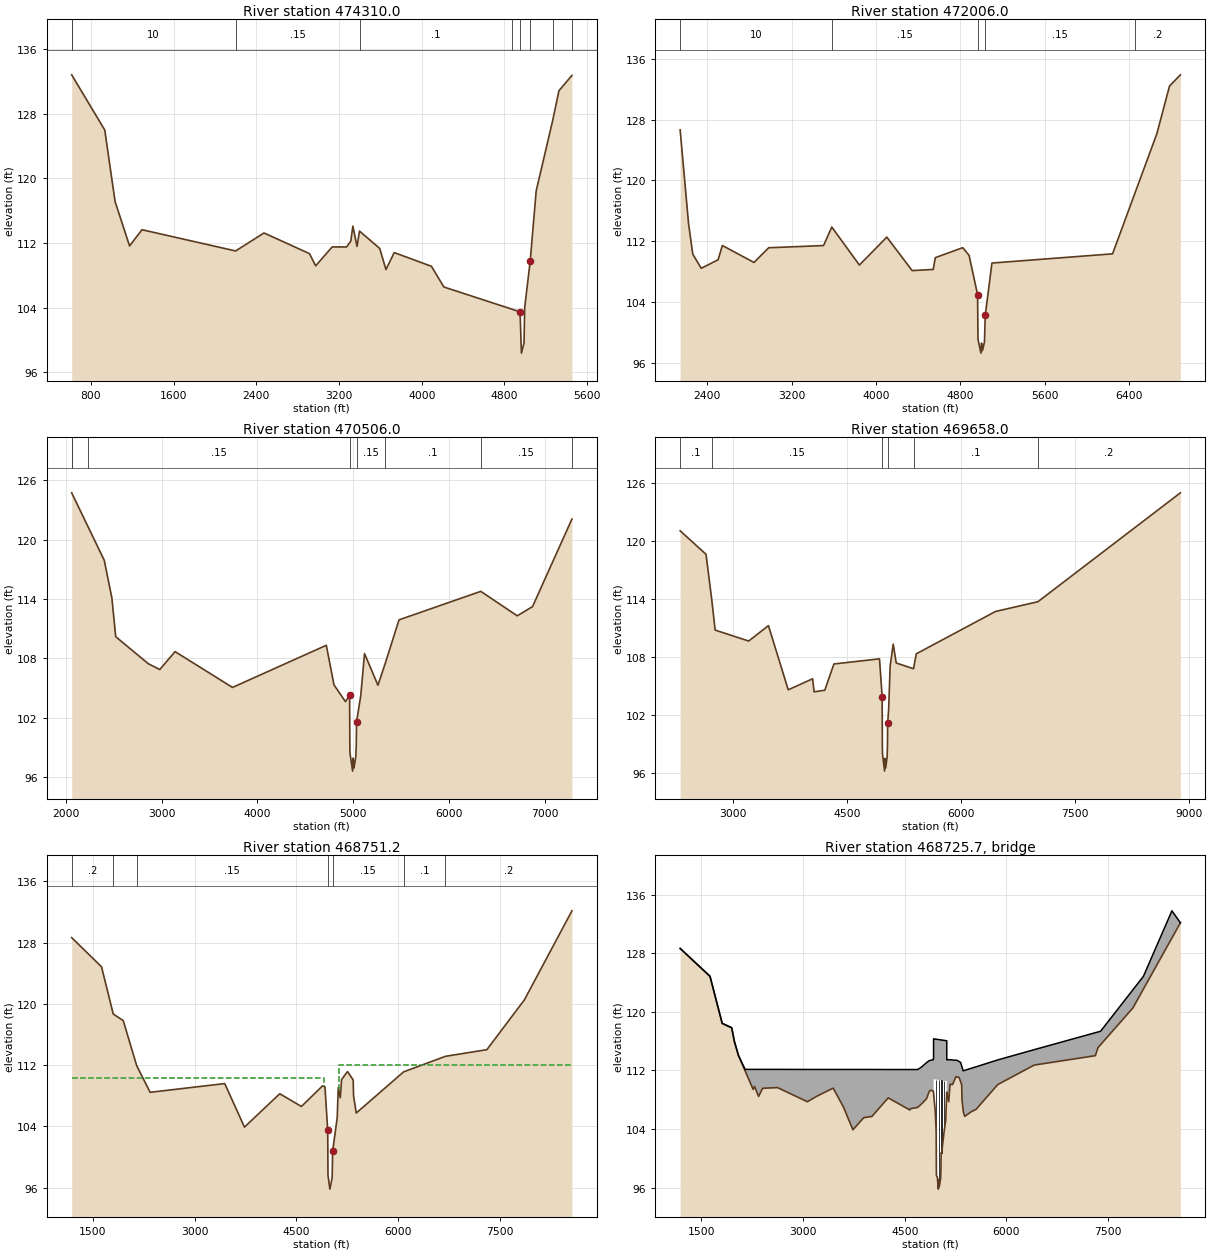
Type RM Length L Ch R = 1 ,474310.0,2304,2304,2304
BEGIN DESCRIPTION:
Cross Section Contentnea Creek 41.0
END DESCRIPTION:
#Sta/Elev= 30
   613.8  132.82   933.8  125.99  1033.8  117.12  1173.8  111.63  1293.8  113.64
  2199.8  111.01  2473.8  113.24  2913.8  110.68  2973.8  109.17  3133.8  111.51
  3273.8  111.51  3313.8  112.24  3333.8  114.09  3373.8  111.57    3398  113.47
  3593.8  111.32  3653.8   108.7  3733.8  110.81  4093.8  109.11  4213.8  106.55
  4875.1  103.79 4951.15  103.47 4963.95   98.36 4989.15    99.6 4995.75  104.02
 5048.85  109.73    5107  118.45  5267.4  127.22    5327  130.85  5452.7  132.75
#Mann= 9 , 1 , 0
   613.8      10       0   613.8      10       0  2199.8     .15       0
    3398      .1       0  4875.1     .15       0 4951.15    .065       0
 5048.85     .15       0  5267.4      .1       0  5452.7      .2       0
Bank Sta=4951.15,5048.85
XS Rating Curve= 0 ,0
Exp/Cntr=0.3,0.1

Type RM Length L Ch R = 1 ,472006.0,1500,1500,1500
BEGIN DESCRIPTION:
Cross Section Contentnea Creek 40.0
END DESCRIPTION:
#Sta/Elev= 30
  2143.1  126.65  2223.1   114.3  2263.1  110.31  2343.1  108.45  2503.1  109.57
  2543.1  111.45  2843.1  109.22  2983.1  111.15  3503.1  111.44  3581.1  113.87
  3843.1  108.88  4103.1  112.55  4343.1  108.15  4543.1   108.3  4563.1  109.85
  4823.1  111.16  4883.1  110.15  4963.7  104.99  4967.6   99.14  4995.4    97.3
  5001.2   98.62  5010.1   97.63    5029   98.77  5036.3  102.25    5100  109.14
  6243.8  110.35  6454.2  118.26  6663.8  126.14  6783.8   132.4  6887.1  133.88
#Mann= 5 , 1 , 0
  2143.1      10       0  3581.1     .15       0  4963.7    .065       0
  5036.3     .15       0  6454.2      .2       0
Bank Sta=4963.7,5036.3
XS Rating Curve= 0 ,0
Exp/Cntr=0.3,0.1

Type RM Length L Ch R = 1 ,470506.0,848,848,848
BEGIN DESCRIPTION:
Cross Section Contentnea Creek 39.0
END DESCRIPTION:
#Sta/Elev= 30
  2060.6  124.74  2234.2  121.26  2400.6  117.93  2480.6  114.11  2520.6   110.2
  2860.6  107.47  2980.6  106.88  3140.6  108.69  3740.6  105.07  4720.6  109.33
  4800.6  105.33  4920.6  103.63  4963.7   104.3  4966.3   99.41  4967.6   98.45
  4995.4   96.61  5001.2   97.93  5010.1   96.94    5029   98.08  5033.6   99.33
  5036.3  101.56    5080  104.22    5120  108.49    5260  105.29  5336.5  107.51
    5480   111.9  6334.2  114.78  6714.9  112.31  6874.9  113.24  7286.4  122.09
#Mann= 8 , 1 , 0
  2060.6      .2       0  2060.6      .1       0  2234.2     .15       0
  4963.7    .065       0  5036.3     .15       0  5336.5      .1       0
  6334.2     .15       0  7286.4      .2       0
Bank Sta=4963.7,5036.3
XS Rating Curve= 0 ,0
Exp/Cntr=0.3,0.1

Type RM Length L Ch R = 1 ,469658.0,906.8,906.8,906.8
BEGIN DESCRIPTION:
Cross Section Contentnea Creek 38.0
END DESCRIPTION:
#Sta/Elev= 30
  2310.1  121.05  2650.1  118.62  2724.2  114.01  2770.1  110.79  3210.1  109.66
  3470.1  111.25  3730.1  104.62  4050.1  105.76  4070.1  104.41  4210.1  104.58
  4330.1  107.29  4928.8  107.82  4963.7  103.91  4966.3   99.02  4967.6   98.06
  4995.4   96.22  5001.2   97.54  5010.1   96.55    5029   97.69  5033.6   98.94
  5036.3  101.17  5048.8  102.57  5068.8  107.08  5108.8  109.34  5148.8  107.39
  5375.7   106.8  5412.1  108.34  6452.1  112.71  7009.6  113.72  8881.4  124.97
#Mann= 6 , 1 , 0
  2310.1      .1       0  2724.2     .15       0  4963.7    .065       0
  5036.3     .15       0  5375.7      .1       0  7009.6      .2       0
Bank Sta=4963.7,5036.3
XS Rating Curve= 0 ,0
Exp/Cntr=0.5,0.3

Type RM Length L Ch R = 1 ,468751.2,51,51,51
BEGIN DESCRIPTION:
Upstream Section of Bridge/Culvert/Weir
END DESCRIPTION:
#Sta/Elev= 30
  1189.4  128.66  1629.4  124.85    1802  118.68  1949.4  117.82  2147.9  111.93
  2345.8  108.45  3445.8  109.59  3736.4   103.9  4256.4  108.26  4576.4   106.6
  4888.5   109.3    4923  109.16  4963.8  103.49  4967.7   97.64  4995.5    95.8
  5029.1   97.27  5036.4  100.75  5103.9  105.14    5119  109.05    5149  107.73
  5168.5  110.12  5255.6  111.16  5339.4  110.06  5344.5  108.02  5384.5  105.74
  6082.5  111.12  6698.8  113.15  7310.1  114.02    7864  120.54    8564  132.16
#Mann= 7 , 1 , 0
  1189.4      .2       0    1802      .1       0  2147.9     .15       0
  4963.8    .065       0  5036.4     .15       0  6082.5      .1       0
  6698.8      .2       0
#XS Ineff= 2 , 0
       0    4910   110.3    5125       0     112
Permanent Ineff=
       F       F
Bank Sta=4963.8,5036.4
XS Rating Curve= 0 ,0
Exp/Cntr=0.5,0.3

Type RM Length L Ch R = 3 ,468725.7,,,
BEGIN DESCRIPTION:
ST ROSE CHURCH RD (SR 1154)
Structure ID: WI_CONCR7
END DESCRIPTION:
Bridge Culvert--1,0,-1,-1, 0
Deck Dist Width WeirC Skew NumUp NumDn MinLoCord MaxHiCord MaxSubmerge Is_Ogee
10,31,2.6,0, 60, 60, , , 0.95, 0, 1,1,,
  1189.4  1629.4  1809.4  1949.4  1989.4  2049.4  2147.9  2265.8  2285.8  2345.8
  2405.8  2625.8  3065.8  3205.8  3445.8  3596.4  3736.4  3896.4  4016.4  4256.4
  4576.4  4584.5  4690.3  4740.3  4822.3    4861  4888.5  4920.4    4923 4925.17
 4925.28 4925.51  4925.6 5119.97 5120.08 5120.19  5120.3    5149  5168.5  5205.5
  5255.6  5274.1  5303.4  5323.9  5339.4  5344.5  5361.9  5364.5  5384.5    5491
    5551    5871    6411  7310.1  7350.1  7387.5    7864  8018.7  8439.1    8564
  128.66  124.86  118.43  117.83  115.95  114.04  112.14  112.14  112.14  112.14
  112.14  112.14  112.13  112.13  112.13  112.13  112.13  112.13  112.13  112.12
  112.12  112.12  112.12  112.41  113.07  113.33  113.39  113.46   113.6  113.71
  116.31  116.31  116.31  116.05  113.45  113.45  113.45  113.45  113.47  113.42
  113.38  113.38   113.2  113.08  112.62  112.46  111.94  111.95  112.01  112.32
  112.49  113.43  114.84  117.15  117.25  117.35  123.01  124.85  133.79  132.16
  128.65  124.84  118.41  117.81  115.93  114.02  111.92   109.4  109.82  108.44
  109.56  109.65  107.72  108.48  109.58  107.01  103.89  105.55  105.71  108.25
  106.59  106.77  106.94  107.36  108.14  109.14  109.29  109.16  109.15  108.93
  108.92   108.9   110.8  110.54  110.54  110.54  108.98  107.72  110.11  110.07
  111.15   111.1  111.01  110.46  110.05  108.01  106.53  106.31  105.73  106.41
  106.67  110.06  112.73  114.01  115.12  115.51  120.53   123.1  130.08  132.15
  1189.4  1629.4  1809.4  1949.4  1989.4  2049.4  2147.9  2265.8  2285.8  2345.8
  2405.8  2625.8  3065.8  3205.8  3445.8  3596.4  3736.4  3896.4  4016.4  4256.4
  4576.4  4584.5  4690.3  4740.3  4822.3    4861  4888.5  4920.4    4923 4925.17
 4925.28 4925.51  4925.6 5119.97 5120.08 5120.19  5120.3    5149  5168.5  5205.5
  5255.6  5274.1  5303.4  5323.9  5339.4  5344.5  5361.9  5364.5  5384.5    5491
    5551    5871    6411  7310.1  7350.1  7387.5    7864  8018.7  8439.1    8564
  128.66  124.86  118.43  117.83  115.95  114.04  112.14  112.14  112.14  112.14
  112.14  112.14  112.13  112.13  112.13  112.13  112.13  112.13  112.13  112.12
  112.12  112.12  112.12  112.41  113.07  113.33  113.39  113.46   113.6  113.71
  116.31  116.31  116.31  116.05  113.45  113.45  113.45  113.45  113.47  113.42
  113.38  113.38   113.2  113.08  112.62  112.46  111.94  111.95  112.01  112.32
  112.49  113.43  114.84  117.15  117.25  117.35  123.01  124.85  133.79  132.16
  128.56  124.75  118.32  117.72  115.84  113.93  111.83  109.31  109.73  108.35
  109.47  109.56  107.63  108.39  109.49  106.92   103.8  105.46  105.62  108.16
   106.5  106.68  106.85  107.27  108.05  109.05   109.2  109.07  109.06  108.84
  108.83  108.81  110.71  110.45  110.45  110.45  108.89  107.63  110.02  109.98
  111.06  111.01  110.92  110.37  109.96  107.92  106.44  106.22  105.64  106.32
  106.58  109.97  112.64  113.92  115.03  115.42  120.44  123.01  129.99  132.06
Pier Skew, UpSta & Num, DnSta & Num=  ,4961.3, 2 ,4961.3, 2 , 0 , 0 , 0 ,,
     2.2     2.2
  102.84  111.75
     2.2     2.2
  102.75  111.66
Pier Skew, UpSta & Num, DnSta & Num=  ,5001.3, 2 ,5001.3, 2 , 0 , 0 , 0 ,,
     2.2     2.2
   95.86   111.7
     2.2     2.2
   95.77  111.61
Pier Skew, UpSta & Num, DnSta & Num=  ,5041.2, 2 ,5041.2, 2 , 0 , 0 , 0 ,,
     2.2     2.2
   99.72  111.65
     2.2     2.2
   99.63  111.56
Pier Skew, UpSta & Num, DnSta & Num=  ,5081.4, 2 ,5081.4, 2 , 0 , 0 , 0 ,,
     2.2     2.2
   102.6  111.59
     2.2     2.2
  102.51   111.5
Abutment Skew #Up #Dn= , 2 , 2
    5104 5120.39
  105.16  110.54
    5104 5120.39
  105.07  110.45
BR Coef= 1 , 1 , 0 ,1.25, 0 ,,,0.8,0,2,0,
WSPro=,,,, 1 ,,,, 0 ,,,, 0 ,,,,-1 ,-1 ,-1 , 0 , 0 , 0 , 0 , 0
BR U #Sta/Elev= 96
  1189.4  128.65  1299.3   127.7  1629.4  124.84    1802  118.67  1809.4  118.41
  1949.4  117.81  1989.4  115.93  2049.4  114.02  2078.2  113.41  2147.9  111.92
  2265.8   109.4  2285.8  109.82  2345.8  108.44  2405.8  109.56  2625.8  109.65
  3065.8  107.72  3205.8  108.48  3445.8  109.58  3596.4  107.01  3736.4  103.89
  3896.4  105.55  4016.4  105.71  4256.4  108.25  4576.4  106.59  4584.5  106.77
  4690.2  106.94  4690.3  106.94  4724.6  107.23  4740.3  107.36  4762.3  107.55
  4796.9  107.89  4822.3  108.14  4858.4  109.07    4861  109.14  4888.5  109.29
  4920.4  109.16    4923  109.15 4925.17  108.93 4925.28  108.92 4925.39  108.91
 4925.51   108.9  4925.6  108.89  4925.7  108.88    4950  106.42  4961.3  104.12
  4963.8  103.48  4966.4   98.59  4967.7   97.63  4980.5   97.44  4995.5   95.79
  5001.3   97.11  5010.2   96.12  5029.1   97.26  5033.7   98.51  5036.4  100.74
  5041.2  100.73  5044.3  100.69  5081.4  103.69  5103.9  105.13    5104  105.16
    5119  109.04 5119.86     109 5119.97     109 5120.08  108.99 5120.19  108.99
  5120.3  108.98  5122.6  108.88    5149  107.72  5168.5  110.11    5171  110.11
  5205.5  110.07    5224  110.47  5255.6  111.15  5274.1   111.1  5303.4  111.01
  5323.9  110.46  5339.4  110.05  5344.5  108.01  5361.9  106.53  5364.5  106.31
  5384.5  105.73    5491  106.41    5551  106.67    5871  110.06  5910.9  110.26
  6082.5  111.11    6231  111.85    6411  112.73  6698.8  113.14  7310.1  114.01
  7350.1  115.12  7387.5  115.51    7864  120.53  8018.7   123.1  8439.1  130.08
    8564  132.15
BR U #Mann= 7
  1189.4      .2    1802      .1  2147.9     .15  4963.8    .065  5036.4     .15
  6082.5      .1  6698.8      .2
BR U Banks=4963.8,5036.4
BR D #Sta/Elev= 96
  1189.4  128.56  1299.3  127.61  1629.4  124.75    1802  118.58  1809.4  118.32
  1949.4  117.72  1989.4  115.84  2049.4  113.93  2078.2  113.32  2147.9  111.83
  2265.8  109.31  2285.8  109.73  2345.8  108.35  2405.8  109.47  2625.8  109.56
  3065.8  107.63  3205.8  108.39  3445.8  109.49  3596.4  106.92  3736.4   103.8
  3896.4  105.46  4016.4  105.62  4256.4  108.16  4576.4   106.5  4584.5  106.68
  4690.2  106.85  4690.3  106.85  4724.6  107.14  4740.3  107.27  4762.3  107.46
  4796.9   107.8  4822.3  108.05  4858.4  108.98    4861  109.05  4888.5   109.2
  4920.4  109.07    4923  109.06 4925.17  108.84 4925.28  108.83 4925.39  108.82
 4925.51  108.81  4925.6   108.8  4925.7  108.79    4950  106.33  4961.3  104.03
  4963.8  103.39  4966.4    98.5  4967.7   97.54  4980.5   97.35  4995.5    95.7
  5001.3   97.02  5010.2   96.03  5029.1   97.17  5033.7   98.42  5036.4  100.65
  5041.2  100.64  5044.3   100.6  5081.4   103.6  5103.9  105.04    5104  105.07
    5119  108.95 5119.86  108.91 5119.97  108.91 5120.08   108.9 5120.19   108.9
  5120.3  108.89  5122.6  108.79    5149  107.63  5168.5  110.02    5171  110.02
  5205.5  109.98    5224  110.38  5255.6  111.06  5274.1  111.01  5303.4  110.92
  5323.9  110.37  5339.4  109.96  5344.5  107.92  5361.9  106.44  5364.5  106.22
  5384.5  105.64    5491  106.32    5551  106.58    5871  109.97  5910.9  110.17
  6082.5  111.02    6231  111.76    6411  112.64  6698.8  113.05  7310.1  113.92
  7350.1  115.03  7387.5  115.42    7864  120.44  8018.7  123.01  8439.1  129.99
    8564  132.06
BR D #Mann= 7
  1189.4      .2    1802      .1  2147.9     .15  4963.8    .065  5036.4     .15
  6082.5      .1  6698.8      .2
BR D Banks=4963.8,5036.4
BC Design=,, 0 ,, 0 ,,,,,,
BC HTab HWMax=132.16
BC Use User HTab Curves=0
BC User HTab FreeFlow(D)= 0

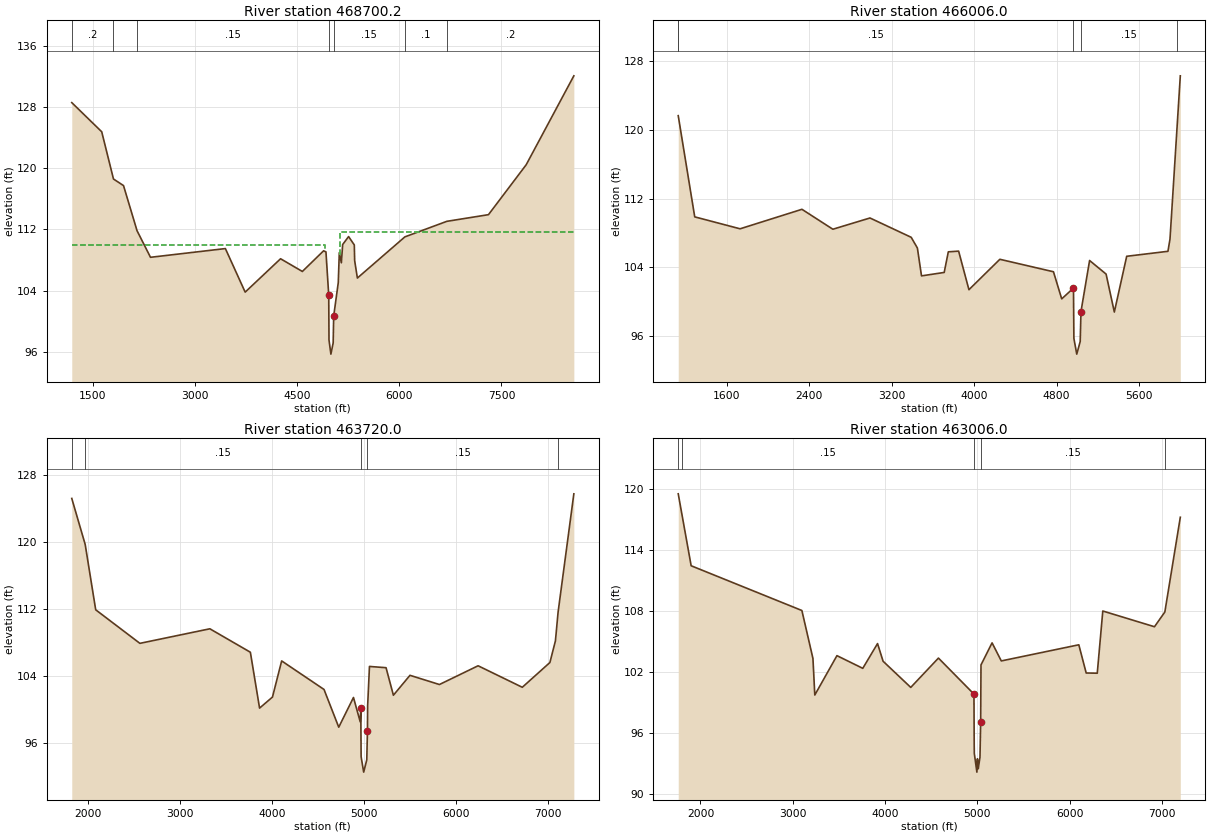
Type RM Length L Ch R = 1 ,468700.2,2694.2,2694.2,2694.2
BEGIN DESCRIPTION:
Downstream Section of Bridge/Culvert/Weir
END DESCRIPTION:
#Sta/Elev= 30
  1189.4  128.55  1629.4  124.74    1802  118.57  1949.4  117.71  2147.9  111.82
  2345.8  108.34  3445.8  109.48  3736.4  103.79  4256.4  108.15  4576.4  106.49
  4888.5  109.19    4923  109.05  4963.8  103.38  4967.7   97.53  4995.5   95.69
  5029.1   97.16  5036.4  100.64  5103.9  105.03    5119  108.94    5149  107.62
  5168.5  110.01  5255.6  111.05  5339.4  109.95  5344.5  107.91  5384.5  105.63
  6082.5  111.01  6698.8  113.04  7310.1  113.91    7864  120.43    8564  132.05
#Mann= 7 , 1 , 0
  1189.4      .2       0    1802      .1       0  2147.9     .15       0
  4963.8    .065       0  5036.4     .15       0  6082.5      .1       0
  6698.8      .2       0
#XS Ineff= 2 , 0
       0    4910     110    5125       0   111.7
Permanent Ineff=
       F       F
Bank Sta=4963.8,5036.4
XS Rating Curve= 0 ,0
Exp/Cntr=0.5,0.3

Type RM Length L Ch R = 1 ,466006.0,2286,2286,2286
BEGIN DESCRIPTION:
Cross Section Contentnea Creek 36.0
END DESCRIPTION:
#Sta/Elev= 30
  1129.5  121.65  1131.8  121.48  1289.5  109.87  1729.5  108.48  2329.5  110.75
  2629.5  108.43  2989.5  109.74  3389.5  107.49  3449.5  106.24  3489.5     103
  3709.5   103.4  3749.5   105.8  3849.5  105.88  3949.5  101.39  4249.5  104.93
  4769.5  103.48  4849.5  100.32  4963.7  101.58  4967.6   95.73  4995.4   93.89
    5029   95.36  5036.3   98.84    5120  104.79    5280  103.21    5360   98.79
    5480  105.28    5880  105.86    5900  107.29    5968  120.21    6000  126.29
#Mann= 5 , 1 , 0
  1129.5      .1       0  1131.8     .15       0  4963.7    .065       0
  5036.3     .15       0    5968      .1       0
Bank Sta=4963.7,5036.3
XS Rating Curve= 0 ,0
Exp/Cntr=0.3,0.1

Type RM Length L Ch R = 1 ,463720.0,714,714,714
BEGIN DESCRIPTION:
Cross Section Contentnea Creek 35.0
END DESCRIPTION:
#Sta/Elev= 30
  1824.5  125.17  1970.3  119.67  2084.5  111.86  2564.5  107.85  3324.5  109.59
  3764.5  106.79  3864.5  100.11  4004.5  101.43  4104.5  105.75  4564.5  102.34
  4724.5   97.83  4884.5  101.38  4958.2   98.46  4963.7  100.15  4967.6    94.3
  4995.4   92.46    5029   93.93  5036.3   97.41  5038.2  100.34  5058.2  105.09
  5238.2  104.94  5318.2  101.65  5498.2  104.03  5818.2  102.93  6238.2  105.17
  6718.2   102.6  7018.2  105.56  7078.2  108.15    7107  111.57  7278.2  125.72
#Mann= 5 , 1 , 0
  1824.5      .1       0  1970.3     .15       0  4963.7    .065       0
  5036.3     .15       0    7107      .1       0
Bank Sta=4963.7,5036.3
XS Rating Curve= 0 ,0
Exp/Cntr=0.3,0.1

Type RM Length L Ch R = 1 ,463006.0,1500,1500,1500
BEGIN DESCRIPTION:
Cross Section Contentnea Creek 34.0
END DESCRIPTION:
#Sta/Elev= 30
  1758.8  119.57  1798.3  117.57  1898.8  112.48  3098.8  108.07  3218.8  103.34
  3238.8   99.74  3478.8  103.62  3758.8  102.37  3918.8  104.81  3978.8  103.07
  4278.8  100.49  4578.8  103.38  4963.7   99.83  4966.3   94.94  4967.6   93.98
  4995.4   92.14  5001.2   93.46  5010.1   92.47    5029   93.61  5036.3   97.09
    5040  102.71    5160  104.88    5260   103.1    6100  104.69    6180  101.91
    6300  101.89    6360  108.02    6920  106.47  7032.4  107.92    7200  117.26
#Mann= 5 , 1 , 0
  1758.8      .1       0  1798.3     .15       0  4963.7    .065       0
  5036.3     .15       0  7032.4      .1       0
Bank Sta=4963.7,5036.3
XS Rating Curve= 0 ,0
Exp/Cntr=0.3,0.1