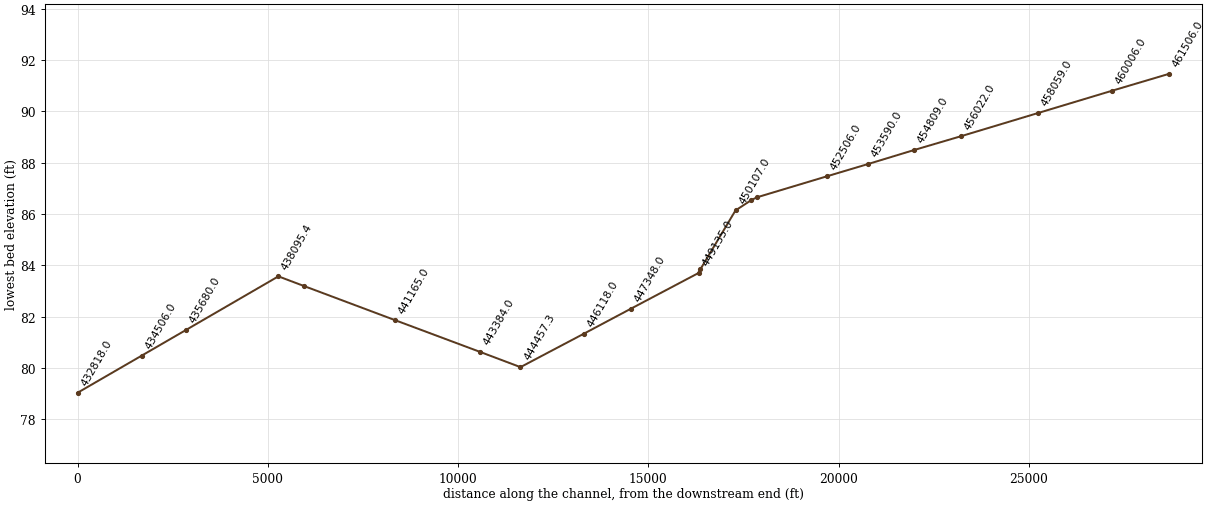
HEC-RAS study CONTENTNEA_FINAL.PRJ: Contentnea

--- CONTENTNEA_FINAL.g01 (geometry) --- (continued)

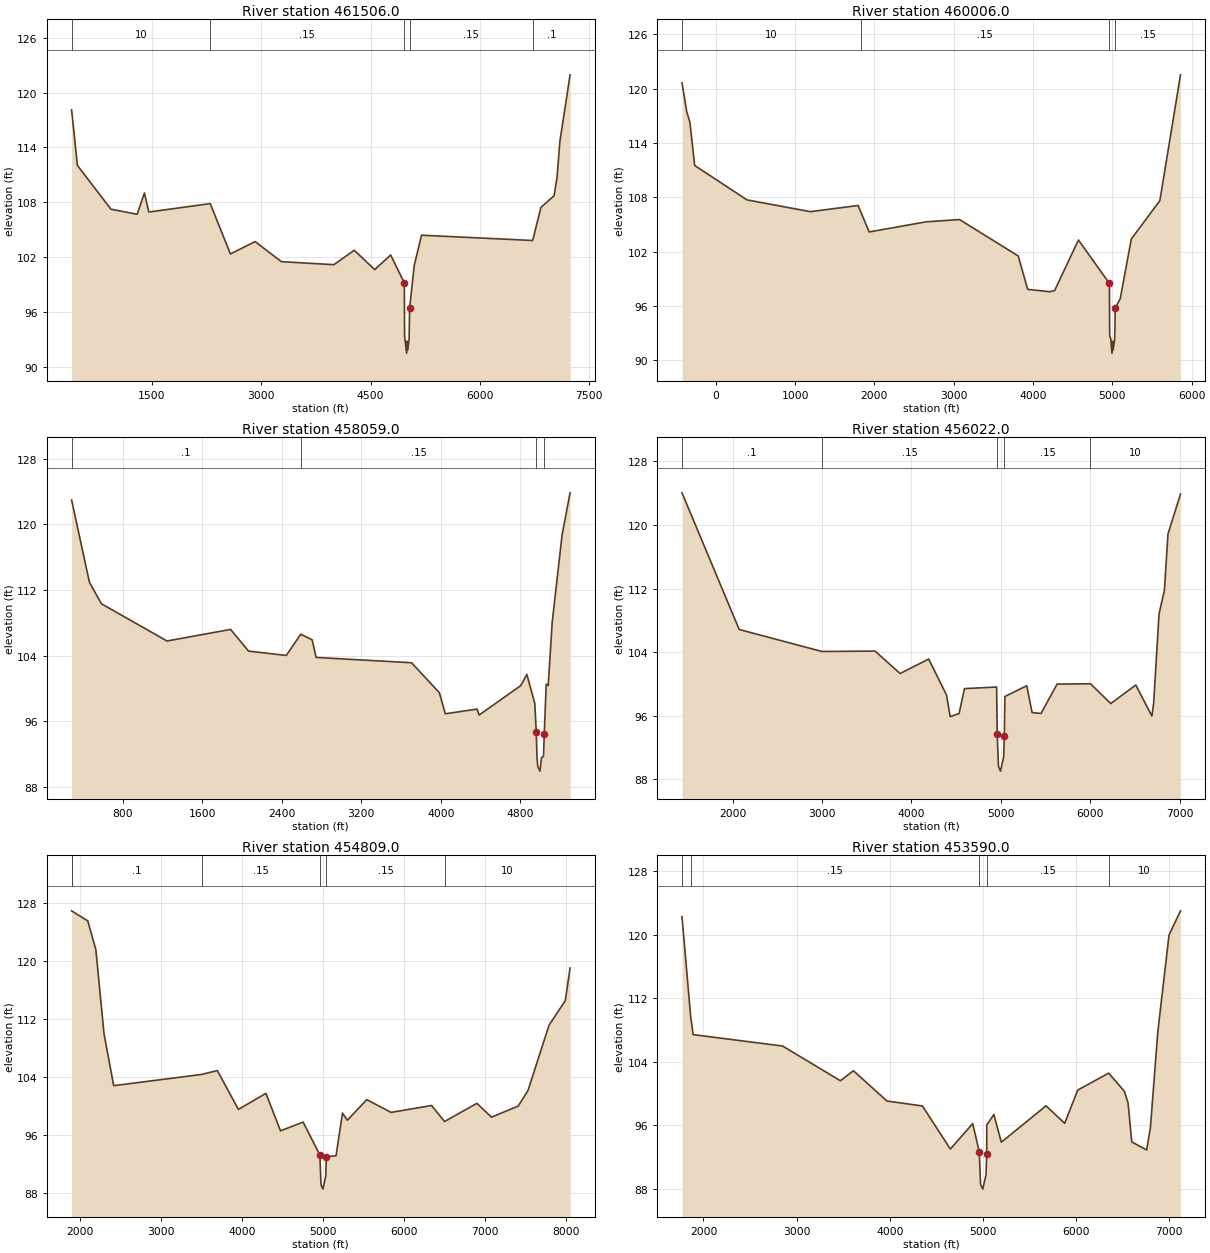
Type RM Length L Ch R = 1 ,461506.0,1500,1500,1500
BEGIN DESCRIPTION:
Cross Section Contentnea Creek 33.0
END DESCRIPTION:
#Sta/Elev= 30
   396.4  118.13   476.4  112.03   936.4  107.24  1296.4  106.68  1396.4  109.02
  1456.4  106.93  2299.4  107.85  2576.4  102.34  2916.4  103.69  3276.4  101.49
  3996.4  101.16  4276.4  102.74  4556.4  100.62  4776.4  102.22  4963.7   99.16
  4966.3   94.27  4967.6   93.31  4995.4   91.47  5001.2   92.79  5010.1    91.8
    5029   92.94  5036.3   96.42    5100  101.09    5200  104.39  6725.4  103.81
  6838.9  107.44  7018.9  108.71  7058.9  110.66  7098.9  114.66  7238.9  121.96
#Mann= 5 , 1 , 0
   396.4      10       0  2299.4     .15       0  4963.7    .065       0
  5036.3     .15       0  6725.4      .1       0
Bank Sta=4963.7,5036.3
XS Rating Curve= 0 ,0
Exp/Cntr=0.3,0.1

Type RM Length L Ch R = 1 ,460006.0,1947,1947,1947
BEGIN DESCRIPTION:
Cross Section Contentnea Creek 32.0
END DESCRIPTION:
#Sta/Elev= 30
  -426.7  120.66  -366.7  117.47  -326.7  116.28  -266.7  111.53   393.3  107.73
  1193.3  106.43  1793.3  107.11  1833.3   106.3  1933.3  104.19  2653.3  105.31
  3073.3  105.56  3813.3  101.54  3933.3   97.85  4213.3   97.59  4273.3   97.73
  4573.3   103.3  4963.7    98.5  4966.3   93.61  4967.6   92.65  4980.4   92.46
  4995.4   90.81  5001.2   92.13  5010.1   91.14    5029   92.28  5033.6   93.53
  5036.3   95.76    5100   96.82    5240  103.41    5600  107.65    5860  121.54
#Mann= 4 , 1 , 0
  -426.7      10       0  1833.3     .15       0  4963.7    .065       0
  5036.3     .15       0
Bank Sta=4963.7,5036.3
XS Rating Curve= 0 ,0
Exp/Cntr=0.3,0.1

Type RM Length L Ch R = 1 ,458059.0,2037,2037,2037
BEGIN DESCRIPTION:
Cross Section Contentnea Creek 31.2
END DESCRIPTION:
#Sta/Elev= 30
     285  122.99     465  112.94     585  110.34    1245   105.8    1885  107.21
    2065  104.57    2445  104.04    2590  106.62    2705  105.95    2745   103.8
    3705  103.15    3985    99.5    4045   96.93    4365    97.5    4385   96.78
    4805  100.37    4865  101.73    4945    98.2    4960   94.65  4966.5   91.88
  4974.3   90.54    4997   89.94  5012.6   91.57  5032.6   91.74    5040   94.42
  5060.1  100.54  5080.1  100.36  5120.1  108.08  5220.1  118.78  5300.1  123.86
#Mann= 4 , 1 , 0
     285      .1       0    2590     .15       0    4960    .065       0
    5040     .15       0
Bank Sta=4960,5040
XS Rating Curve= 0 ,0
Exp/Cntr=0.3,0.1

Type RM Length L Ch R = 1 ,456022.0,1213,1213,1213
BEGIN DESCRIPTION:
Cross Section Contentnea Creek 31.0
END DESCRIPTION:
#Sta/Elev= 30
  1433.7  124.04  2073.7  106.85  2999.7  104.08  3593.7  104.13  3873.7  101.31
  4193.7  103.13  4393.7   98.59  4433.7   95.89  4533.7   96.27  4593.7   99.41
  4953.7   99.61    4960   93.74  4974.3   89.63    4997   89.03  5032.6   90.83
    5040   93.51  5046.2   98.42  5290.6   99.77  5350.6   96.39  5450.6   96.29
  5630.6   99.98  6003.7  100.02  6230.6   97.53  6510.6   99.86  6690.6   95.96
  6710.6    97.6  6770.6   108.8  6830.6  111.78  6870.6  118.85  7010.6  123.89
#Mann= 5 , 1 , 0
  1433.7      .1       0  2999.7     .15       0    4960    .065       0
    5040     .15       0  6003.7      10       0
Bank Sta=4960,5040
XS Rating Curve= 0 ,0
Exp/Cntr=0.3,0.1

Type RM Length L Ch R = 1 ,454809.0,1219,1219,1219
BEGIN DESCRIPTION:
Cross Section Contentnea Creek 30.2
END DESCRIPTION:
#Sta/Elev= 30
  1893.7  126.94  2093.7  125.55  2193.7  121.56  2293.7  109.99  2413.7  102.79
  3499.7  104.34  3693.7  104.88  3953.7   99.51  4293.7  101.73  4473.7   96.55
  4753.7   97.76    4960   93.21  4974.3    89.1    4997    88.5  5032.6    90.3
    5040   92.98  5159.5    93.1  5239.5      99  5299.5   98.02  5539.5  100.86
  5839.5    99.1  6339.5  100.05  6499.7   97.84  6899.5  100.35  7079.5   98.44
  7410.3   99.98  7530.3  102.12  7790.3  111.14  7990.3  114.52  8050.3  119.04
#Mann= 6 , 1 , 0
  1893.7      10       0  1893.7      .1       0  3499.7     .15       0
    4960    .065       0    5040     .15       0  6499.7      10       0
Bank Sta=4960,5040
XS Rating Curve= 0 ,0
Exp/Cntr=0.3,0.1

Type RM Length L Ch R = 1 ,453590.0,1084,1084,1084
BEGIN DESCRIPTION:
Cross Section Contentnea Creek 30.0
END DESCRIPTION:
#Sta/Elev= 30
  1769.8   122.3  1863.6   109.6  1889.8  107.42  2849.8  105.98  3469.8  101.61
  3609.8  102.87  3969.8   99.05  4349.8   98.43  4649.8      93  4889.8   96.21
    4960   92.66  4974.3   88.55    4997   87.95  5032.6   89.75    5040   92.43
  5040.3   96.04  5116.6   97.35  5196.6   93.86  5676.6   98.45  5876.6   96.24
  6016.6  100.43  6348.8  102.57  6516.6  100.29  6556.6   98.84  6596.6   93.89
  6756.6   92.89  6796.6   95.69  6876.6  107.83  6996.6  119.97  7119.5  123.02
#Mann= 5 , 1 , 0
  1769.8      .1       0  1863.6     .15       0    4960    .065       0
    5040     .15       0  6348.8      10       0
Bank Sta=4960,5040
XS Rating Curve= 0 ,0
Exp/Cntr=0.3,0.1

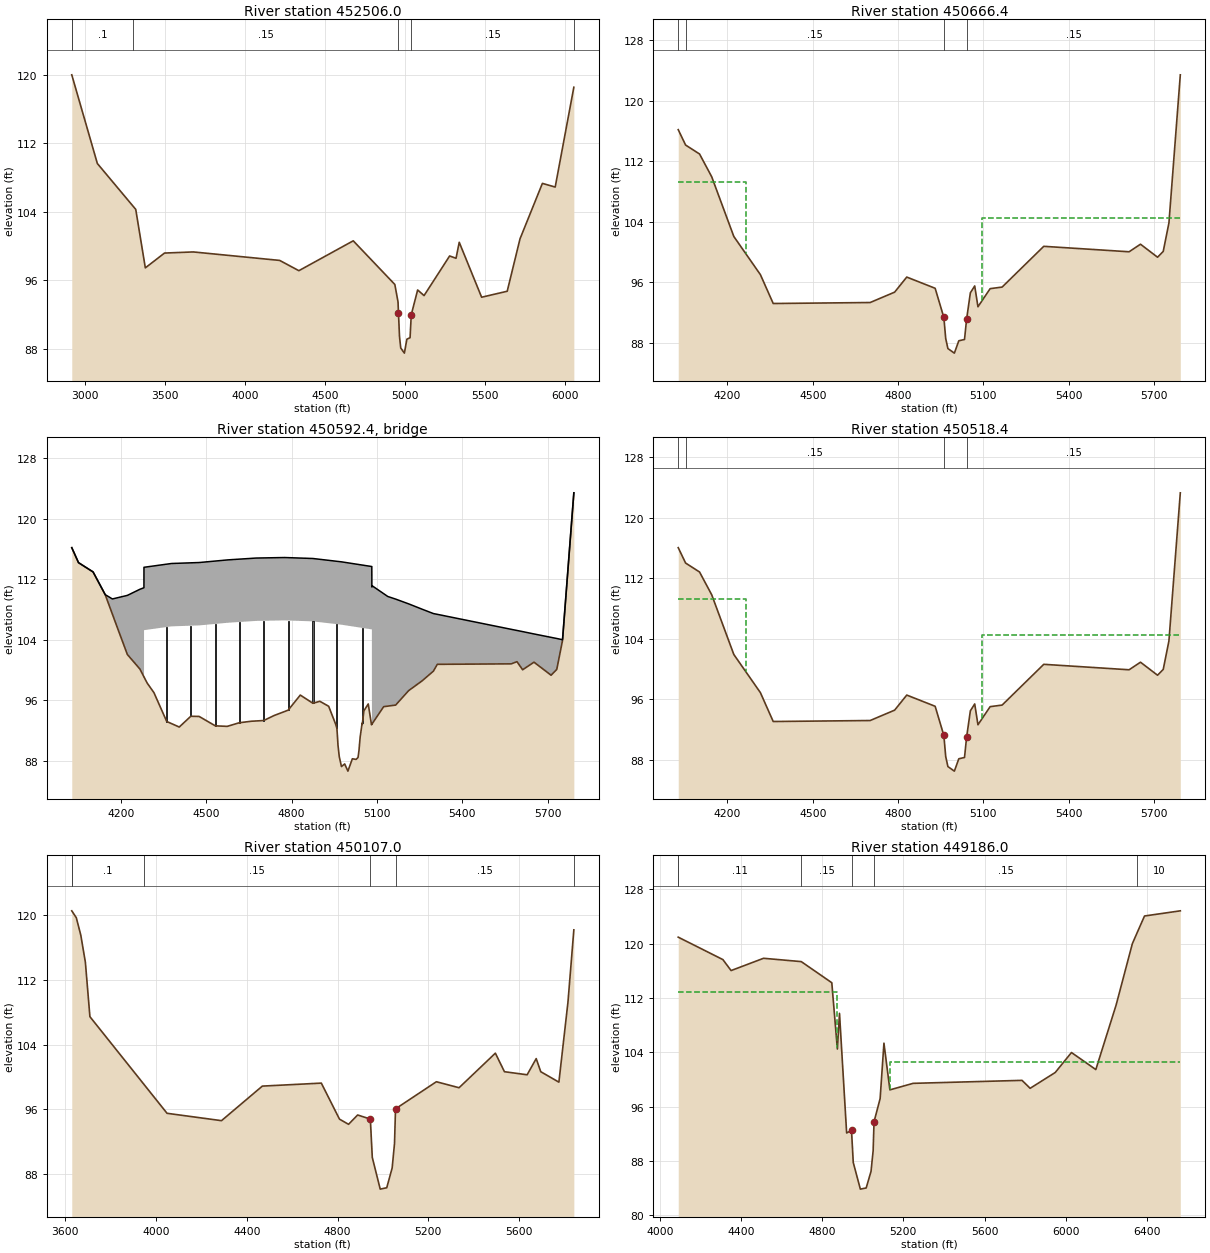
Type RM Length L Ch R = 1 ,452506.0,1839.6,1839.6,1839.6
BEGIN DESCRIPTION:
Cross Section Contentnea Creek 29.0
END DESCRIPTION:
#Sta/Elev= 30
  2917.3  119.98  3077.3  109.62  3302.1   104.6  3317.3  104.26  3377.3   97.43
  3497.3   99.16  3677.3   99.29  4217.3    98.3  4337.3    97.1  4677.3  100.59
  4937.3   95.49  4957.3   93.45    4960   92.18  4966.5   89.41  4974.3   88.07
    4997   87.47  5012.6    89.1  5032.6   89.27    5040   91.95    5080   94.85
    5120   94.19    5280   98.82    5320   98.55    5340  100.42    5480      94
    5640    94.7    5720  100.82    5860   107.3    5940  106.87  6056.6  118.53
#Mann= 6 , 1 , 0
  2917.3      .2       0  2917.3      .1       0  3302.1     .15       0
    4960    .065       0    5040     .15       0  6056.6      .2       0
Bank Sta=4960,5040
XS Rating Curve= 0 ,0
Exp/Cntr=0.5,0.3

Type RM Length L Ch R = 1 ,450666.4,148,148,148
BEGIN DESCRIPTION:
Upstream Section of Bridge/Culvert/Weir
END DESCRIPTION:
#Sta/Elev= 30
  4027.1  116.15    4053  114.12    4102  112.94  4144.7  109.94  4222.5  102.05
    4316   97.01    4361    93.2  4701.8   93.33  4787.9    94.7  4830.5   96.69
  4930.3   95.21  4960.9   91.36  4967.4   88.59  4975.2   87.25  4997.9   86.65
  5013.5   88.28  5033.5   88.45  5040.9   91.13  5054.1   94.61  5069.4   95.52
  5080.8   92.77  5123.6   95.16  5165.8   95.37  5312.2  100.75  5612.2  100.03
  5652.2  101.03  5712.2   99.31  5732.2  100.08  5752.2  103.85  5792.2  123.39
#Mann= 4 , 1 , 0
  4027.1      .1       0    4053     .15       0  4960.9    .065       0
  5040.9     .15       0
#XS Ineff= 2 , 0
       0    4265   109.3    5095       0   104.5
Permanent Ineff=
       F       F
Bank Sta=4960.9,5040.9
XS Rating Curve= 0 ,0
Exp/Cntr=0.5,0.3

Type RM Length L Ch R = 3 ,450592.4,,,
BEGIN DESCRIPTION:
US 264
Structure ID: WI_CONCR1A
END DESCRIPTION:
Bridge Culvert--1,0,-1,-1, 0
Deck Dist Width WeirC Skew NumUp NumDn MinLoCord MaxHiCord MaxSubmerge Is_Ogee
10,128,2.6,0, 39, 39, , , 0.95, 0, 1,1,,
  4027.1  4050.8    4102  4144.7  4169.9  4222.5  4266.7 4280.77 4280.88 4281.11
  4281.2  4377.4  4475.8  4576.4  4675.3  4775.5    4875  4975.2 5081.97 5082.08
 5082.19  5082.3  5085.1  5123.6  5137.9  5165.8  5211.6  5258.6  5298.5  5312.2
  5572.2  5592.2  5612.2  5652.2  5712.2  5732.2  5752.2  5752.6  5792.2
  116.15  114.17  112.95  109.95  109.38  109.85  110.66  110.86  113.56  113.56
  113.56  114.06  114.19  114.54  114.78  114.85  114.72  114.28  113.66  110.96
  110.96  110.97  111.07  110.08  109.71  109.36  108.73  108.03  107.45  107.35
  105.37  105.22  105.07  104.76  104.31  104.16     104  104.06  123.39
  116.15  114.17  112.94  109.94  107.37  102.05  100.12    99.1    99.1   99.08
  105.26  105.76  105.89  106.24  106.48  106.55  106.42  105.98  105.36  105.36
  105.36   92.85   93.01   95.16   95.23   95.37   97.28   98.56   99.85  100.75
  100.81   101.1  100.03  101.03   99.31  100.08  103.85  104.05  123.39
  4027.1  4050.8    4102  4144.7  4169.9  4222.5  4266.7 4280.77 4280.88 4281.11
  4281.2  4377.4  4475.8  4576.4  4675.3  4775.5    4875  4975.2 5081.97 5082.08
 5082.19  5082.3  5085.1  5123.6  5137.9  5165.8  5211.6  5258.6  5298.5  5312.2
  5572.2  5592.2  5612.2  5652.2  5712.2  5732.2  5752.2  5752.6  5792.2
  116.15  114.17  112.95  109.95  109.38  109.85  110.66  110.86  113.56  113.56
  113.56  114.06  114.19  114.54  114.78  114.85  114.72  114.28  113.66  110.96
  110.96  110.97  111.07  110.08  109.71  109.36  108.73  108.03  107.45  107.35
  105.37  105.22  105.07  104.76  104.31  104.16     104  104.06  123.39
  116.05  114.07  112.84  109.84  107.27  101.95  100.02      99      99   98.98
  105.16  105.66  105.79  106.14  106.38  106.45  106.32  105.88  105.26  105.26
  105.26   92.75   92.91   95.06   95.13   95.27   97.18   98.46   99.75  100.65
  100.71     101   99.93  100.93   99.21   99.98  103.75  103.95  123.29
Pier Skew, UpSta & Num, DnSta & Num=  ,4361, 2 ,4361, 2 , 0 , 0 , 0 ,,
       4       4
   92.17  106.68
       4       4
   92.07  106.58
Pier Skew, UpSta & Num, DnSta & Num=  ,4445.5, 2 ,4445.5, 2 , 0 , 0 , 0 ,,
       4       4
   92.82  106.85
       4       4
   92.72  106.75
Pier Skew, UpSta & Num, DnSta & Num=  ,4531.6, 2 ,4531.6, 2 , 0 , 0 , 0 ,,
       4       4
   91.63  107.09
       4       4
   91.53  106.99
Pier Skew, UpSta & Num, DnSta & Num=  ,4616.3, 2 ,4616.3, 2 , 0 , 0 , 0 ,,
       4       4
   92.02  107.34
       4       4
   91.92  107.24
Pier Skew, UpSta & Num, DnSta & Num=  ,4701.8, 2 ,4701.8, 2 , 0 , 0 , 0 ,,
       4       4
   92.33   107.5
       4       4
   92.23   107.4
Pier Skew, UpSta & Num, DnSta & Num=  ,4787.9, 2 ,4787.9, 2 , 0 , 0 , 0 ,,
       4       4
   93.67  107.53
       4       4
   93.57  107.43
Pier Skew, UpSta & Num, DnSta & Num=  ,4875, 2 ,4875, 2 , 0 , 0 , 0 ,,
       4       4
   94.63  107.42
       4       4
   94.53  107.32
Pier Skew, UpSta & Num, DnSta & Num=  ,4959.2, 2 ,4959.2, 2 , 0 , 0 , 0 ,,
     3.5     3.5
   90.33  107.06
     3.5     3.5
   90.23  106.96
Pier Skew, UpSta & Num, DnSta & Num=  ,5047.8, 2 ,5047.8, 2 , 0 , 0 , 0 ,,
     3.5     3.5
    91.5  106.59
     3.5     3.5
    91.4  106.49
Abutment Skew #Up #Dn= , 2 , 2
    4281  4292.3
  105.26   98.27
    4281  4292.3
  105.16   98.17
Abutment Skew #Up #Dn= , 2 , 2
  5069.4 5082.39
   95.52  105.36
  5069.4 5082.39
   95.42  105.26
BR Coef= 1 , 1 , 0 ,1.25, 0 ,,,0.8,0,2,0,
WSPro=,,,, 1 ,,,, 0 ,,,, 0 ,,,,-1 ,-1 ,-1 , 0 , 0 , 0 , 0 , 0
BR U #Sta/Elev= 88
  4027.1  116.15  4050.8  114.17    4053  114.12  4072.8  113.64    4102  112.94
  4122.1  111.53  4144.7  109.94  4169.9  107.37  4186.6  105.67  4218.4  102.46
  4222.5  102.05  4266.7  100.12  4278.2   99.29 4280.77    99.1 4280.88    99.1
 4280.99   99.09 4281.11   99.08  4281.2   99.07  4292.2   98.28  4292.3   98.27
    4316   97.01    4361    93.2  4377.4   92.93    4405   92.47  4445.5   93.89
  4474.7   93.87  4475.8   93.85  4531.6   92.63  4573.3   92.56  4576.4   92.59
  4616.3   93.04  4659.6   93.24  4675.3   93.27  4701.8   93.33    4739      94
  4775.5   94.52  4787.9    94.7  4830.5   96.69  4874.9   95.61    4875   95.61
  4899.2   95.87  4930.3   95.21  4955.2   92.81  4959.2    92.3  4960.9   91.36
  4963.1   90.06  4967.4   88.59  4972.7   87.68  4975.2   87.25  4986.5    87.6
  4997.9   86.65  5013.5   88.28  5026.8    88.2  5033.5   88.45  5036.9    89.4
  5040.9   91.13  5047.8   92.96  5048.4   92.82  5054.1   94.61  5069.3   95.51
  5069.4   95.52  5072.7   94.72  5080.8   92.77 5081.86   92.83 5081.97   92.84
 5082.08   92.84 5082.19   92.85  5082.3   92.85  5085.1   93.01  5123.6   95.16
  5137.9   95.23  5165.8   95.37    5190   96.38  5211.6   97.28  5241.7    98.1
  5258.6   98.56  5294.8   99.73  5298.5   99.85  5312.2  100.75  5572.2  100.81
  5592.2   101.1  5612.2  100.03  5652.2  101.03  5712.2   99.31  5732.2  100.08
  5752.2  103.85  5752.6  104.05  5792.2  123.39
BR U #Mann= 4
  4027.1      .1    4053     .15  4960.9    .065  5040.9     .15
BR U Banks=4960.9,5040.9
BR D #Sta/Elev= 88
  4027.1  116.05  4050.8  114.07    4053  114.02  4072.8  113.54    4102  112.84
  4122.1  111.43  4144.7  109.84  4169.9  107.27  4186.6  105.57  4218.4  102.36
  4222.5  101.95  4266.7  100.02  4278.2   99.19 4280.77      99 4280.88      99
 4280.99   98.99 4281.11   98.98  4281.2   98.97  4292.2   98.18  4292.3   98.17
    4316   96.91    4361    93.1  4377.4   92.83    4405   92.37  4445.5   93.79
  4474.7   93.77  4475.8   93.75  4531.6   92.53  4573.3   92.46  4576.4   92.49
  4616.3   92.94  4659.6   93.14  4675.3   93.17  4701.8   93.23    4739    93.9
  4775.5   94.42  4787.9    94.6  4830.5   96.59  4874.9   95.51    4875   95.51
  4899.2   95.77  4930.3   95.11  4955.2   92.71  4959.2    92.2  4960.9   91.26
  4963.1   89.96  4967.4   88.49  4972.7   87.58  4975.2   87.15  4986.5    87.5
  4997.9   86.55  5013.5   88.18  5026.8    88.1  5033.5   88.35  5036.9    89.3
  5040.9   91.03  5047.8   92.86  5048.4   92.72  5054.1   94.51  5069.3   95.41
  5069.4   95.42  5072.7   94.62  5080.8   92.67 5081.86   92.73 5081.97   92.74
 5082.08   92.74 5082.19   92.75  5082.3   92.75  5085.1   92.91  5123.6   95.06
  5137.9   95.13  5165.8   95.27    5190   96.28  5211.6   97.18  5241.7      98
  5258.6   98.46  5294.8   99.63  5298.5   99.75  5312.2  100.65  5572.2  100.71
  5592.2     101  5612.2   99.93  5652.2  100.93  5712.2   99.21  5732.2   99.98
  5752.2  103.75  5752.6  103.95  5792.2  123.29
BR D #Mann= 4
  4027.1      .1    4053     .15  4960.9    .065  5040.9     .15
BR D Banks=4960.9,5040.9
BC Design=,, 0 ,, 0 ,,,,,,
BC HTab HWMax=123.39
BC Use User HTab Curves=0
BC User HTab FreeFlow(D)= 0

Type RM Length L Ch R = 1 ,450518.4,411.4,411.4,411.4
BEGIN DESCRIPTION:
Downstream Section of Bridge/Culvert/Weir
END DESCRIPTION:
#Sta/Elev= 30
  4027.1  116.04    4053  114.01    4102  112.83  4144.7  109.83  4222.5  101.94
    4316    96.9    4361   93.09  4701.8   93.22  4787.9   94.59  4830.5   96.58
  4930.3    95.1  4960.9   91.25  4967.4   88.48  4975.2   87.14  4997.9   86.54
  5013.5   88.17  5033.5   88.34  5040.9   91.02  5054.1    94.5  5069.4   95.41
  5080.8   92.66  5123.6   95.05  5165.8   95.26  5312.2  100.64  5612.2   99.92
  5652.2  100.92  5712.2    99.2  5732.2   99.97  5752.2  103.74  5792.2  123.28
#Mann= 4 , 1 , 0
  4027.1      .1       0    4053     .15       0  4960.9    .065       0
  5040.9     .15       0
#XS Ineff= 2 , 0
       0    4265   109.3    5095       0   104.5
Permanent Ineff=
       F       F
Bank Sta=4960.9,5040.9
XS Rating Curve= 0 ,0
Exp/Cntr=0.5,0.3

Type RM Length L Ch R = 1 ,450107.0,921,921,921
BEGIN DESCRIPTION:
Cross Section Contentnea Creek 28.2
END DESCRIPTION:
#Sta/Elev= 30
  3628.5  120.53  3648.5  119.68  3668.5   117.5  3688.5  114.17  3708.5  107.45
  3945.1   99.14  4048.5   95.51  4288.5    94.6  4468.5   98.87  4728.5   99.24
  4808.5   94.79  4848.5   94.15  4888.5    95.3  4944.5    94.8  4953.1   90.06
  4988.1   86.14  5016.8   86.31  5040.7   88.76  5051.1   91.79  5055.5   96.06
  5235.6   99.41  5335.6   98.67  5495.6  102.94  5535.6  100.65  5635.6  100.27
  5675.6  102.27  5695.6  100.65  5775.6   99.36  5815.6  109.25  5841.5  118.18
#Mann= 6 , 1 , 0
  3628.5      .2       0  3628.5      .1       0  3945.1     .15       0
  4944.5    .065       0  5055.5     .15       0  5841.5      .2       0
Bank Sta=4944.5,5055.5
XS Rating Curve= 0 ,0
Exp/Cntr=0.5,0.3

Type RM Length L Ch R = 1 ,449186.0,51,51,51
BEGIN DESCRIPTION:
Upstream Section of Bridge/Culvert/Weir
END DESCRIPTION:
#Sta/Elev= 30
  4090.4  120.96  4310.4  117.66  4350.9  116.04  4510.9  117.85  4696.7  117.36
  4847.3  114.25  4874.7  104.48  4885.2  109.74  4920.4   92.12  4944.4   92.51
    4953   87.77    4988   83.85  5016.7   84.02  5040.6   86.47    5051    89.5
  5055.4   93.77  5085.5   97.19  5104.2  105.35  5133.6   98.47  5248.1   99.43
  5784.8   99.87  5824.8    98.7  5948.5  101.03  6028.5  103.97  6148.5  101.46
  6248.5  110.96  6328.5     120    6353  121.67  6388.5  124.08  6564.9  124.84
#Mann= 6 , 1 , 0
  4090.4      .2       0  4090.4     .11       0  4696.7     .15       0
  4944.4    .065       0  5055.4     .15       0    6353      10       0
#XS Ineff= 2 , 0
       0    4875   112.9    5135       0   102.6
Permanent Ineff=
       F       F
Bank Sta=4944.4,5055.4
XS Rating Curve= 0 ,0
Exp/Cntr=0.5,0.3

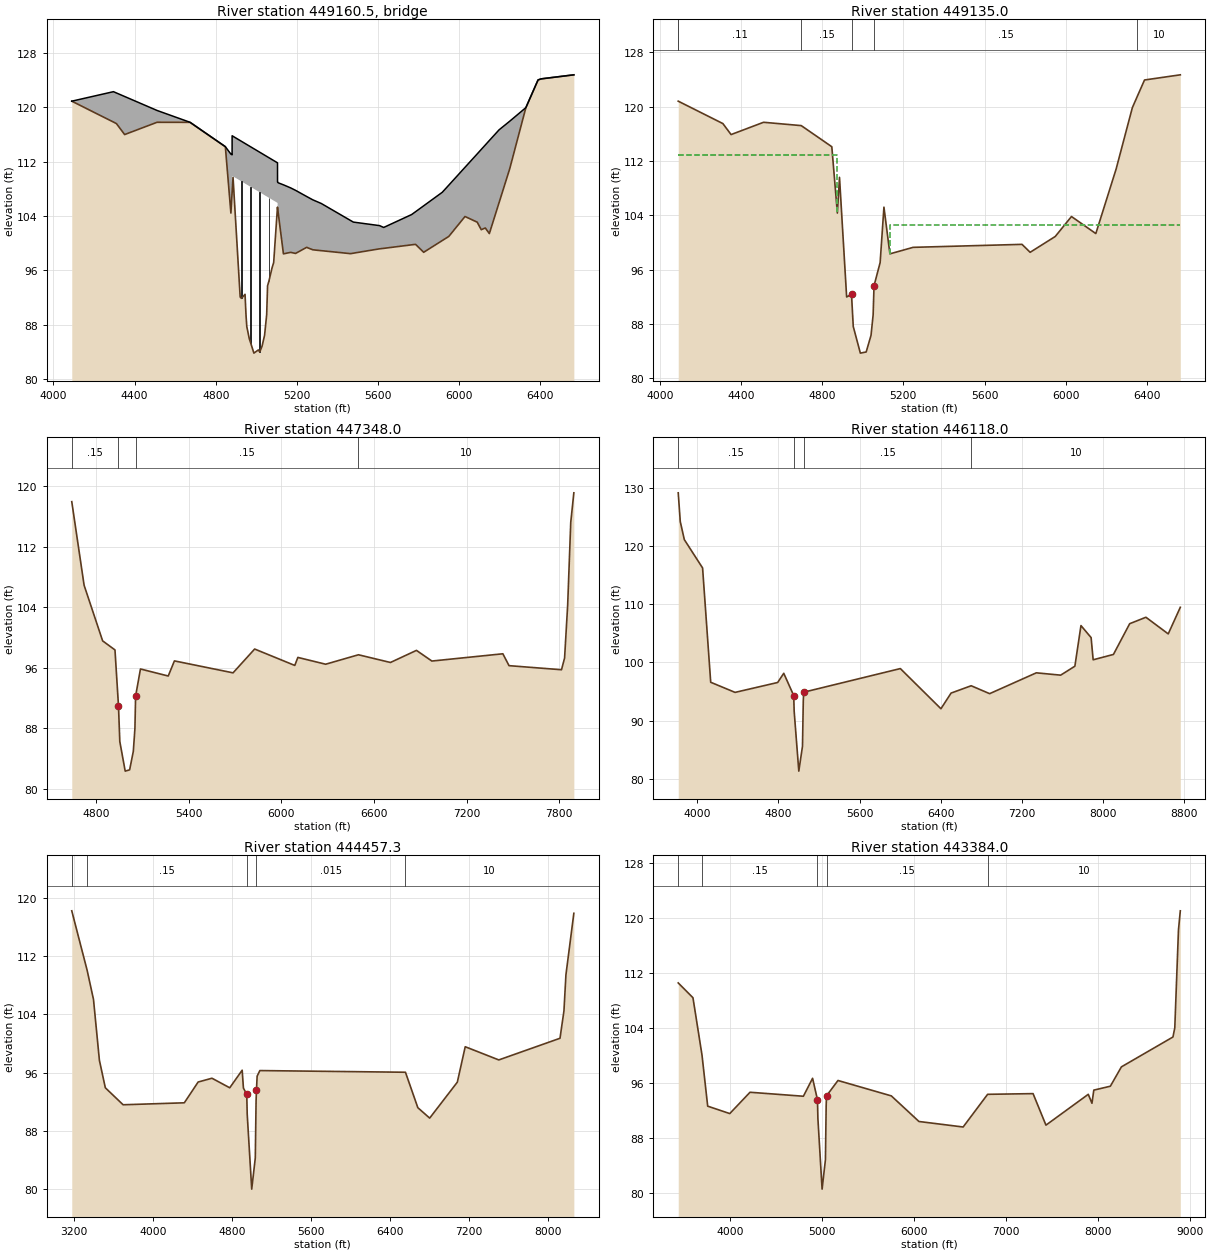
Type RM Length L Ch R = 3 ,449160.5,,,
BEGIN DESCRIPTION:
QUAKER RD (SR 1162)
Structure ID: WI_CONCR6
END DESCRIPTION:
Bridge Culvert--1,0,-1,-1, 0
Deck Dist Width WeirC Skew NumUp NumDn MinLoCord MaxHiCord MaxSubmerge Is_Ogee
10,31,2.6,0, 43, 43, , , 0.95, 0, 1,1,,
  4090.4  4295.9  4310.4  4350.9  4510.9  4673.3  4847.3  4874.7 4880.57 4880.68
 4880.91    4881 5104.37 5104.48 5104.59  5104.7  5107.7  5133.6  5169.7  5193.1
  5248.1  5278.3  5320.2  5464.8  5478.2  5607.6  5627.6  5765.3  5784.8  5824.8
  5916.4  5948.5  6028.5  6088.5  6108.5  6128.5  6148.5  6196.4  6248.5  6328.5
  6388.5  6404.1  6564.9
  120.92  122.32  122.13  121.61  119.55  117.81  114.22  113.12  113.02  115.82
  115.82  115.82  111.84  109.04  109.04  109.03   108.9   108.6  108.14  107.79
  106.88  106.39  105.85  103.34  103.11  102.59  102.32  104.22  104.64  105.51
   107.5  108.55  111.18  113.15  113.81  114.47  115.13   116.7  117.96  119.97
  124.05  124.21   124.8
  120.92  117.84  117.62     116  117.81   117.8  114.21  104.44  107.38  107.44
  107.55  109.92  105.94  105.94  105.94  105.19  104.49   98.43   98.65   98.49
   99.39   99.03    98.9   98.46   98.53   99.17   99.24   99.76   99.83   98.66
  100.39  100.99  103.93   103.1  101.99  102.24  101.42  105.97  110.92  119.96
  124.04   124.2   124.8
  4090.4  4295.9  4310.4  4350.9  4510.9  4673.3  4847.3  4874.7 4880.57 4880.68
 4880.91    4881 5104.37 5104.48 5104.59  5104.7  5107.7  5133.6  5169.7  5193.1
  5248.1  5278.3  5320.2  5464.8  5478.2  5607.6  5627.6  5765.3  5784.8  5824.8
  5916.4  5948.5  6028.5  6088.5  6108.5  6128.5  6148.5  6196.4  6248.5  6328.5
  6388.5  6404.1  6564.9
  120.92  122.32  122.13  121.61  119.55  117.81  114.22  113.12  113.02  115.82
  115.82  115.82  111.84  109.04  109.04  109.03   108.9   108.6  108.14  107.79
  106.88  106.39  105.85  103.34  103.11  102.59  102.32  104.22  104.64  105.51
   107.5  108.55  111.18  113.15  113.81  114.47  115.13   116.7  117.96  119.97
  124.05  124.21   124.8
  120.82  117.74  117.52   115.9  117.71   117.7  114.11  104.34  107.28  107.34
  107.45  109.82  105.84  105.84  105.84  105.09  104.39   98.33   98.55   98.39
   99.29   98.93    98.8   98.36   98.43   99.07   99.14   99.66   99.73   98.56
  100.29  100.89  103.83     103  101.89  102.14  101.32  105.87  110.82  119.86
  123.94   124.1   124.7
Pier Skew, UpSta & Num, DnSta & Num=  ,4926.6, 2 ,4926.6, 2 , 0 , 0 , 0 ,,
     2.7     2.7
   90.92  110.12
     2.7     2.7
   90.82  110.02
Pier Skew, UpSta & Num, DnSta & Num=  ,4971.9, 2 ,4971.9, 2 , 0 , 0 , 0 ,,
     2.7     2.7
   84.21  109.32
     2.7     2.7
   84.11  109.22
Pier Skew, UpSta & Num, DnSta & Num=  ,5016.7, 2 ,5016.7, 2 , 0 , 0 , 0 ,,
     2.7     2.7
   83.04  108.52
     2.7     2.7
   82.94  108.42
Pier Skew, UpSta & Num, DnSta & Num=  ,5061.9, 2 ,5061.9, 2 , 0 , 0 , 0 ,,
     2.7     2.7
   93.25  107.71
     2.7     2.7
   93.15  107.61
Abutment Skew #Up #Dn= , 2 , 2
  4880.8  4920.4
  109.92   92.08
  4880.8  4920.4
  109.82   91.98
Abutment Skew #Up #Dn= , 2 , 2
  5085.6 5104.79
   97.19  105.94
  5085.6 5104.79
   97.09  105.84
BR Coef= 1 , 1 , 0 ,1.25, 0 ,,,0.8,0,2,0,
WSPro=,,,, 1 ,,,, 0 ,,,, 0 ,,,,-1 ,-1 ,-1 , 0 , 0 , 0 , 0 , 0
BR U #Sta/Elev= 79
  4090.4  120.92  4295.9  117.84  4310.4  117.62  4350.9     116  4510.9  117.81
  4673.3   117.8  4681.5  117.63  4696.7  117.32  4735.7  116.51  4786.6  115.46
  4835.7  114.45  4847.3  114.21  4874.7  104.44  4880.1  107.15 4880.57  107.38
 4880.68  107.44 4880.79  107.49 4880.91  107.55    4881   107.6  4885.2   109.7
  4920.3   92.13  4920.4   92.08  4926.6   91.88  4944.4   92.47    4949    89.5
    4953   87.73  4965.6   85.89  4971.9   85.34    4988   83.81  5010.1   84.28
  5016.7   83.98  5028.3   84.83  5040.6   86.43    5051   89.46  5055.4   93.73
  5061.9   94.39  5077.5   96.37  5085.5   97.15  5085.6   97.19  5104.2  105.31
 5104.26   105.3 5104.37  105.27 5104.48  105.24 5104.59  105.22  5104.7  105.19
  5107.7  104.49  5133.6   98.43  5159.3   98.59  5169.7   98.65  5193.1   98.49
  5214.1   98.83  5248.1   99.39  5268.8   99.14  5278.3   99.03  5320.2    98.9
  5464.8   98.46  5478.2   98.53  5604.8   99.16  5607.6   99.17  5627.6   99.24
  5765.3   99.76  5784.8   99.83  5824.8   98.66  5916.4  100.39  5948.5  100.99
  6028.5  103.93  6088.5   103.1  6108.5  101.99  6128.5  102.24  6148.5  101.42
  6196.4  105.97  6248.5  110.92  6328.5  119.96    6353  121.63  6388.5  124.04
  6404.1   124.2  6516.4  124.62  6556.4  124.77  6564.9   124.8
BR U #Mann= 6
  4090.4      .2  4090.4     .11  4696.7     .15  4944.4    .065  5055.4     .15
    6353      10
BR U Banks=4944.4,5055.4
BR D #Sta/Elev= 79
  4090.4  120.82  4295.9  117.74  4310.4  117.52  4350.9   115.9  4510.9  117.71
  4673.3   117.7  4681.5  117.53  4696.7  117.22  4735.7  116.41  4786.6  115.36
  4835.7  114.35  4847.3  114.11  4874.7  104.34  4880.1  107.05 4880.57  107.28
 4880.68  107.34 4880.79  107.39 4880.91  107.45    4881   107.5  4885.2   109.6
  4920.3   92.03  4920.4   91.98  4926.6   91.78  4944.4   92.37    4949    89.4
    4953   87.63  4965.6   85.79  4971.9   85.24    4988   83.71  5010.1   84.18
  5016.7   83.88  5028.3   84.73  5040.6   86.33    5051   89.36  5055.4   93.63
  5061.9   94.29  5077.5   96.27  5085.5   97.05  5085.6   97.09  5104.2  105.21
 5104.26   105.2 5104.37  105.17 5104.48  105.14 5104.59  105.12  5104.7  105.09
  5107.7  104.39  5133.6   98.33  5159.3   98.49  5169.7   98.55  5193.1   98.39
  5214.1   98.73  5248.1   99.29  5268.8   99.04  5278.3   98.93  5320.2    98.8
  5464.8   98.36  5478.2   98.43  5604.8   99.06  5607.6   99.07  5627.6   99.14
  5765.3   99.66  5784.8   99.73  5824.8   98.56  5916.4  100.29  5948.5  100.89
  6028.5  103.83  6088.5     103  6108.5  101.89  6128.5  102.14  6148.5  101.32
  6196.4  105.87  6248.5  110.82  6328.5  119.86    6353  121.53  6388.5  123.94
  6404.1   124.1  6516.4  124.52  6556.4  124.67  6564.9   124.7
BR D #Mann= 6
  4090.4      .2  4090.4     .11  4696.7     .15  4944.4    .065  5055.4     .15
    6353      10
BR D Banks=4944.4,5055.4
BC Design=,, 0 ,, 0 ,,,,,,
BC HTab HWMax=124.84
BC Use User HTab Curves=0
BC User HTab FreeFlow(D)= 0

Type RM Length L Ch R = 1 ,449135.0,1787,1787,1787
BEGIN DESCRIPTION:
Downstream Section of Bridge/Culvert/Weir
END DESCRIPTION:
#Sta/Elev= 30
  4090.4  120.81  4310.4  117.51  4350.9  115.89  4510.9   117.7  4696.7  117.21
  4847.3   114.1  4874.7  104.33  4885.2  109.59  4920.4   91.97  4944.4   92.36
    4953   87.62    4988    83.7  5016.7   83.87  5040.6   86.32    5051   89.35
  5055.4   93.62  5085.5   97.04  5104.2   105.2  5133.6   98.32  5248.1   99.28
  5784.8   99.72  5824.8   98.55  5948.5  100.88  6028.5  103.82  6148.5  101.31
  6248.5  110.81  6328.5  119.85    6353  121.52  6388.5  123.93  6564.9  124.69
#Mann= 6 , 1 , 0
  4090.4      .2       0  4090.4     .11       0  4696.7     .15       0
  4944.4    .065       0  5055.4     .15       0    6353      10       0
#XS Ineff= 2 , 0
       0    4875   112.9    5135       0   102.6
Permanent Ineff=
       F       F
Bank Sta=4944.4,5055.4
XS Rating Curve= 0 ,0
Exp/Cntr=0.5,0.3

Type RM Length L Ch R = 1 ,447348.0,1230,1230,1230
BEGIN DESCRIPTION:
Cross Section Contentnea Creek 28.0
END DESCRIPTION:
#Sta/Elev= 30
  4641.8  117.94  4721.8  106.88  4841.8   99.53  4921.8   98.33  4944.5   90.96
  4953.1   86.22  4988.1    82.3  5016.8   82.47  5040.7   84.92  5051.1   87.95
  5055.5   92.22    5087   95.81    5267   94.88    5307   96.88    5687    95.3
    5827   98.45    6087   96.28    6107   97.34    6287   96.44  6499.8   97.69
    6707   96.67  6875.5   98.27  6975.5   96.86  7435.5   97.82  7475.5   96.25
  7815.5   95.71  7835.5   97.26  7855.5  104.26  7875.5  115.22  7895.5  119.11
#Mann= 4 , 1 , 0
  4641.8     .15       0  4944.5    .065       0  5055.5     .15       0
  6499.8      10       0
Bank Sta=4944.5,5055.5
XS Rating Curve= 0 ,0
Exp/Cntr=0.3,0.1

Type RM Length L Ch R = 1 ,446118.0,1660.7,1660.7,1660.7
BEGIN DESCRIPTION:
Cross Section Contentnea Creek 27.0
END DESCRIPTION:
#Sta/Elev= 30
  3812.9  129.15  3832.9  124.21  3872.9  121.11  4052.9  116.24  4132.9    96.6
  4372.9   94.86  4792.9   96.56  4852.9   98.14  4950.8   94.32  4955.4   91.62
  5001.1   81.33  5037.4   85.61  5045.3   93.43  5049.2   94.89  6001.8   98.95
  6401.8   92.05  6501.8   94.74  6699.9      96  6881.8   94.64  7341.8   98.22
  7581.8   97.82  7721.8   99.36  7781.8  106.34  7881.8  104.27  7901.8  100.46
  8101.8  101.38  8261.8  106.66  8421.8  107.77  8641.8  104.91  8760.8  109.48
#Mann= 4 , 1 , 0
  3812.9     .15       0  4950.8    .065       0  5049.2     .15       0
  6699.9      10       0
Bank Sta=4950.8,5049.2
XS Rating Curve= 0 ,0
Exp/Cntr=0.3,0.1

Type RM Length L Ch R = 1 ,444457.3,1073.3,1073.3,1073.3
BEGIN DESCRIPTION:
Cross Section CCX_W149
Located At: OLD DAM DR
END DESCRIPTION:
#Sta/Elev= 30
  3179.4   118.2  3334.6  110.07  3399.4  106.05  3459.4   97.69  3519.4   93.93
  3699.4    91.6  4319.4   91.87  4459.4   94.72  4599.4   95.24  4779.4   93.93
  4905.4   96.34  4918.2   93.89  4951.8   93.02  4956.4   90.32  5002.1   80.03
  5038.4   84.31  5046.3   92.13  5050.2   93.59  5056.9   95.52  5084.6   96.29
  6559.4   96.06  6684.7    91.2  6804.7   89.77  7084.7    94.7  7164.7   99.56
  7504.7   97.75  8124.7  100.72  8164.7  104.48  8184.7  109.42  8264.9  117.86
#Mann= 5 , 1 , 0
  3179.4     .11       0  3334.6     .15       0  4951.8    .065       0
  5050.2    .015       0  6559.4      10       0
Bank Sta=4951.8,5050.2
XS Rating Curve= 0 ,0
Exp/Cntr=0.3,0.1

Type RM Length L Ch R = 1 ,443384.0,2219,2219,2219
BEGIN DESCRIPTION:
Cross Section Contentnea Creek 26.2
END DESCRIPTION:
#Sta/Elev= 30
  3437.8   110.6  3597.8  108.45    3696  100.12  3757.8   92.69  3997.8   91.61
  4217.8   94.71  4797.8   94.13  4897.8   96.74  4950.8   93.62  4955.4   90.92
  5001.1   80.63  5037.4   84.91  5045.3   92.73  5049.2   94.19  5173.7   96.42
  5753.7   94.18  6053.7   90.46  6533.7   89.66  6799.8   94.41  7293.7   94.51
  7433.7   89.93  7893.7   94.41  7933.7   93.11  7953.7   95.02  8133.7   95.59
  8253.7    98.4  8813.7  102.74  8833.7  104.07  8873.7   118.3  8893.7  121.08
#Mann= 5 , 1 , 0
  3437.8     .11       0    3696     .15       0  4950.8    .065       0
  5049.2     .15       0  6799.8      10       0
Bank Sta=4950.8,5049.2
XS Rating Curve= 0 ,0
Exp/Cntr=0.3,0.1

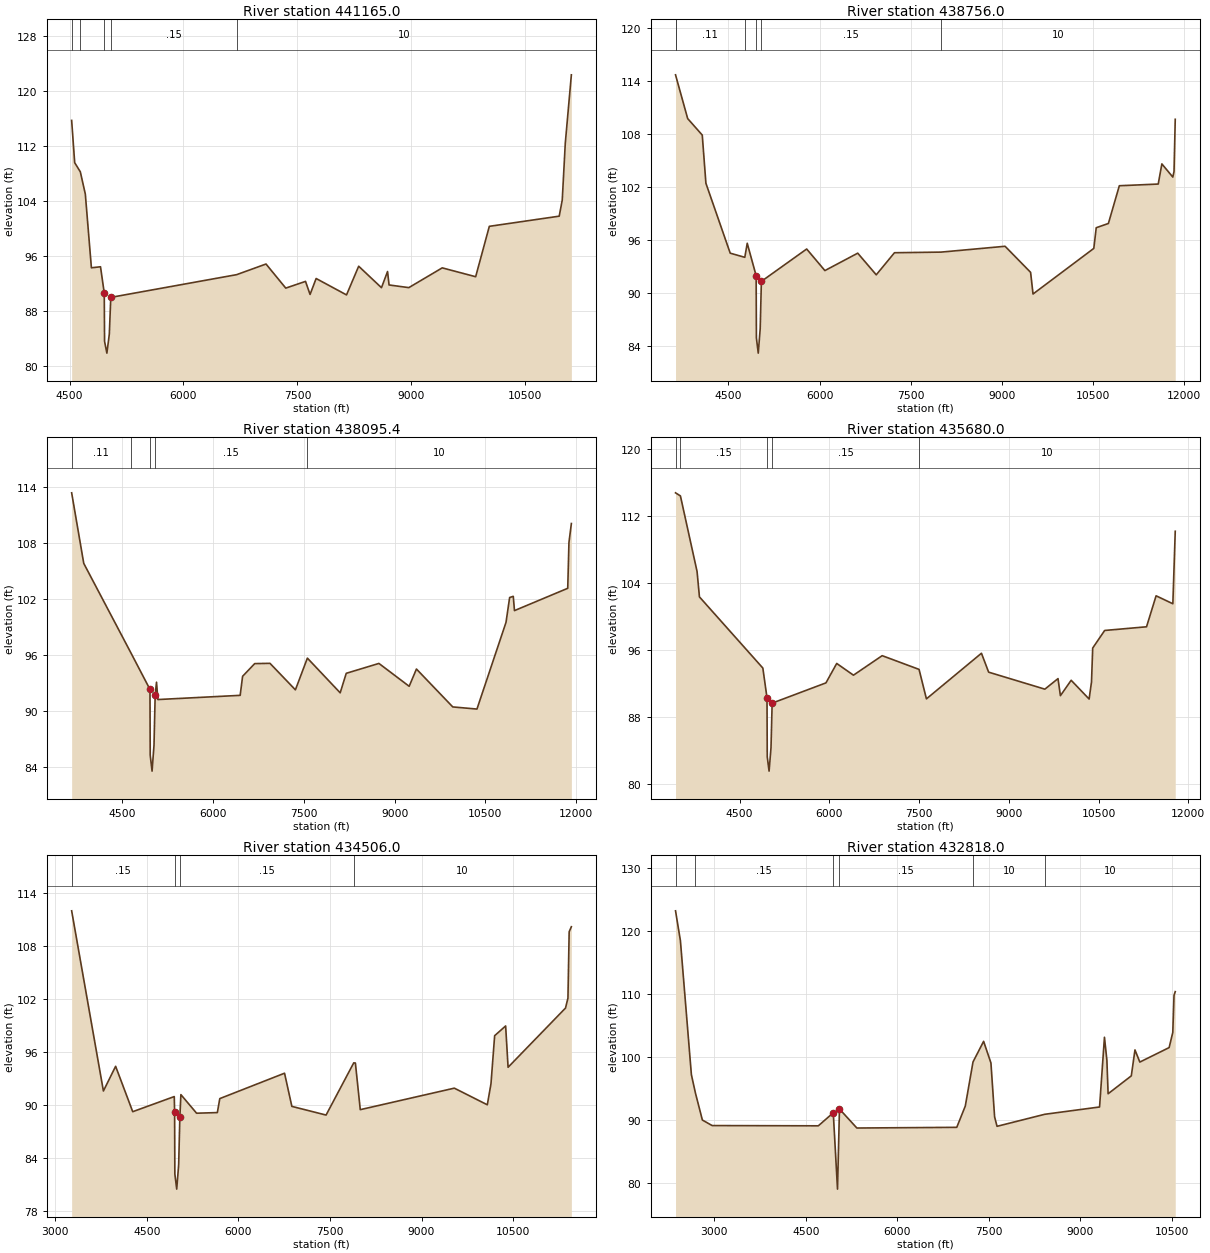
Type RM Length L Ch R = 1 ,441165.0,2409,2409,2409
BEGIN DESCRIPTION:
Cross Section Contentnea Creek 26.0
END DESCRIPTION:
#Sta/Elev= 30
  4527.8  115.76  4567.8   109.6    4642  108.27  4707.8  105.03  4787.8   94.29
  4907.8   94.44    4957   90.62  4961.1   83.57  4991.7   81.86  5023.8   84.64
    5043   89.98  6699.8   93.29  7086.5   94.84  7346.5   91.33  7606.5   92.31
  7666.5   90.41  7746.5   92.73  8146.5   90.34  8306.5   94.52  8606.5   91.39
  8686.5   93.75  8706.5   91.79  8966.5    91.4  9406.5   94.28  9846.5   92.99
 10026.5  100.33 10946.5  101.81 10986.5  104.16 11026.5  112.45 11106.5   122.4
#Mann= 5 , 1 , 0
  4527.8     .11       0    4642     .15       0    4957    .065       0
    5043     .15       0  6699.8      10       0
Bank Sta=4957,5043
XS Rating Curve= 0 ,0
Exp/Cntr=0.3,0.1

Type RM Length L Ch R = 1 ,438756.0,660.6,660.6,660.6
BEGIN DESCRIPTION:
Cross Section Contentnea Creek 25.7
END DESCRIPTION:
#Sta/Elev= 30
  3630.3  114.69  3830.3  109.74  4070.3  107.87  4130.3  102.42  4530.3   94.51
  4770.3   94.04  4810.3   95.63    4957   91.96  4961.1   84.91  4991.7    83.2
  5023.8   85.98    5043   91.32  5788.4   94.98  6088.4   92.54  6628.4   94.51
  6933.2   92.06  7233.2   94.56  7999.3   94.63  9053.2   95.29  9473.2   92.34
  9513.2   89.89 10513.2   95.05 10553.2   97.39 10753.2   97.87 10933.2  102.14
 11573.2  102.33 11633.2  104.61 11813.2  103.12 11833.2  103.76 11853.2  109.66
#Mann= 6 , 1 , 0
  3630.3      .2       0  3630.3     .11       0  4770.3     .15       0
    4957    .065       0    5043     .15       0  7999.3      10       0
Bank Sta=4957,5043
XS Rating Curve= 0 ,0
Exp/Cntr=0.3,0.1

Type RM Length L Ch R = 1 ,438095.4,2415.4,2415.4,2415.4
BEGIN DESCRIPTION:
Cross Section CCX_W148
Located At: CCX_W148
END DESCRIPTION:
#Sta/Elev= 30
  3664.3  113.39  3864.3  105.83  4637.9   96.31  4958.3   92.33  4962.4   85.28
    4993   83.57  5025.1   86.35  5044.3   91.69  5066.5    93.1    5089   91.24
    6449   91.69    6489   93.73    6689   95.09  6941.5   95.12  7361.5   92.28
  7559.3   95.68  8101.5   91.96  8201.5   94.05  8741.5   95.11  9241.5   92.66
  9361.5   94.51  9961.5   90.45 10361.5   90.22 10841.5   99.51 10901.5  102.17
 10961.5   102.3 10981.5  100.77 11861.5  103.16 11881.5  108.06 11921.5   110.1
#Mann= 5 , 1 , 0
  3664.3     .11       0  4637.9     .15       0  4958.3    .065       0
  5044.3     .15       0  7559.3      10       0
Bank Sta=4958.3,5044.3
XS Rating Curve= 0 ,0
Exp/Cntr=0.3,0.1

Type RM Length L Ch R = 1 ,435680.0,1174,1174,1174
BEGIN DESCRIPTION:
Cross Section Contentnea Creek 25.2
END DESCRIPTION:
#Sta/Elev= 30
  3427.5  114.73  3509.4  114.36  3787.5  105.34  3827.5   102.3  4887.5    93.8
    4957   90.25  4961.1    83.2  4991.7   81.49  5023.8   84.27    5043   89.61
  5942.6   92.03  6122.6   94.35  6402.6   92.95  6882.6   95.28  7499.5   93.64
  7622.6   90.12  8542.6   95.57  8662.6   93.31  9602.6   91.28  9822.6   92.54
  9862.6    90.5 10042.6   92.34 10342.6    90.1 10382.6   92.15 10402.6   96.19
 10602.6   98.29 11302.6   98.73 11462.6  102.43 11742.6  101.48 11782.6  110.14
#Mann= 5 , 1 , 0
  3427.5     .11       0  3509.4     .15       0    4957    .065       0
    5043     .15       0  7499.5      10       0
Bank Sta=4957,5043
XS Rating Curve= 0 ,0
Exp/Cntr=0.3,0.1

Type RM Length L Ch R = 1 ,434506.0,1688,1688,1688
BEGIN DESCRIPTION:
Cross Section Contentnea Creek 25.0
END DESCRIPTION:
#Sta/Elev= 30
  3271.5  111.93  3791.5   91.57  3991.5   94.36  4271.5   89.23  4951.5   90.94
    4957   89.24  4961.1   82.19  4991.7   80.48  5023.8   83.26    5043    88.6
    5060   91.16    5317   89.06    5657   89.13    5697   90.71    6757   93.58
    6877   89.83    7437   88.85    7890   94.75    7917   94.73    7997   89.46
    9537   91.89   10077   90.01   10137   92.39   10197   97.82   10377   98.92
   10417   94.25   11357  100.94   11397  102.06   11417  109.56 11453.1  110.13
#Mann= 4 , 1 , 0
  3271.5     .15       0    4957    .065       0    5043     .15       0
    7890      10       0
Bank Sta=4957,5043
XS Rating Curve= 0 ,0
Exp/Cntr=0.3,0.1

Type RM Length L Ch R = 1 ,432818.0,4974.6,4974.6,4974.6
BEGIN DESCRIPTION:
Cross Section Contentnea Creek 24.0
END DESCRIPTION:
#Sta/Elev= 30
  2364.4  123.21  2444.4  118.48  2624.4    97.2  2690.7   94.28  2804.4      90
  2964.4   89.12  4704.4   89.08  4949.2   91.15  5018.7   79.03  5050.8   91.75
  5335.9   88.73  6972.8   88.84  7112.8   92.22  7239.1   99.22  7412.8  102.49
  7532.8   99.06  7592.8    90.5  7632.8      89  8414.4   90.91  9312.8   92.07
  9392.8  103.14  9432.8    99.5  9452.8   94.17  9832.8   97.01  9892.8  101.13
  9972.8    99.2 10452.8   101.5 10512.8  103.92 10532.8   109.8 10552.8  110.38
#Mann= 6 , 1 , 0
  2364.4      .1       0  2690.7     .15       0  4949.2    .065       0
  5050.8     .15       0  7239.1      10       0  8414.4      10       0
Bank Sta=4949.2,5050.8
XS Rating Curve= 0 ,0
Exp/Cntr=0.5,0.3