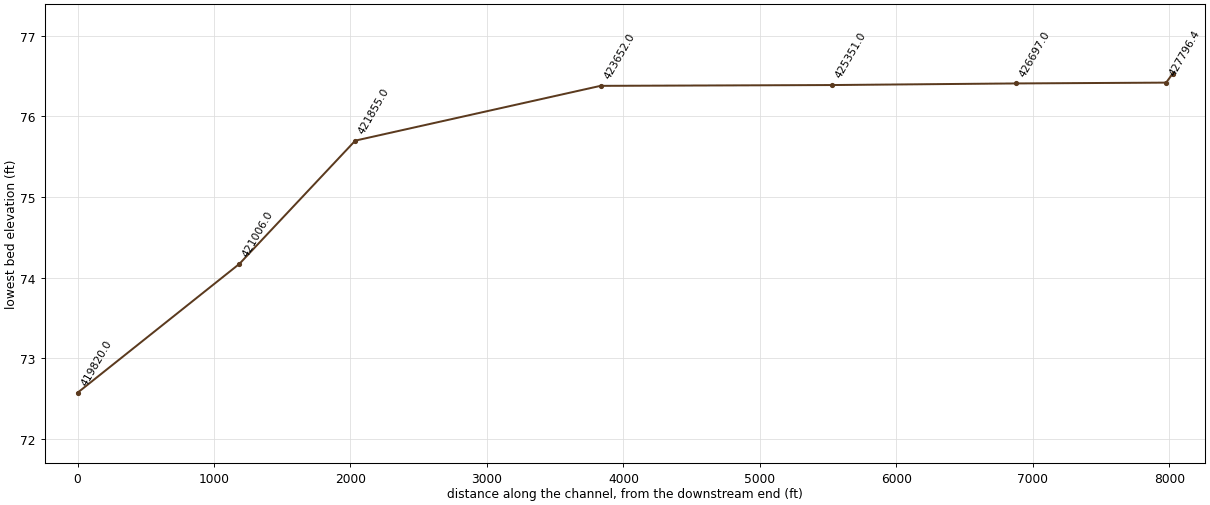
HEC-RAS study CONTENTNEA_FINAL.PRJ: Contentnea

--- CONTENTNEA_FINAL.g01 (geometry) --- (continued)

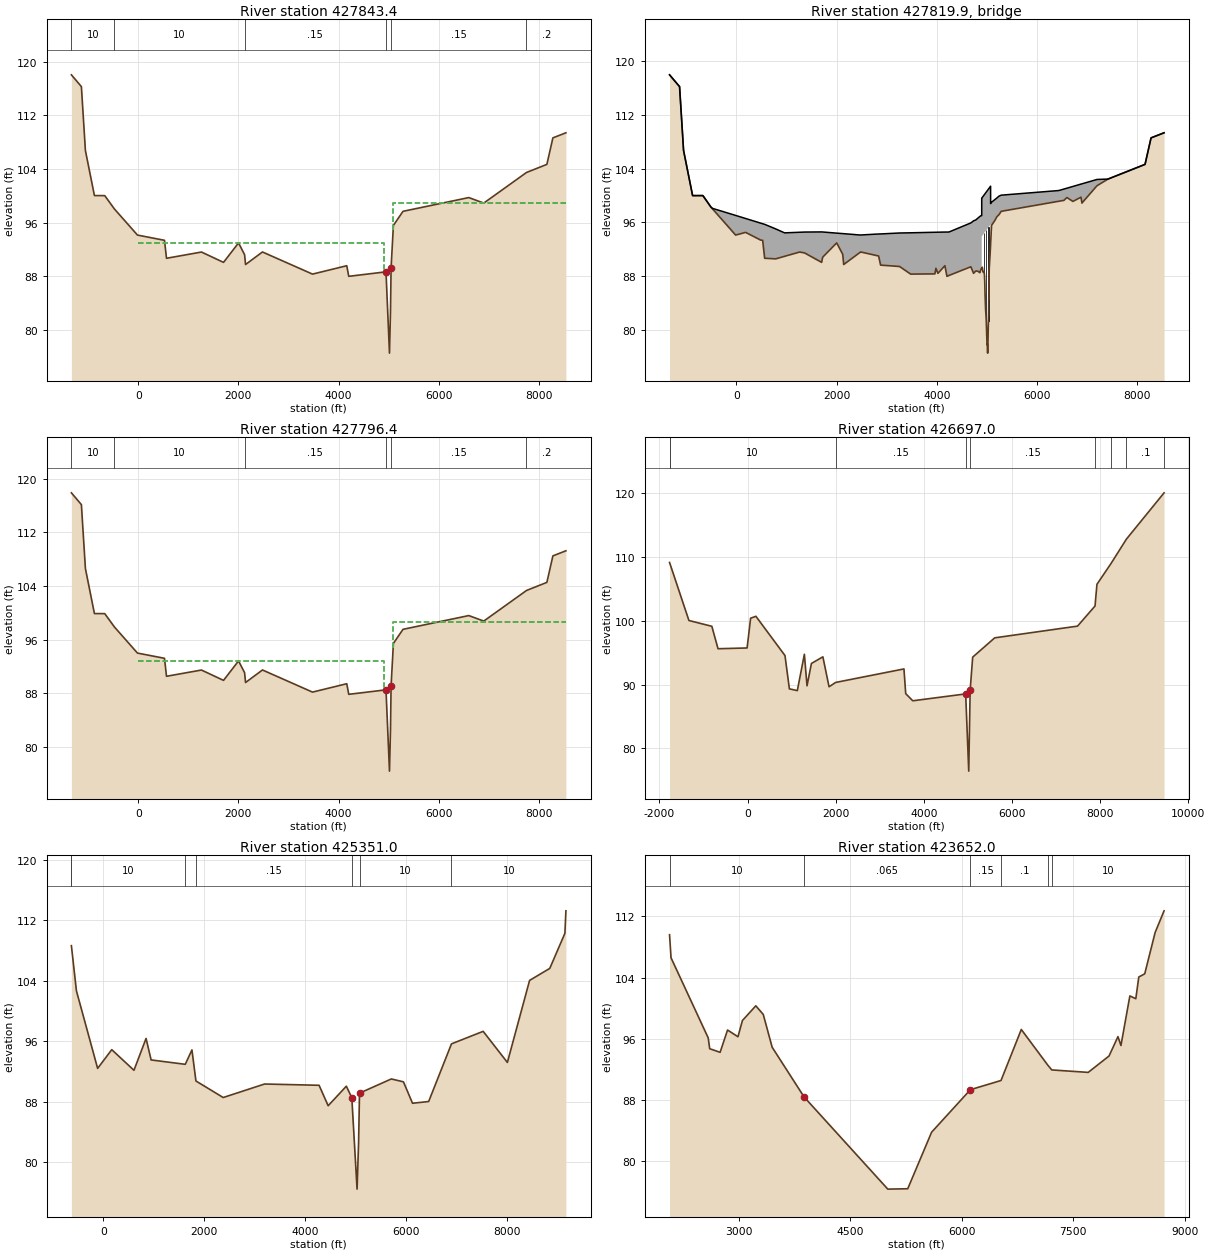
Type RM Length L Ch R = 1 ,427843.4,47,47,47
BEGIN DESCRIPTION:
Upstream Section of Bridge/Culvert/Weir
END DESCRIPTION:
#Sta/Elev= 30
 -1334.8  118.02 -1134.8  116.26 -1054.8  106.73  -874.8  100.02  -668.8  100.01
  -476.3   98.03   -15.6   94.13   524.4   93.35   564.4   90.67    1263    91.6
    1703   90.06    2003   92.96  2123.7   91.21    2143   89.74  2480.8   91.61
  3479.8   88.31  4163.9   89.56  4203.9   87.98  4947.5   88.65    5017   76.53
  5037.3   82.77  5049.1   89.25  5095.1   95.57  5287.2   97.67  6600.1   99.72
  6900.1    98.9  7752.9  103.46  8160.1  104.67  8280.1  108.62  8540.1  109.38
#Mann= 6 , 1 , 0
 -1334.8      10       0  -476.3      10       0  2123.7     .15       0
  4947.5    .065       0  5049.1     .15       0  7752.9      .2       0
#XS Ineff= 2 , 0
       0    4900    92.9    5090       0    98.9
Permanent Ineff=
       F       F
Bank Sta=4947.5,5049.1
XS Rating Curve= 0 ,0
Exp/Cntr=0.5,0.3

Type RM Length L Ch R = 3 ,427819.9,,,
BEGIN DESCRIPTION:
DOWNING RD (SR 1163)
Structure ID: WI_CONCR5
END DESCRIPTION:
Bridge Culvert--1,0,-1,-1, 0
Deck Dist Width WeirC Skew NumUp NumDn MinLoCord MaxHiCord MaxSubmerge Is_Ogee
10,27,2.6,0, 60, 60, , , 0.95, 0, 1,1,,
 -1334.8 -1134.8 -1054.8  -874.8  -668.8  -508.8  -476.3   -15.6   184.4   484.4
   524.4   564.4   784.4   961.7    1263    1363    1703    1723    2003    2123
    2143  2471.9  2839.8  2879.8  3259.8  3479.8  3963.9  3983.9  4023.9  4163.9
  4203.9    4246    4681  4736.7  4779.3  4861.6  4884.5 4898.57 4898.68 4898.91
    4899 5076.17 5076.28 5076.39  5076.5  5095.1  5203.1  5242.5  5287.2  6438.2
  6540.1  6600.1  6720.1  6880.1  6900.1  7200.1  7420.1  8160.1  8280.1  8540.1
  118.01  116.25  106.72  100.02  100.01    98.3    98.1   97.05   96.59    95.9
   95.81   95.72   95.04   94.45   94.54   94.57   94.59   94.58   94.41   94.34
   94.33   94.13   94.28   94.29   94.43   94.46   94.54   94.54   94.55   94.57
   94.57   94.58   95.93   96.25   96.37    96.9   97.01   97.02   99.62   99.62
   99.62  101.41   98.81   98.81   98.82   99.02   99.66   99.92  100.07  100.76
  100.98  101.11  101.37  101.72  101.76  102.41  102.47  104.66  108.61  109.37
  118.01  116.25  106.72  100.01     100   98.29   98.02   94.12   94.52   93.37
   93.34   90.66   90.57   90.95   91.59   91.45   90.05   90.82   92.95   91.25
   89.73   91.55      91   89.64   89.43    88.3   88.33   89.16   88.41   89.55
   87.97    88.1   89.39   88.41   88.76   88.51   89.03   89.19   89.19    89.2
   93.92   95.71   95.71   95.71   92.79   95.56   96.87   97.14   97.66   99.16
   99.29   99.71   99.14   99.76   98.89  101.47  102.47  104.66  108.61  109.37
 -1334.8 -1134.8 -1054.8  -874.8  -668.8  -508.8  -476.3   -15.6   184.4   484.4
   524.4   564.4   784.4   961.7    1263    1363    1703    1723    2003    2123
    2143  2471.9  2839.8  2879.8  3259.8  3479.8  3963.9  3983.9  4023.9  4163.9
  4203.9    4246    4681  4736.7  4779.3  4861.6  4884.5 4898.57 4898.68 4898.91
    4899 5076.17 5076.28 5076.39  5076.5  5095.1  5203.1  5242.5  5287.2  6438.2
  6540.1  6600.1  6720.1  6880.1  6900.1  7200.1  7420.1  8160.1  8280.1  8540.1
  118.01  116.25  106.72  100.02  100.01    98.3    98.1   97.05   96.59    95.9
   95.81   95.72   95.04   94.45   94.54   94.57   94.59   94.58   94.41   94.34
   94.33   94.13   94.28   94.29   94.43   94.46   94.54   94.54   94.55   94.57
   94.57   94.58   95.93   96.25   96.37    96.9   97.01   97.02   99.62   99.62
   99.62  101.41   98.81   98.81   98.82   99.02   99.66   99.92  100.07  100.76
  100.98  101.11  101.37  101.72  101.76  102.41  102.47  104.66  108.61  109.37
  117.94  116.18  106.65   99.94   99.93   98.22   97.95   94.05   94.45    93.3
   93.27   90.59    90.5   90.88   91.52   91.38   89.98   90.75   92.88   91.18
   89.66   91.48   90.93   89.57   89.36   88.23   88.26   89.09   88.34   89.48
    87.9   88.03   89.32   88.34   88.69   88.44   88.96   89.12   89.12   89.13
   93.85   95.64   95.64   95.64   92.72   95.49    96.8   97.07   97.59   99.09
   99.22   99.64   99.07   99.69   98.82   101.4   102.4  104.59  108.54   109.3
Pier Skew, UpSta & Num, DnSta & Num=  ,4942.4, 2 ,4942.4, 2 , 0 , 0 , 0 ,,
       2       2
   87.67   95.37
       2       2
    87.6    95.3
Pier Skew, UpSta & Num, DnSta & Num=  ,4988.2, 2 ,4988.2, 2 , 0 , 0 , 0 ,,
       2       2
    80.4   95.83
       2       2
   80.33   95.76
Pier Skew, UpSta & Num, DnSta & Num=  ,5033.2, 2 ,5033.2, 2 , 0 , 0 , 0 ,,
       2       2
   80.13   96.29
       2       2
   80.06   96.22
Abutment Skew #Up #Dn= , 2 , 2
  4898.8  4910.7
   93.92   89.32
  4898.8  4910.7
   93.85   89.25
Abutment Skew #Up #Dn= , 2 , 2
  5065.9 5076.59
   91.21   95.71
  5065.9 5076.59
   91.14   95.64
BR Coef= 1 , 1 , 0 ,1.25, 0 ,,,0.8,0,2,0,
WSPro=,,,, 1 ,,,, 0 ,,,, 0 ,,,,-1 ,-1 ,-1 , 0 , 0 , 0 , 0 , 0
BR U #Sta/Elev= 110
 -1334.8  118.01 -1134.8  116.25 -1054.8  106.72  -989.8   104.3  -874.8  100.01
  -868.8   99.98  -668.8     100  -508.8   98.29  -476.3   98.02   -15.6   94.12
   184.4   94.52   484.4   93.37   524.4   93.34   564.4   90.66   621.7   90.64
   784.4   90.57   961.7   90.95    1263   91.59    1363   91.45  1620.1   90.39
    1703   90.05    1723   90.82    2003   92.95    2123   91.25  2123.7    91.2
    2143   89.73  2471.9   91.55  2480.8    91.6  2839.8      91  2879.8   89.64
  3193.2   89.47  3259.8   89.43  3479.8    88.3  3963.9   88.33  3983.9   89.16
  4023.9   88.41  4163.9   89.55  4203.9   87.97    4246    88.1    4681   89.39
  4681.6   89.39  4734.4   88.45  4736.7   88.41  4779.3   88.76  4787.3   88.76
  4806.8   88.76  4831.7   88.68  4841.1   88.63  4861.6   88.51  4884.5   89.03
  4897.4   89.18 4898.57   89.19 4898.68   89.19 4898.79   89.19 4898.91    89.2
    4899    89.2  4910.6   89.33  4910.7   89.32  4922.4   88.69  4932.1   88.56
  4942.4   88.68  4947.5   88.64  4952.6   88.29  4959.2   87.21    4966   85.11
  4976.7   82.96  4983.6   82.17  4988.2   81.59  4991.5   80.96  4998.9   79.13
  5005.4   77.78  5009.7   77.93    5017   76.52  5022.8   77.93  5029.7   80.52
  5033.2   81.37  5037.3   82.76  5043.6   87.22  5047.4   88.43  5049.1   89.24
  5065.8    91.2  5065.9   91.21 5076.06   92.72 5076.17   92.74 5076.28   92.76
 5076.39   92.77  5076.5   92.79    5079   93.16  5095.1   95.56  5159.8   96.28
  5183.9   96.61  5203.1   96.87  5242.4   97.14  5242.5   97.14  5287.2   97.66
  5297.5   97.67  5380.4   97.78  6438.2   99.16  6540.1   99.29  6600.1   99.71
  6720.1   99.14  6880.1   99.76  6900.1   98.89  7200.1  101.47  7214.2  101.53
  7420.1  102.47  7752.9  103.45  8160.1  104.66  8280.1  108.61  8540.1  109.37
BR U #Mann= 6
 -1334.8      10  -476.3      10  2123.7     .15  4947.5    .065  5049.1     .15
  7752.9      .2
BR U Banks=4947.5,5049.1
BR D #Sta/Elev= 110
 -1334.8  117.94 -1134.8  116.18 -1054.8  106.65  -989.8  104.23  -874.8   99.94
  -868.8   99.91  -668.8   99.93  -508.8   98.22  -476.3   97.95   -15.6   94.05
   184.4   94.45   484.4    93.3   524.4   93.27   564.4   90.59   621.7   90.57
   784.4    90.5   961.7   90.88    1263   91.52    1363   91.38  1620.1   90.32
    1703   89.98    1723   90.75    2003   92.88    2123   91.18  2123.7   91.13
    2143   89.66  2471.9   91.48  2480.8   91.53  2839.8   90.93  2879.8   89.57
  3193.2    89.4  3259.8   89.36  3479.8   88.23  3963.9   88.26  3983.9   89.09
  4023.9   88.34  4163.9   89.48  4203.9    87.9    4246   88.03    4681   89.32
  4681.6   89.32  4734.4   88.38  4736.7   88.34  4779.3   88.69  4787.3   88.69
  4806.8   88.69  4831.7   88.61  4841.1   88.56  4861.6   88.44  4884.5   88.96
  4897.4   89.11 4898.57   89.12 4898.68   89.12 4898.79   89.12 4898.91   89.13
    4899   89.13  4910.6   89.26  4910.7   89.25  4922.4   88.62  4932.1   88.49
  4942.4   88.61  4947.5   88.57  4952.6   88.22  4959.2   87.14    4966   85.04
  4976.7   82.89  4983.6    82.1  4988.2   81.52  4991.5   80.89  4998.9   79.06
  5005.4   77.71  5009.7   77.86    5017   76.45  5022.8   77.86  5029.7   80.45
  5033.2    81.3  5037.3   82.69  5043.6   87.15  5047.4   88.36  5049.1   89.17
  5065.8   91.13  5065.9   91.14 5076.06   92.65 5076.17   92.67 5076.28   92.69
 5076.39    92.7  5076.5   92.72    5079   93.09  5095.1   95.49  5159.8   96.21
  5183.9   96.54  5203.1    96.8  5242.4   97.07  5242.5   97.07  5287.2   97.59
  5297.5    97.6  5380.4   97.71  6438.2   99.09  6540.1   99.22  6600.1   99.64
  6720.1   99.07  6880.1   99.69  6900.1   98.82  7200.1   101.4  7214.2  101.46
  7420.1   102.4  7752.9  103.38  8160.1  104.59  8280.1  108.54  8540.1   109.3
BR D #Mann= 6
 -1334.8      10  -476.3      10  2123.7     .15  4947.5    .065  5049.1     .15
  7752.9      .2
BR D Banks=4947.5,5049.1
BC Design=,, 0 ,, 0 ,,,,,,
BC HTab HWMax=118.02
BC Use User HTab Curves=0
BC User HTab FreeFlow(D)= 0

Type RM Length L Ch R = 1 ,427796.4,1099.4,1099.4,1099.4
BEGIN DESCRIPTION:
Downstream Section of Bridge/Culvert/Weir
END DESCRIPTION:
#Sta/Elev= 30
 -1334.8  117.91 -1134.8  116.15 -1054.8  106.62  -874.8   99.91  -668.8    99.9
  -476.3   97.92   -15.6   94.02   524.4   93.24   564.4   90.56    1263   91.49
    1703   89.95    2003   92.85  2123.7    91.1    2143   89.63  2480.8    91.5
  3479.8    88.2  4163.9   89.45  4203.9   87.87  4947.5   88.54    5017   76.42
  5037.3   82.66  5049.1   89.14  5095.1   95.46  5287.2   97.56  6600.1   99.61
  6900.1   98.79  7752.9  103.35  8160.1  104.56  8280.1  108.51  8540.1  109.27
#Mann= 6 , 1 , 0
 -1334.8      10       0  -476.3      10       0  2123.7     .15       0
  4947.5    .065       0  5049.1     .15       0  7752.9      .2       0
#XS Ineff= 2 , 0
       0    4900    92.9    5090       0    98.7
Permanent Ineff=
       F       F
Bank Sta=4947.5,5049.1
XS Rating Curve= 0 ,0
Exp/Cntr=0.5,0.3

Type RM Length L Ch R = 1 ,426697.0,1346,1346,1346
BEGIN DESCRIPTION:
Cross Section Contentnea Creek 23.0
END DESCRIPTION:
#Sta/Elev= 30
 -1771.6  109.16 -1331.6  100.05  -811.6   99.14  -671.6   95.62   -11.6   95.74
    68.4  100.41   188.4  100.71   848.4   94.55   948.4   89.32  1128.4   89.05
  1288.4   94.75  1348.4    89.8  1448.4   93.31  1708.4   94.35  1848.4   89.65
  1998.4   90.33  3548.4   92.45  3588.4   88.57  3748.4   87.45  4949.2   88.53
  5018.7   76.41  5050.8   89.13  5108.2    94.3  5608.2   97.33  7488.2   99.17
  7885.1  102.33  7928.2  105.73  8245.3  108.97  8597.8  112.83  9451.8  120.09
#Mann= 9 , 1 , 0
 -1771.6      10       0 -1771.6      10       0  1998.4     .15       0
  4949.2    .065       0  5050.8     .15       0  7885.1      .1       0
  8245.3     .15       0  8597.8      .1       0  9451.8      .2       0
Bank Sta=4949.2,5050.8
XS Rating Curve= 0 ,0
Exp/Cntr=0.3,0.1

Type RM Length L Ch R = 1 ,425351.0,1699,1699,1699
BEGIN DESCRIPTION:
Cross Section Contentnea Creek 22.0
END DESCRIPTION:
#Sta/Elev= 30
  -633.8  108.65  -533.8  102.66  -113.8   92.39   166.2   94.87   606.2   92.14
   846.2   96.36   946.2   93.51  1623.2   92.93  1755.3   94.84  1834.6   90.72
  2375.3   88.53  3195.3   90.32  4275.3   90.15  4455.3   87.44  4815.3   90.03
  4923.8   88.51 5028.05   76.39  5058.5   82.63  5076.2   89.11  5707.1   90.99
  5947.1   90.61  6127.1   87.77  6447.1      88  6899.2   95.64  7527.1    97.3
  8007.1   93.18  8447.1  104.05  8847.1  105.64  9147.1  110.29  9167.1  113.27
#Mann= 7 , 1 , 0
  -633.8      10       0  -633.8      10       0  1623.2      .1       0
  1834.6     .15       0  4923.8    .065       0  5076.2      10       0
  6899.2      10       0
Bank Sta=4923.8,5076.2
XS Rating Curve= 0 ,0
Exp/Cntr=0.3,0.1

Type RM Length L Ch R = 1 ,423652.0,1797,1797,1797
BEGIN DESCRIPTION:
Cross Section Contentnea Creek 21.0
END DESCRIPTION:
#Sta/Elev= 30
  2072.1  109.59  2092.1  106.58  2592.1   96.12  2612.1   94.71  2752.1   94.24
  2852.1   97.15  2992.1   96.27  3052.1   98.39  3232.1  100.31  3332.1   99.19
  3452.1    94.9  3882.4    88.4  5007.2   76.38  5275.2   76.43    5596   83.81
  6117.6   89.36  6529.4   90.56  6802.2   97.22  7160.7   92.54  7212.1   91.94
  7702.2   91.62  7982.2   93.76  8102.2   96.29  8142.2   95.13  8262.2   101.6
  8342.2  101.24  8382.2  104.07  8462.2  104.49  8602.2  109.89  8722.2  112.71
#Mann= 6 , 1 , 0
  2072.1      10       0  3882.4    .065       0  6117.6     .15       0
  6529.4      .1       0  7160.7      10       0  7212.1      10       0
Bank Sta=3882.4,6117.6
XS Rating Curve= 0 ,0
Exp/Cntr=0.3,0.1

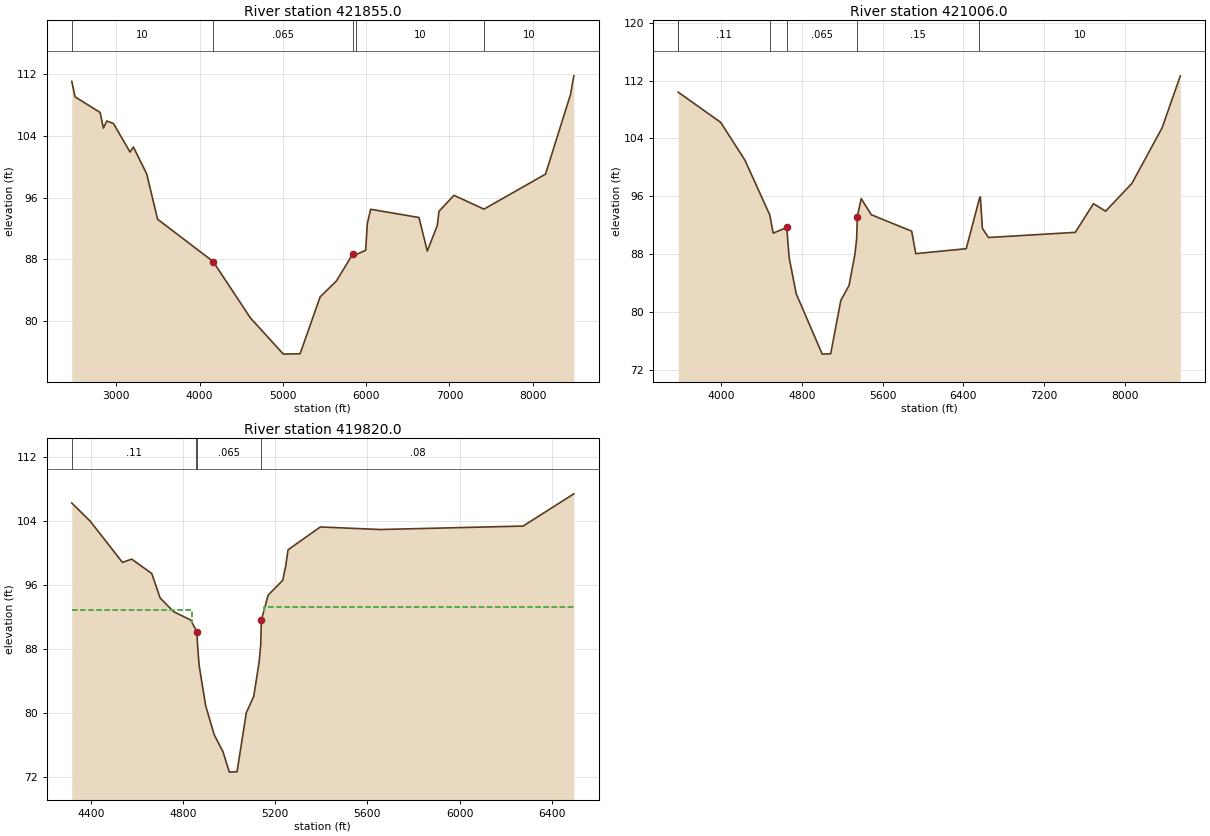
Type RM Length L Ch R = 1 ,421855.0,849,849,849
BEGIN DESCRIPTION:
Cross Section Contentnea Creek 20.0
END DESCRIPTION:
#Sta/Elev= 30
  2464.1  111.11  2504.1  109.09  2804.1  107.07  2844.1  105.03  2884.1  105.96
  2964.1  105.64  3164.1  101.93  3204.1  102.58  3364.1   99.09  3494.8   93.21
  4161.8   87.72  4609.4    80.4  5005.4    75.7  5206.4   75.75    5447   83.13
    5642   85.19  5838.2   88.68  5883.6   88.64  5993.9   89.18  6013.9   92.65
  6053.9    94.5  6633.9   93.43  6733.9   89.08  6853.9   92.39  6873.9   94.23
  7053.9   96.31  7414.1   94.52  8153.9   99.06  8453.9   109.4  8493.9  111.82
#Mann= 5 , 1 , 0
  2464.1      10       0  4161.8    .065       0  5838.2     .15       0
  5883.6      10       0  7414.1      10       0
Bank Sta=4161.8,5838.2
XS Rating Curve= 0 ,0
Exp/Cntr=0.3,0.1

Type RM Length L Ch R = 1 ,421006.0,1186,1186,1186
BEGIN DESCRIPTION:
Cross Section Contentnea Creek 19.0
END DESCRIPTION:
#Sta/Elev= 30
  3576.2   110.4  3996.2  106.23  4236.2  101.01    4483   93.41  4516.2    90.9
 4650.75   91.69  4674.5   87.52    4745    82.5 5002.25   74.17    5086   74.22
 5186.25    81.6  5267.5   83.66    5326   87.98 5343.25   90.15 5349.25   93.15
  5388.2   95.68  5488.2   93.45  5888.2   91.17  5928.2   88.07  6428.2   88.75
  6559.2   95.71  6568.2   95.92  6588.2   91.56  6648.2    90.3  7508.2   91.01
  7688.2   94.98  7808.2   93.94  8068.2   97.77  8368.2  105.48  8548.2  112.66
#Mann= 6 , 1 , 0
  3576.2      .2       0  3576.2     .11       0    4483     .15       0
 4650.75    .065       0 5349.25     .15       0  6559.2      10       0
Bank Sta=4650.75,5349.25
XS Rating Curve= 0 ,0
Exp/Cntr=0.5,0.3

Type RM Length L Ch R = 1 ,419820.0,176,176,176
BEGIN DESCRIPTION:
Upstream Section of Bridge/Culvert/Weir
END DESCRIPTION:
#Sta/Elev= 30
  4317.3   106.2  4397.3  103.93  4537.3   98.78  4577.3   99.19  4664.4   97.39
  4700.7   94.33  4758.6   92.64  4833.6   91.57  4856.6    90.3  4860.3   90.09
  4862.7   88.59  4869.8   85.92    4898    80.9  4934.9   77.27  4973.8   75.08
  5000.9   72.57  5034.4   72.62  5074.5      80    5107   82.06  5130.4   86.38
  5137.3   88.55  5139.7   91.55  5169.2   94.69  5232.5   96.54  5245.8   98.38
  5255.5  100.35  5395.5  103.21  5655.5  102.89  6275.5  103.32  6495.5  107.35
#Mann= 4 , 1 , 0
  4317.3     .11       0  4856.6     .15       0  4860.3    .065       0
  5139.7     .08       0
#XS Ineff= 2 , 0
       0    4840    92.8    5150       0    93.2
Permanent Ineff=
       F       F
Bank Sta=4860.3,5139.7
XS Rating Curve= 0 ,0
Exp/Cntr=0.5,0.3