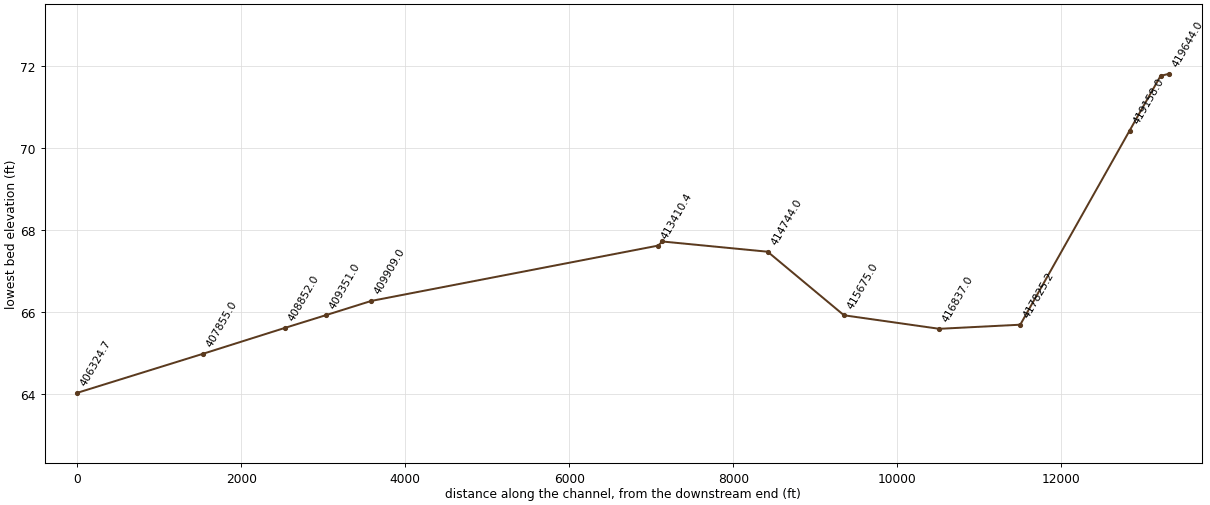
HEC-RAS study CONTENTNEA_FINAL.PRJ: Contentnea

--- CONTENTNEA_FINAL.g01 (geometry) --- (continued)

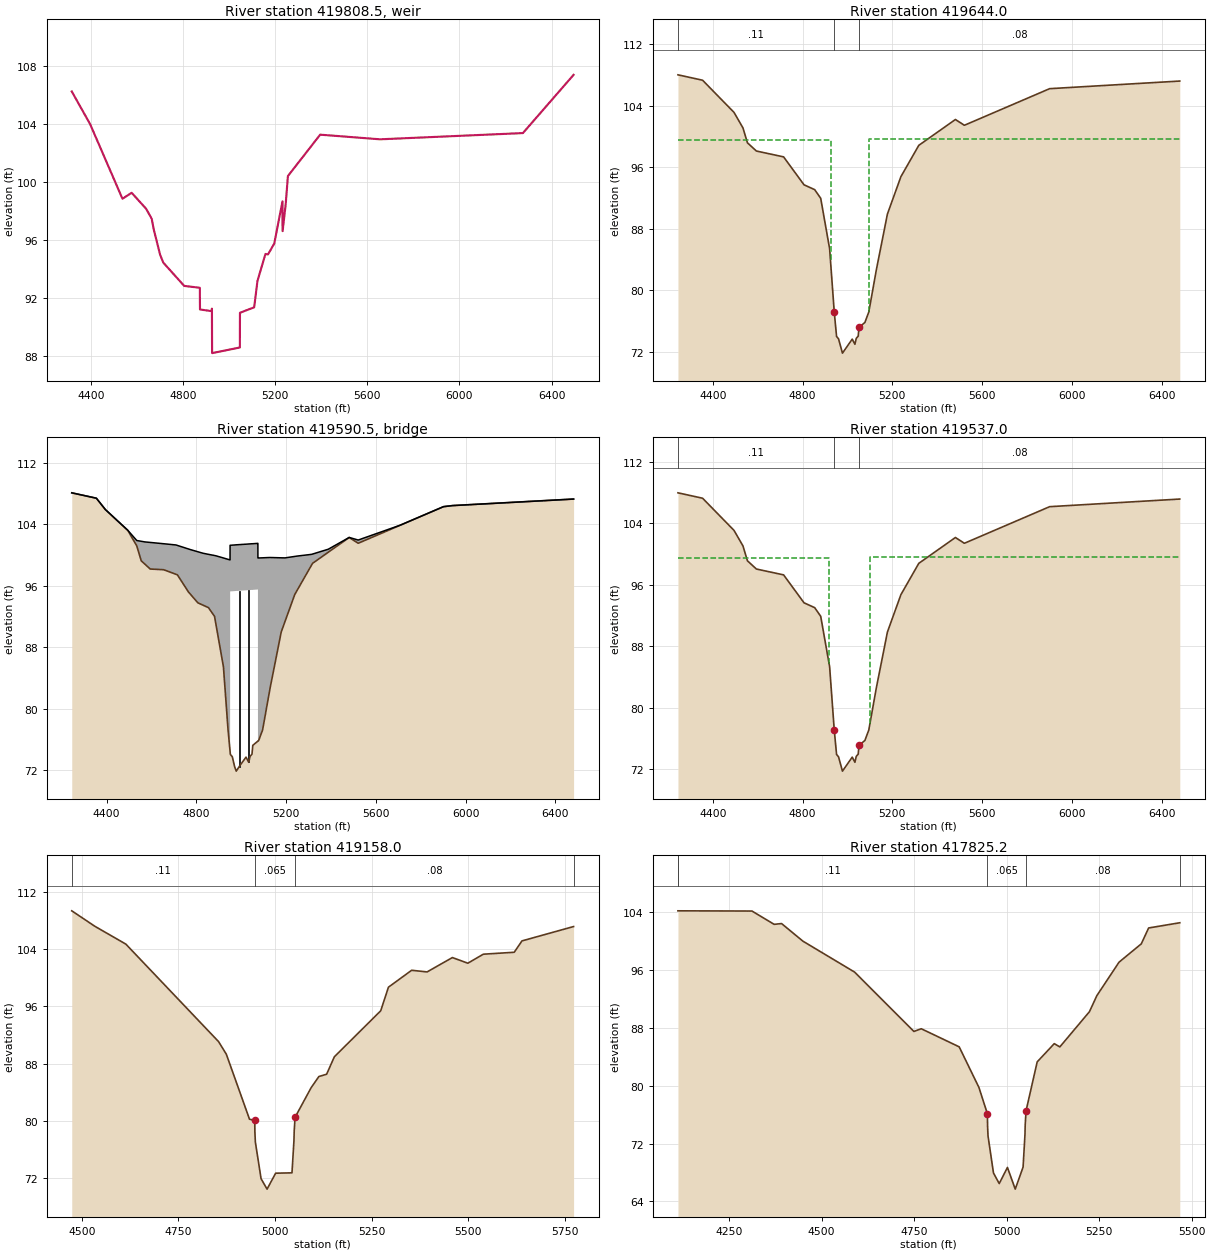
Type RM Length L Ch R = 5 ,419808.5,,,
BEGIN DESCRIPTION:
WIGGINS MILL DAM
Structure ID: WI_CONCR4
END DESCRIPTION:
IW Pilot Flow=0
#Inline Weir SE= 30
  4317.3  106.27  4397.3     104  4537.3   98.85  4577.3   99.26  4640.4   98.15
  4664.4   97.46  4673.4   96.71  4700.7   94.98  4714.6   94.43  4805.3   92.82
  4873.2   92.69  4873.9   91.19  4925.6   91.07  4925.7   91.25  4926.4   88.17
    5047   88.56  5047.4   90.96  5109.1   91.34  5123.4   93.17  5158.1   95.03
  5169.2      95  5196.3   95.75  5231.9   98.67  5232.5   96.61  5245.8   98.45
  5255.5  100.42  5395.5  103.28  5655.5  102.96  6275.5  103.39  6495.5  107.42
IW Dist,WD,Coef,Skew,MaxSub,Min_El,Is_Ogee,SpillHt,DesHd
10,3,3,0,0.95,, 0 ,,,1,1,

Type RM Length L Ch R = 1 ,419644.0,107,107,107
BEGIN DESCRIPTION:
Upstream Section of Bridge/Culvert/Weir
END DESCRIPTION:
#Sta/Elev= 30
  4244.9  108.01  4354.6  107.31  4494.6  103.13  4534.6  101.11  4554.6   99.17
  4594.6    98.1  4715.8   97.34  4806.7   93.71  4854.2   93.08  4881.2   91.95
  4920.9   85.39  4941.5   77.17  4951.8   73.99  4960.5   73.69  4978.1   71.82
  5021.6   73.64  5033.6   72.97  5039.6   73.74  5048.3   74.03  5051.7   75.17
  5078.1   75.81  5095.4   77.16  5129.5   82.71  5178.5   89.91  5238.6   94.77
  5318.3   98.84  5481.5   102.2  5521.5  101.45  5901.5  106.21  6481.5   107.2
#Mann= 3 , 1 , 0
  4244.9     .11       0  4941.5    .065       0  5051.7     .08       0
#XS Ineff= 2 , 0
       0    4925    99.5    5095       0    99.6
Permanent Ineff=
       F       F
Bank Sta=4941.5,5051.7
XS Rating Curve= 0 ,0
Exp/Cntr=0.5,0.3

Type RM Length L Ch R = 3 ,419590.5,,,
BEGIN DESCRIPTION:
HWY 301 (Ward Blvd)
Structure ID: WI_CONCR3
END DESCRIPTION:
Bridge Culvert--1,0,-1,-1, 0
Deck Dist Width WeirC Skew NumUp NumDn MinLoCord MaxHiCord MaxSubmerge Is_Ogee
10,87,2.6,0, 60, 60, , , 0.95, 0, 1,1,,
  4244.9  4354.6  4389.8  4394.6  4494.6  4534.6  4554.6  4569.8  4594.6  4654.6
  4709.6  4715.8  4765.1    4770  4806.7  4829.2  4854.2  4881.2  4887.6  4920.9
  4941.5 4950.37 4950.48 4950.59 4950.71  4950.8  4950.9  4951.8  4960.5  4970.6
  4978.1  4993.6  5021.6  5033.6  5039.6  5048.3  5051.7  5074.3 5074.36 5074.47
 5074.58 5074.69  5074.8  5078.1  5095.4  5126.3  5129.5  5178.5  5195.3  5238.6
  5253.2  5313.9  5318.3  5388.5  5481.5  5521.5  5708.5  5901.5  5941.5  6481.5
   108.1   107.4  106.11  105.93  103.23   101.9   101.8  101.72  101.65  101.48
  101.32  101.26   100.8  100.75  100.44  100.25   100.1   99.95   99.91   99.63
   99.45   99.38  101.28  101.28  101.28  101.28  101.28  101.28   101.3  101.32
  101.34  101.37  101.42  101.45  101.46  101.48  101.48  101.53  101.53  101.53
   99.63   99.63   99.63   99.63   99.65   99.69   99.69   99.65   99.64   99.83
   99.89   100.1  100.14  100.77   102.3  101.96  103.89   106.3  106.44  107.29
   108.1   107.4   106.1  105.92  103.22   101.2   99.26   98.85   98.19    98.1
    97.5   97.43    95.2   95.04    93.8    93.5   93.17   92.04   90.98   85.48
   77.26   74.52   74.49   74.45   74.42   95.28   95.28   95.28    95.3   95.32
   95.34   95.37   95.42   95.45   95.46   95.48   95.48   95.53   95.53   95.53
   95.53   95.53   75.82    75.9   77.25   82.28    82.8      90   91.36   94.86
   95.61   98.71   98.93  100.38  102.29  101.54  103.88   106.3  106.44  107.29
  4244.9  4354.6  4389.8  4394.6  4494.6  4534.6  4554.6  4569.8  4594.6  4654.6
  4709.6  4715.8  4765.1    4770  4806.7  4829.2  4854.2  4881.2  4887.6  4920.9
  4941.5 4950.37 4950.48 4950.59 4950.71  4950.8  4950.9  4951.8  4960.5  4970.6
  4978.1  4993.6  5021.6  5033.6  5039.6  5048.3  5051.7  5074.3 5074.36 5074.47
 5074.58 5074.69  5074.8  5078.1  5095.4  5126.3  5129.5  5178.5  5195.3  5238.6
  5253.2  5313.9  5318.3  5388.5  5481.5  5521.5  5708.5  5901.5  5941.5  6481.5
   108.1   107.4  106.11  105.93  103.23   101.9   101.8  101.72  101.65  101.48
  101.32  101.26   100.8  100.75  100.44  100.25   100.1   99.95   99.91   99.63
   99.45   99.38  101.28  101.28  101.28  101.28  101.28  101.28   101.3  101.32
  101.34  101.37  101.42  101.45  101.46  101.48  101.48  101.53  101.53  101.53
   99.63   99.63   99.63   99.63   99.65   99.69   99.69   99.65   99.64   99.83
   99.89   100.1  100.14  100.77   102.3  101.96  103.89   106.3  106.44  107.29
     108   107.3     106  105.82  103.12   101.1   99.16   98.75   98.09      98
    97.4   97.33    95.1   94.94    93.7    93.4   93.07   91.94   90.88   85.38
   77.16   74.42   74.39   74.35   74.32   95.18   95.18   95.18    95.2   95.22
   95.24   95.27   95.32   95.35   95.36   95.38   95.38   95.43   95.43   95.43
   95.43   95.43   75.72    75.8   77.15   82.18    82.7    89.9   91.26   94.76
   95.51   98.61   98.83  100.28  102.19  101.44  103.78   106.2  106.34  107.19
Pier Skew, UpSta & Num, DnSta & Num=  ,4991.1, 2 ,4991.1, 2 , 0 , 0 , 0 ,,
       4       4
    71.4   96.37
       4       4
    71.3   96.27
Pier Skew, UpSta & Num, DnSta & Num=  ,5033.6, 2 ,5033.6, 2 , 0 , 0 , 0 ,,
       4       4
   72.17   96.45
       4       4
   72.07   96.35
BR Coef= 1 , 1 , 0 ,1.25, 0 ,,,0.8,0,2,0,
WSPro=,,,, 1 ,,,, 0 ,,,, 0 ,,,,-1 ,-1 ,-1 , 0 , 0 , 0 , 0 , 0
BR U #Sta/Elev= 60
  4244.9   108.1  4354.6   107.4  4389.8   106.1  4394.6  105.92  4494.6  103.22
  4534.6   101.2  4554.6   99.26  4569.8   98.85  4594.6   98.19  4654.6    98.1
  4709.6    97.5  4715.8   97.43  4765.1    95.2    4770   95.04  4806.7    93.8
  4829.2    93.5  4854.2   93.17  4881.2   92.04  4887.6   90.98  4920.9   85.48
  4941.5   77.26 4950.37   74.52 4950.48   74.49 4950.59   74.45 4950.71   74.42
  4950.8   74.39  4950.9   74.36  4951.8   74.08  4960.5   73.78  4970.6   72.51
  4978.1   71.91  4993.6    72.6  5021.6   73.73  5033.6   73.06  5039.6   73.83
  5048.3   74.12  5051.7   75.26  5074.3   75.81 5074.36   75.81 5074.47   75.81
 5074.58   75.81 5074.69   75.82  5074.8   75.82  5078.1    75.9  5095.4   77.25
  5126.3   82.28  5129.5    82.8  5178.5      90  5195.3   91.36  5238.6   94.86
  5253.2   95.61  5313.9   98.71  5318.3   98.93  5388.5  100.38  5481.5  102.29
  5521.5  101.54  5708.5  103.88  5901.5   106.3  5941.5  106.44  6481.5  107.29
BR U #Mann= 3
  4244.9     .11  4941.5    .065  5051.7     .08
BR U Banks=4941.5,5051.7
BR D #Sta/Elev= 60
  4244.9     108  4354.6   107.3  4389.8     106  4394.6  105.82  4494.6  103.12
  4534.6   101.1  4554.6   99.16  4569.8   98.75  4594.6   98.09  4654.6      98
  4709.6    97.4  4715.8   97.33  4765.1    95.1    4770   94.94  4806.7    93.7
  4829.2    93.4  4854.2   93.07  4881.2   91.94  4887.6   90.88  4920.9   85.38
  4941.5   77.16 4950.37   74.42 4950.48   74.39 4950.59   74.35 4950.71   74.32
  4950.8   74.29  4950.9   74.26  4951.8   73.98  4960.5   73.68  4970.6   72.41
  4978.1   71.81  4993.6    72.5  5021.6   73.63  5033.6   72.96  5039.6   73.73
  5048.3   74.02  5051.7   75.16  5074.3   75.71 5074.36   75.71 5074.47   75.71
 5074.58   75.71 5074.69   75.72  5074.8   75.72  5078.1    75.8  5095.4   77.15
  5126.3   82.18  5129.5    82.7  5178.5    89.9  5195.3   91.26  5238.6   94.76
  5253.2   95.51  5313.9   98.61  5318.3   98.83  5388.5  100.28  5481.5  102.19
  5521.5  101.44  5708.5  103.78  5901.5   106.2  5941.5  106.34  6481.5  107.19
BR D #Mann= 3
  4244.9     .11  4941.5    .065  5051.7     .08
BR D Banks=4941.5,5051.7
BC Design=,, 0 ,, 0 ,,,,,,
BC HTab HWMax=108.01
BC Use User HTab Curves=0
BC User HTab FreeFlow(D)= 0

Type RM Length L Ch R = 1 ,419537.0,379,379,379
BEGIN DESCRIPTION:
Downstream Section of Bridge/Culvert/Weir
END DESCRIPTION:
#Sta/Elev= 30
  4244.9  107.96  4354.6  107.26  4494.6  103.08  4534.6  101.06  4554.6   99.12
  4594.6   98.05  4715.8   97.29  4806.7   93.66  4854.2   93.03  4881.2    91.9
  4920.9   85.34  4941.5   77.12  4951.8   73.94  4960.5   73.64  4978.1   71.77
  5021.6   73.59  5033.6   72.92  5039.6   73.69  5048.3   73.98  5051.7   75.12
  5078.1   75.76  5095.4   77.11  5129.5   82.66  5178.5   89.86  5238.6   94.72
  5318.3   98.79  5481.5  102.15  5521.5   101.4  5901.5  106.16  6481.5  107.15
#Mann= 3 , 1 , 0
  4244.9     .11       0  4941.5    .065       0  5051.7     .08       0
#XS Ineff= 2 , 0
       0    4920    99.5    5100       0    99.6
Permanent Ineff=
       F       F
Bank Sta=4941.5,5051.7
XS Rating Curve= 0 ,0
Exp/Cntr=0.5,0.3

Type RM Length L Ch R = 1 ,419158.0,1332.8,1332.8,1332.8
BEGIN DESCRIPTION:
Cross Section Contentnea Creek 18.7
END DESCRIPTION:
#Sta/Elev= 30
  4474.3  109.38  4534.3  107.21  4614.3  104.72  4854.3   91.07  4874.3   89.31
  4934.3   80.21  4947.8   80.07  4948.2   78.46  4949.4   77.03  4964.2   71.89
  4979.7   70.43  5001.9   72.66  5044.2   72.71  5049.3   77.24  5049.9   78.54
  5052.2   80.49  5093.8   84.63  5113.8   86.19  5133.8   86.51  5153.8   88.95
  5273.8   95.39  5293.8   98.69  5353.8  101.06  5393.8  100.83  5459.3  102.84
  5499.3  102.05  5539.3  103.31  5619.3  103.58  5639.3  105.17  5772.9  107.18
#Mann= 4 , 1 , 0
  4474.3     .11       0  4947.8    .065       0  5052.2     .08       0
  5772.9      .2       0
Bank Sta=4947.8,5052.2
XS Rating Curve= 0 ,0
Exp/Cntr=0.3,0.1

Type RM Length L Ch R = 1 ,417825.2,988.2,988.2,988.2
BEGIN DESCRIPTION:
Cross Section WI_CCX146
Located At: WI_CCX146
END DESCRIPTION:
#Sta/Elev= 30
    4112  104.19    4312  104.16    4372  102.32    4392  102.43  4449.5     100
  4589.5   95.71  4749.5   87.51  4769.5   87.88  4871.9   85.38  4925.2   79.77
  4948.2   76.11  4948.6    74.5  4949.8   73.07  4964.6   67.93  4980.1   66.47
  5002.3    68.7  5023.4    65.7  5044.6   68.75  5049.7   73.28  5050.3   74.58
  5052.6   76.53  5082.7    83.3  5128.8   85.82  5143.9   85.37  5223.9   90.24
  5243.9   92.46  5303.9   97.09  5363.9   99.62  5383.9  101.82    5468  102.54
#Mann= 5 , 1 , 0
    4112      .2       0    4112     .11       0  4948.2    .065       0
  5052.6     .08       0    5468      .2       0
Bank Sta=4948.2,5052.6
XS Rating Curve= 0 ,0
Exp/Cntr=0.3,0.1

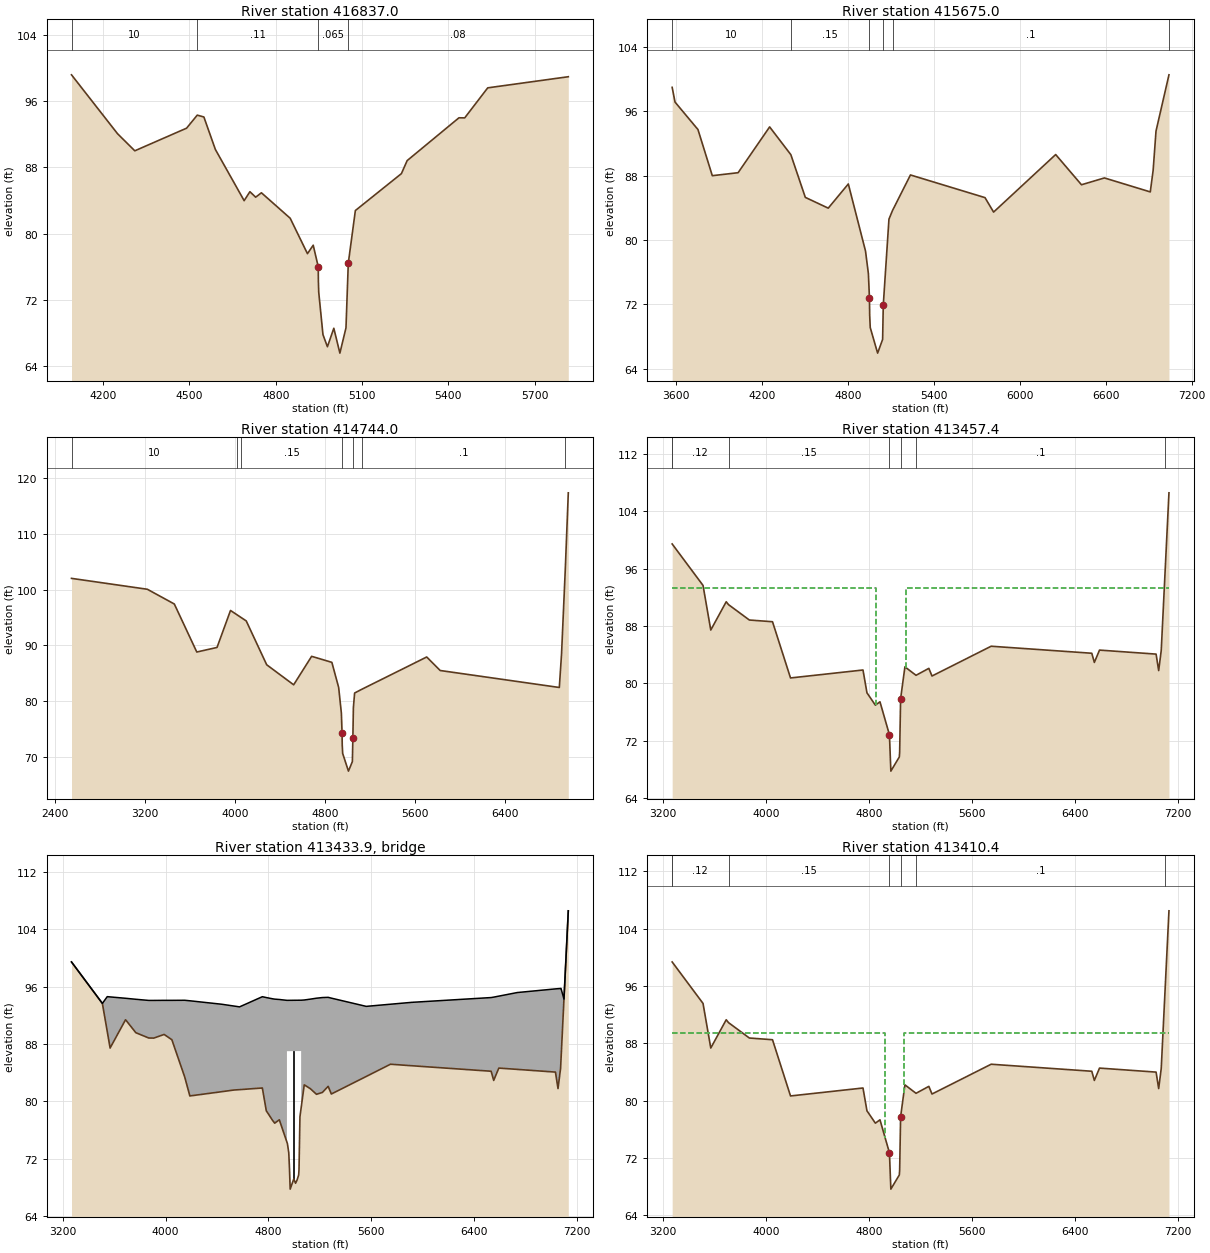
Type RM Length L Ch R = 1 ,416837.0,1162,1162,1162
BEGIN DESCRIPTION:
Cross Section Contentnea Creek 18.0
END DESCRIPTION:
#Sta/Elev= 30
  4090.3   99.15  4250.3   92.05  4310.3   89.99  4490.3   92.72  4527.3   94.29
  4550.3   94.07  4590.3   90.15  4690.3   83.98  4710.3   85.06  4730.3    84.4
  4750.3   84.93  4850.3   81.86  4910.3   77.59  4930.3   78.61  4947.8   76.01
  4948.2    74.4  4949.4   72.97  4964.2   67.83  4979.7   66.37  5001.9    68.6
    5023    65.6  5044.2   68.65  5052.2   76.43  5076.8   82.79  5236.8   87.24
  5256.8   88.81  5436.8   93.97  5456.8   93.96  5536.8   97.58  5816.8   98.92
#Mann= 4 , 1 , 0
  4090.3      10       0  4527.3     .11       0  4947.8    .065       0
  5052.2     .08       0
Bank Sta=4947.8,5052.2
XS Rating Curve= 0 ,0
Exp/Cntr=0.3,0.1

Type RM Length L Ch R = 1 ,415675.0,931,931,931
BEGIN DESCRIPTION:
Cross Section Contentnea Creek 17.0
END DESCRIPTION:
#Sta/Elev= 30
  3575.4      99  3595.4   97.17  3755.4   93.75  3855.4   88.01  4035.4   88.38
  4255.4   94.08  4403.5   90.62  4504.3   85.31  4664.3   83.97  4804.3   86.98
  4924.3   78.63  4944.3   75.82 4951.85   72.74 4953.35   70.64 4957.25   69.11
 5008.75   65.93 5043.65   67.64 5048.15    71.9  5087.8    82.6  5112.7   83.68
  5237.8    88.1  5757.8   85.28  5817.8   83.48  6250.9   90.64  6430.9   86.88
  6590.9   87.73  6910.9   85.99  6930.9   88.69  6950.9   93.56  7041.2  100.56
#Mann= 6 , 1 , 0
  3575.4      10       0  4403.5     .15       0 4951.85    .065       0
 5048.15     .15       0  5112.7      .1       0  7041.2      .2       0
Bank Sta=4951.85,5048.15
XS Rating Curve= 0 ,0
Exp/Cntr=0.3,0.1

Type RM Length L Ch R = 1 ,414744.0,1286.6,1286.6,1286.6
BEGIN DESCRIPTION:
Cross Section CCX_W147
Located At: CCX_W147 CNTL
END DESCRIPTION:
#Sta/Elev= 30
  2543.9     102  3218.9  100.05  3458.9   97.41  3658.9   88.81  3838.9   89.63
  3958.9   96.25  4013.7   95.52  4051.7   95.01  4098.9   94.38  4280.9   86.53
  4520.9   82.94  4680.9   88.04  4860.9   86.96  4921.4   82.46  4945.6   77.85
  4951.6   74.29  4953.1   72.19    4957   70.66  5008.5   67.48  5043.4   69.19
  5047.9   73.45  5052.4   78.84  5063.4   81.47  5129.6   82.16    5705   87.92
    5825    85.5    6885   82.46    6905    88.5  6938.2  103.63    6965  117.32
#Mann= 7 , 1 , 0
  2543.9      10       0  4013.7      .2       0  4051.7     .15       0
  4951.6    .065       0  5047.9     .15       0  5129.6      .1       0
  6938.2      .2       0
Bank Sta=4951.6,5047.9
XS Rating Curve= 0 ,0
Exp/Cntr=0.5,0.3

Type RM Length L Ch R = 1 ,413457.4,47,47,47
BEGIN DESCRIPTION:
Upstream Section of Bridge/Culvert/Weir
END DESCRIPTION:
#Sta/Elev= 30
  3268.5   99.45  3508.5   93.66  3568.7   87.43  3688.7   91.38  3706.5   90.98
  3868.7   88.83  4048.7   88.59  4188.7   80.74  4752.2   81.85  4782.9   78.67
  4848.4   76.94  4884.2   77.41  4957.7   72.81  4968.8   67.73  5034.6   69.71
  5037.3   70.43  5044.6   77.84  5078.1   82.29  5164.5   81.11  5264.1   82.08
  5288.6   81.01  5748.6   85.17    6531   84.19    6551   82.91    6591   84.63
    7031   84.07    7051   81.77    7071   84.59  7097.4   94.27    7131  106.59
#Mann= 7 , 1 , 0
  3268.5      .2       0  3268.5     .12       0  3706.5     .15       0
  4957.7    .065       0  5044.6     .15       0  5164.5      .1       0
  7097.4      .2       0
#XS Ineff= 2 , 0
       0    4850   93.25    5090       0   93.25
Permanent Ineff=
       F       F
Bank Sta=4957.7,5044.6
XS Rating Curve= 0 ,0
Exp/Cntr=0.5,0.3

Type RM Length L Ch R = 3 ,413433.9,,,
BEGIN DESCRIPTION:
CSX RAILROAD
Structure ID: WI_CONCR2
END DESCRIPTION:
Bridge Culvert--1,0,-1,-1, 0
Deck Dist Width WeirC Skew NumUp NumDn MinLoCord MaxHiCord MaxSubmerge Is_Ogee
10,27,2.6,0, 42, 42, , , 0.95, 0, 1,1,,
  3268.5  3508.5  3546.4  3568.7  3688.7  3768.7  3868.7  3908.7  3988.7  4048.7
  4148.7  4188.7  4434.9  4574.9  4752.2  4782.9  4830.8  4848.4  4884.2 4943.41
  4943.5 5053.89    5054  5078.1  5125.7    5173    5219  5264.1  5288.6  5559.9
  5748.6  5912.3    6531    6551    6591  6734.1    7031    7051    7071  7074.2
  7097.4    7131
   99.45   93.66   94.61   94.57   94.38   94.24   94.08   94.08   94.09   94.09
    94.1   94.03   93.55   93.18    94.6   94.48   94.31   94.26   94.21   94.09
   94.09   94.11   94.11   94.14   94.26   94.39   94.48   94.51    94.4   93.25
   93.55   93.81   94.48   94.54   94.68   95.18   95.69   95.72   95.75   95.76
   94.27  106.59
   99.45   93.66   89.74   87.43   91.38   89.57   88.83   88.82   89.33   88.59
   83.38   80.74   81.33   81.62   81.85   78.67   77.35   76.94   77.41   74.29
   86.99   87.01   79.09   82.29   81.75   80.97   81.23   82.08   81.01   83.46
   85.17   84.96   84.19   82.91   84.63   84.45   84.07   81.77   84.59   85.76
   94.27  106.59
  3268.5  3508.5  3546.4  3568.7  3688.7  3768.7  3868.7  3908.7  3988.7  4048.7
  4148.7  4188.7  4434.9  4574.9  4752.2  4782.9  4830.8  4848.4  4884.2 4943.41
  4943.5 5053.89    5054  5078.1  5125.7    5173    5219  5264.1  5288.6  5559.9
  5748.6  5912.3    6531    6551    6591  6734.1    7031    7051    7071  7074.2
  7097.4    7131
   99.45   93.66   94.61   94.57   94.38   94.24   94.08   94.08   94.09   94.09
    94.1   94.03   93.55   93.18    94.6   94.48   94.31   94.26   94.21   94.09
   94.09   94.11   94.11   94.14   94.26   94.39   94.48   94.51    94.4   93.25
   93.55   93.81   94.48   94.54   94.68   95.18   95.69   95.72   95.75   95.76
   94.27  106.59
   99.35   93.56   89.64   87.33   91.28   89.47   88.73   88.72   89.23   88.49
   83.28   80.64   81.23   81.52   81.75   78.57   77.25   76.84   77.31   74.19
   86.89   86.91   78.99   82.19   81.65   80.87   81.13   81.98   80.91   83.36
   85.07   84.86   84.09   82.81   84.53   84.35   83.97   81.67   84.49   85.66
   94.17  106.49
Pier Skew, UpSta & Num, DnSta & Num=  ,4996.6, 2 ,4996.6, 2 , 0 , 0 , 0 ,,
     6.7     6.7
   67.98      88
     6.7     6.7
   67.88    87.9
Abutment Skew #Up #Dn= , 2 , 2
  4943.3  4947.1
   86.99    74.1
  4943.3  4947.1
   86.89      74
BR Coef= 1 , 1 , 0 ,1.25, 0 ,,,0.8,0,2,0,
WSPro=,,,, 1 ,,,, 0 ,,,, 0 ,,,,-1 ,-1 ,-1 , 0 , 0 , 0 , 0 , 0
BR U #Sta/Elev= 73
  3268.5   99.45  3508.5   93.66  3546.4   89.74  3568.7   87.43  3688.7   91.38
  3706.5   90.98  3768.7   89.57  3867.9   88.84  3868.7   88.83  3908.7   88.82
  3988.7   89.33  4048.7   88.59  4148.7   83.38  4152.8   83.11  4188.7   80.74
  4434.9   81.33  4532.2   81.57  4574.9   81.62  4752.2   81.85  4752.9   81.78
  4782.9   78.67    4803   78.12  4830.8   77.35  4848.4   76.94  4848.5   76.94
  4884.2   77.41  4894.8   76.85  4939.2   74.51  4943.3    74.3 4943.41   74.29
  4943.5   74.28  4947.1    74.1  4947.2   74.09  4957.7   72.81  4962.8   70.78
  4968.8   67.73  4983.2   68.47  4996.6   69.15  5010.5   68.55  5022.7   69.02
  5034.6   69.71  5037.3   70.43  5044.6   77.84  5053.8   79.06 5053.89   79.07
    5054   79.09  5054.1    79.1  5056.2   79.38  5078.1   82.29  5104.5   81.99
  5125.7   81.75  5156.5   81.24  5164.5   81.11    5173   80.97  5208.8   81.17
    5219   81.23  5263.1   82.06  5264.1   82.08  5288.6   81.01  5559.9   83.46
  5748.6   85.17  5912.3   84.96    6531   84.19  6534.2   83.99    6551   82.91
    6591   84.63  6734.1   84.45    7031   84.07    7051   81.77    7071   84.59
  7074.2   85.76  7097.4   94.27    7131  106.59
BR U #Mann= 7
  3268.5      .2  3268.5     .12  3706.5     .15  4957.7    .065  5044.6     .15
  5164.5      .1  7097.4      .2
BR U Banks=4957.7,5044.6
BR D #Sta/Elev= 73
  3268.5   99.35  3508.5   93.56  3546.4   89.64  3568.7   87.33  3688.7   91.28
  3706.5   90.88  3768.7   89.47  3867.9   88.74  3868.7   88.73  3908.7   88.72
  3988.7   89.23  4048.7   88.49  4148.7   83.28  4152.8   83.01  4188.7   80.64
  4434.9   81.23  4532.2   81.47  4574.9   81.52  4752.2   81.75  4752.9   81.68
  4782.9   78.57    4803   78.02  4830.8   77.25  4848.4   76.84  4848.5   76.84
  4884.2   77.31  4894.8   76.75  4939.2   74.41  4943.3    74.2 4943.41   74.19
  4943.5   74.18  4947.1      74  4947.2   73.99  4957.7   72.71  4962.8   70.68
  4968.8   67.63  4983.2   68.37  4996.6   69.05  5010.5   68.45  5022.7   68.92
  5034.6   69.61  5037.3   70.33  5044.6   77.74  5053.8   78.96 5053.89   78.97
    5054   78.99  5054.1      79  5056.2   79.28  5078.1   82.19  5104.5   81.89
  5125.7   81.65  5156.5   81.14  5164.5   81.01    5173   80.87  5208.8   81.07
    5219   81.13  5263.1   81.96  5264.1   81.98  5288.6   80.91  5559.9   83.36
  5748.6   85.07  5912.3   84.86    6531   84.09  6534.2   83.89    6551   82.81
    6591   84.53  6734.1   84.35    7031   83.97    7051   81.67    7071   84.49
  7074.2   85.66  7097.4   94.17    7131  106.49
BR D #Mann= 7
  3268.5      .2  3268.5     .12  3706.5     .15  4957.7    .065  5044.6     .15
  5164.5      .1  7097.4      .2
BR D Banks=4957.7,5044.6
BC Design=,, 0 ,, 0 ,,,,,,
BC HTab HWMax=106.59
BC Use User HTab Curves=0
BC User HTab FreeFlow(D)= 0

Type RM Length L Ch R = 1 ,413410.4,3501.4,3501.4,3501.4
BEGIN DESCRIPTION:
Downstream Section of Bridge/Culvert/Weir
END DESCRIPTION:
#Sta/Elev= 30
  3268.5   99.35  3508.5   93.56  3568.7   87.33  3688.7   91.28  3706.5   90.88
  3868.7   88.73  4048.7   88.49  4188.7   80.64  4752.2   81.75  4782.9   78.57
  4848.4   76.84  4884.2   77.31  4957.7   72.71  4968.8   67.63  5034.6   69.61
  5037.3   70.33  5044.6   77.74  5078.1   82.19  5164.5   81.01  5264.1   81.98
  5288.6   80.91  5748.6   85.07    6531   84.09    6551   82.81    6591   84.53
    7031   83.97    7051   81.67    7071   84.49  7097.4   94.17    7131  106.49
#Mann= 7 , 1 , 0
  3268.5      .2       0  3268.5     .12       0  3706.5     .15       0
  4957.7    .065       0  5044.6     .15       0  5164.5      .1       0
  7097.4      .2       0
#XS Ineff= 2 , 0
       0    4925    89.4    5070       0    89.4
Permanent Ineff=
       F       F
Bank Sta=4957.7,5044.6
XS Rating Curve= 0 ,0
Exp/Cntr=0.5,0.3

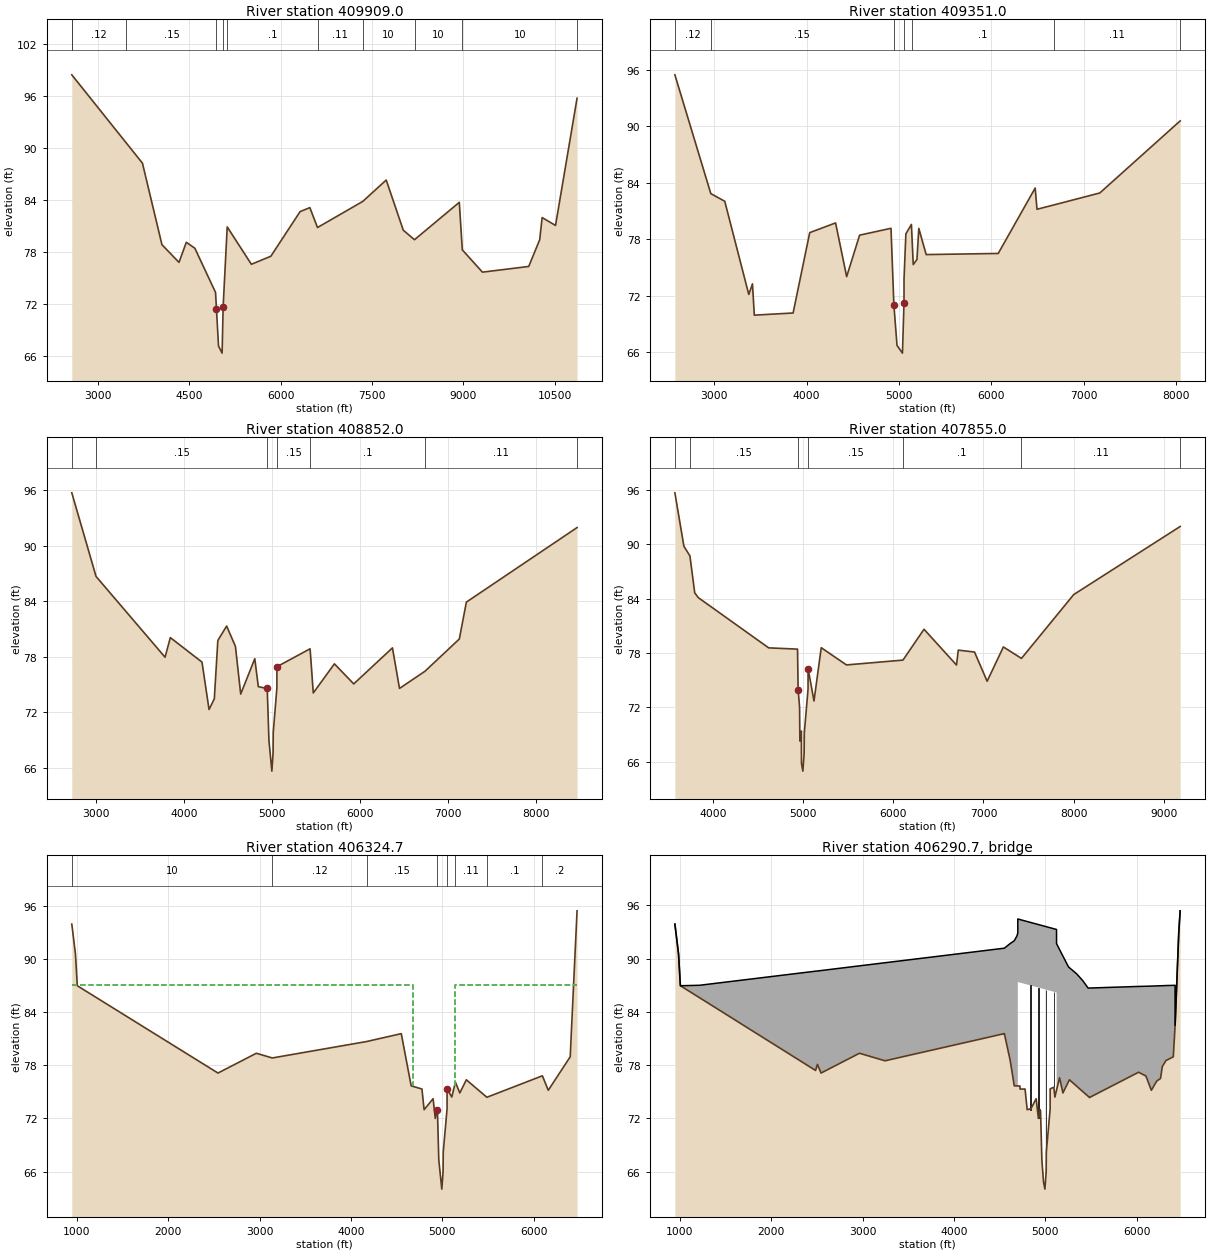
Type RM Length L Ch R = 1 ,409909.0,558,558,558
BEGIN DESCRIPTION:
Cross Section Contentnea Creek 15.0
END DESCRIPTION:
#Sta/Elev= 30
    2570   98.45  3467.3   90.55    3730   88.24    4050   78.82    4330   76.77
    4450   79.09    4590   78.41    4930    73.3  4945.2   71.39  4979.1    67.1
  5037.9   66.28  5054.8   71.64  5121.7   80.87  5518.5   76.55  5838.5   77.48
  6318.5   82.64  6478.5    83.1  6604.2    80.8    7348   83.82  7732.5   86.29
  8012.5   80.49  8196.8   79.39  8932.5   83.71  8981.7   78.22  9312.5   75.64
 10072.5    76.3 10252.5   79.39 10292.5   81.95 10512.5   81.04 10865.9   95.75
#Mann= 11 , 1 , 0
    2570      .2       0    2570     .12       0  3467.3     .15       0
  4945.2    .065       0  5054.8     .15       0  5121.7      .1       0
  6604.2     .11       0    7348      10       0  8196.8      10       0
  8981.7      10       0 10865.9      10       0
Bank Sta=4945.2,5054.8
XS Rating Curve= 0 ,0
Exp/Cntr=0.3,0.1

Type RM Length L Ch R = 1 ,409351.0,499,499,499
BEGIN DESCRIPTION:
Cross Section Contentnea Creek 14.0
END DESCRIPTION:
#Sta/Elev= 30
  2573.9   95.47  2962.9   82.86  3113.9   82.05  3373.9   72.16  3413.9   73.28
  3433.9   69.96  3853.9   70.19  4033.9   78.72  4313.9   79.75  4433.9   74.05
  4573.9   78.45  4913.9   79.18  4945.2   71.04  4979.1   66.75  5037.9   65.93
  5054.8   71.29    5055   73.81    5075   78.59    5135   79.59  5143.9   77.69
    5155   75.33    5195   75.87    5215   79.17    5295   76.39    6075   76.51
    6475   83.45    6495    81.2  6677.7   81.66    7175   82.93  8044.9   90.58
#Mann= 7 , 1 , 0
  2573.9     .12       0  2962.9     .15       0  4945.2    .065       0
  5054.8     .15       0  5143.9      .1       0  6677.7     .11       0
  8044.9      .2       0
Bank Sta=4945.2,5054.8
XS Rating Curve= 0 ,0
Exp/Cntr=0.3,0.1

Type RM Length L Ch R = 1 ,408852.0,997,997,997
BEGIN DESCRIPTION:
Cross Section Contentnea Creek 13.0
END DESCRIPTION:
#Sta/Elev= 30
  2723.5   95.74  2999.1   86.69  3783.5   77.95  3843.5   80.07  4203.5   77.42
  4283.5   72.29  4343.5   73.45  4383.5   79.76  4483.5   81.32  4583.5   79.12
  4643.5   73.96  4803.5   77.79  4843.5   74.76  4944.9   74.57  4964.4   68.93
  4997.5   65.62  5011.6   67.59  5013.2    69.8  5054.8   74.64  5055.1   76.92
  5432.1   78.86  5468.4   74.08  5708.4   77.23  5928.4   75.06  6368.4   78.96
  6448.4   74.57  6738.1   76.43  7128.4   79.92  7208.4   83.91  8466.7   91.98
#Mann= 7 , 1 , 0
  2723.5     .12       0  2999.1     .15       0  4944.9    .065       0
  5055.1     .15       0  5432.1      .1       0  6738.1     .11       0
  8466.7      .2       0
Bank Sta=4944.9,5055.1
XS Rating Curve= 0 ,0
Exp/Cntr=0.3,0.1

Type RM Length L Ch R = 1 ,407855.0,1530.3,1530.3,1530.3
BEGIN DESCRIPTION:
Cross Section Contentnea Creek 11.7
END DESCRIPTION:
#Sta/Elev= 30
  3578.3   95.65  3678.3   89.76  3745.1    88.7  3798.3   84.63  3838.3    84.1
  4618.3   78.57  4938.3   78.43  4944.9   73.94    4961   72.05  4964.4    68.3
    4981   69.41  4982.2   65.82  4997.5   64.99  5011.6   66.96  5013.2   69.17
  5054.8   74.01  5055.1   76.29    5121   72.72    5201   78.59    5481   76.69
  6107.2   77.22    6341   80.62    6701   76.68    6721   78.32    6901   78.11
    7041   74.89    7221   78.67  7421.6   77.41    8001   84.44  9181.3   91.94
#Mann= 7 , 1 , 0
  3578.3     .12       0  3745.1     .15       0  4944.9    .065       0
  5055.1     .15       0  6107.2      .1       0  7421.6     .11       0
  9181.3      .2       0
Bank Sta=4944.9,5055.1
XS Rating Curve= 0 ,0
Exp/Cntr=0.5,0.3

Type RM Length L Ch R = 1 ,406324.7,68,68,68
BEGIN DESCRIPTION:
Upstream Section of Bridge/Culvert/Weir
END DESCRIPTION:
#Sta/Elev= 30
   945.3    93.9   985.3   90.53  1005.3   86.96  2545.3   77.12  2965.3   79.35
  3139.7   78.82  4171.7   80.67  4551.5   81.56  4659.9   75.68  4777.8   75.32
  4801.5   72.99  4899.7   74.23  4923.7   72.01  4942.6   72.99  4947.5   72.85
  4962.1   67.35  4995.2   64.04  5009.3   66.01  5010.9   68.22  5052.5   73.06
  5052.8   75.34  5104.5   74.42  5143.9   76.09  5192.4   74.88  5263.7   76.36
  5488.6   74.39  6096.1   76.81  6160.6   75.18  6400.6   78.95  6475.6    95.4
#Mann= 8 , 1 , 0
   945.3      10       0  3139.7     .12       0  4171.7     .15       0
  4942.6    .065       0  5052.8     .15       0  5143.9     .11       0
  5488.6      .1       0  6096.1      .2       0
#XS Ineff= 2 , 0
       0    4680      87    5135       0      87
Permanent Ineff=
       F       F
Bank Sta=4942.6,5052.8
XS Rating Curve= 0 ,0
Exp/Cntr=0.5,0.3

Type RM Length L Ch R = 3 ,406290.7,,,
BEGIN DESCRIPTION:
US 264
Structure ID: WI_CONCR1B
END DESCRIPTION:
Bridge Culvert--1,0,-1,-1, 0
Deck Dist Width WeirC Skew NumUp NumDn MinLoCord MaxHiCord MaxSubmerge Is_Ogee
10,48,2.6,0, 41, 41, , , 0.95, 0, 1,1,,
   945.3   985.3  1005.3    1215  2485.3  2505.3  2545.3  2965.3  3245.3  4551.5
  4614.6  4659.9  4688.1 4698.47 4698.58 4698.81  4698.9 5122.47 5122.58 5122.69
  5122.8  5155.7  5192.4  5253.6  5263.7  5343.8  5408.9  5468.6  5483.8  6020.6
  6100.6  6160.6  6220.6  6260.6  6280.6  6320.6  6400.6    6420  6420.6  6460.6
  6475.6
   93.89   90.52   86.95      87   88.59   88.61   88.66   89.19   89.54   91.18
    91.7   92.02   92.54   92.87   94.47   94.47   94.47   93.29   91.69   91.69
   91.69   91.03   90.29   89.07   88.98   88.28   87.53   86.68   86.69   86.87
   86.89   86.91   86.93   86.95   86.95   86.97   86.99      87   82.49   92.98
   95.39
   93.89   90.52   86.95    85.6    77.4   78.08   77.11   79.34   78.49   81.55
   78.57   75.67   75.66   75.66   75.66   75.66   87.37   86.19   86.19   86.19
   75.19   76.58   74.87   76.14   76.35   75.62   75.03   74.49   74.35    77.2
   76.78   75.17   76.22   76.49   77.85   78.52   78.94   82.38   82.49   92.98
   95.39
   945.3   985.3  1005.3    1215  2485.3  2505.3  2545.3  2965.3  3245.3  4551.5
  4614.6  4659.9  4688.1 4698.47 4698.58 4698.81  4698.9 5122.47 5122.58 5122.69
  5122.8  5155.7  5192.4  5253.6  5263.7  5343.8  5408.9  5468.6  5483.8  6020.6
  6100.6  6160.6  6220.6  6260.6  6280.6  6320.6  6400.6    6420  6420.6  6460.6
  6475.6
   93.89   90.52   86.95      87   88.59   88.61   88.66   89.19   89.54   91.18
    91.7   92.02   92.54   92.87   94.47   94.47   94.47   93.29   91.69   91.69
   91.69   91.03   90.29   89.07   88.98   88.28   87.53   86.68   86.69   86.87
   86.89   86.91   86.93   86.95   86.95   86.97   86.99      87   82.49   92.98
   95.39
   93.79   90.42   86.85    85.5    77.3   77.98   77.01   79.24   78.39   81.45
   78.47   75.57   75.56   75.56   75.56   75.56   87.27   86.09   86.09   86.09
   75.09   76.48   74.77   76.04   76.25   75.52   74.93   74.39   74.25    77.1
   76.68   75.07   76.12   76.39   77.75   78.42   78.84   82.28   82.39   92.88
   95.29
Pier Skew, UpSta & Num, DnSta & Num=  ,4837.7, 2 ,4837.7, 2 , 0 , 0 , 0 ,,
     3.5     3.5
   72.03   87.98
     3.5     3.5
   71.93   87.88
Pier Skew, UpSta & Num, DnSta & Num=  ,4923.7, 2 ,4923.7, 2 , 0 , 0 , 0 ,,
     3.5     3.5
   71.09   87.75
     3.5     3.5
   70.99   87.65
Pier Skew, UpSta & Num, DnSta & Num=  ,5009.3, 2 ,5009.3, 2 , 0 , 0 , 0 ,,
     3.5     3.5
   64.76    87.5
     3.5     3.5
   64.66    87.4
Pier Skew, UpSta & Num, DnSta & Num=  ,5092.9, 2 ,5092.9, 2 , 0 , 0 , 0 ,,
     3.5     3.5
   74.34   87.27
     3.5     3.5
   74.24   87.17
Abutment Skew #Up #Dn= , 2 , 2
  4698.7  4777.8
   87.37   75.31
  4698.7  4777.8
   87.27   75.21
Abutment Skew #Up #Dn= , 2 , 2
  5104.5 5122.89
   74.41   86.19
  5104.5 5122.89
   74.31   86.09
BR Coef= 1 , 1 , 0 ,1.25, 0 ,,,0.8,0,2,0,
WSPro=,,,, 1 ,,,, 0 ,,,, 0 ,,,,-1 ,-1 ,-1 , 0 , 0 , 0 , 0 , 0
BR U #Sta/Elev= 72
   945.3   93.89   985.3   90.52  1005.3   86.95    1215    85.6  2485.3    77.4
  2505.3   78.08  2545.3   77.11  2965.3   79.34  3139.7   78.81  3245.3   78.49
  4171.7   80.66  4549.8   81.55  4551.5   81.55  4602.1   79.16  4614.6   78.57
  4655.4   75.96  4659.9   75.67  4688.1   75.66 4698.47   75.66 4698.58   75.66
 4698.69   75.66 4698.81   75.66  4698.9   75.66  4721.3   75.65  4724.1    75.3
  4777.7   75.31  4777.8   75.31  4801.5   72.98  4837.4   73.08  4837.7      73
  4899.7   74.22  4923.7      72  4942.6   72.98  4947.5   72.84  4962.1   67.34
  4979.9   64.86  4995.2   64.03  5009.3      66  5010.9   68.21  5052.5   73.05
  5052.8   75.33  5092.9   75.51  5104.4   74.41  5104.5   74.41 5122.36   75.17
 5122.47   75.17 5122.58   75.18 5122.69   75.18  5122.8   75.19  5143.9   76.08
  5155.7   76.58  5192.4   74.87  5253.6   76.14  5263.7   76.35  5343.8   75.62
  5408.9   75.03  5468.6   74.49  5483.8   74.35  5488.6   74.38  6020.6    77.2
  6096.1    76.8  6100.6   76.78  6160.6   75.17  6220.6   76.22  6260.6   76.49
  6280.6   77.85  6320.6   78.52  6400.6   78.94    6420   82.38  6420.6   82.49
  6460.6   92.98  6475.6   95.39
BR U #Mann= 8
   945.3      10  3139.7     .12  4171.7     .15  4942.6    .065  5052.8     .15
  5143.9     .11  5488.6      .1  6096.1      .2
BR U Banks=4942.6,5052.8
BR D #Sta/Elev= 72
   945.3   93.79   985.3   90.42  1005.3   86.85    1215    85.5  2485.3    77.3
  2505.3   77.98  2545.3   77.01  2965.3   79.24  3139.7   78.71  3245.3   78.39
  4171.7   80.56  4549.8   81.45  4551.5   81.45  4602.1   79.06  4614.6   78.47
  4655.4   75.86  4659.9   75.57  4688.1   75.56 4698.47   75.56 4698.58   75.56
 4698.69   75.56 4698.81   75.56  4698.9   75.56  4721.3   75.55  4724.1    75.2
  4777.7   75.21  4777.8   75.21  4801.5   72.88  4837.4   72.98  4837.7    72.9
  4899.7   74.12  4923.7    71.9  4942.6   72.88  4947.5   72.74  4962.1   67.24
  4979.9   64.76  4995.2   63.93  5009.3    65.9  5010.9   68.11  5052.5   72.95
  5052.8   75.23  5092.9   75.41  5104.4   74.31  5104.5   74.31 5122.36   75.07
 5122.47   75.07 5122.58   75.08 5122.69   75.08  5122.8   75.09  5143.9   75.98
  5155.7   76.48  5192.4   74.77  5253.6   76.04  5263.7   76.25  5343.8   75.52
  5408.9   74.93  5468.6   74.39  5483.8   74.25  5488.6   74.28  6020.6    77.1
  6096.1    76.7  6100.6   76.68  6160.6   75.07  6220.6   76.12  6260.6   76.39
  6280.6   77.75  6320.6   78.42  6400.6   78.84    6420   82.28  6420.6   82.39
  6460.6   92.88  6475.6   95.29
BR D #Mann= 8
   945.3      10  3139.7     .12  4171.7     .15  4942.6    .065  5052.8     .15
  5143.9     .11  5488.6      .1  6096.1      .2
BR D Banks=4942.6,5052.8
BC Design=,, 0 ,, 0 ,,,,,,
BC HTab HWMax=95.4
BC Use User HTab Curves=0
BC User HTab FreeFlow(D)= 0