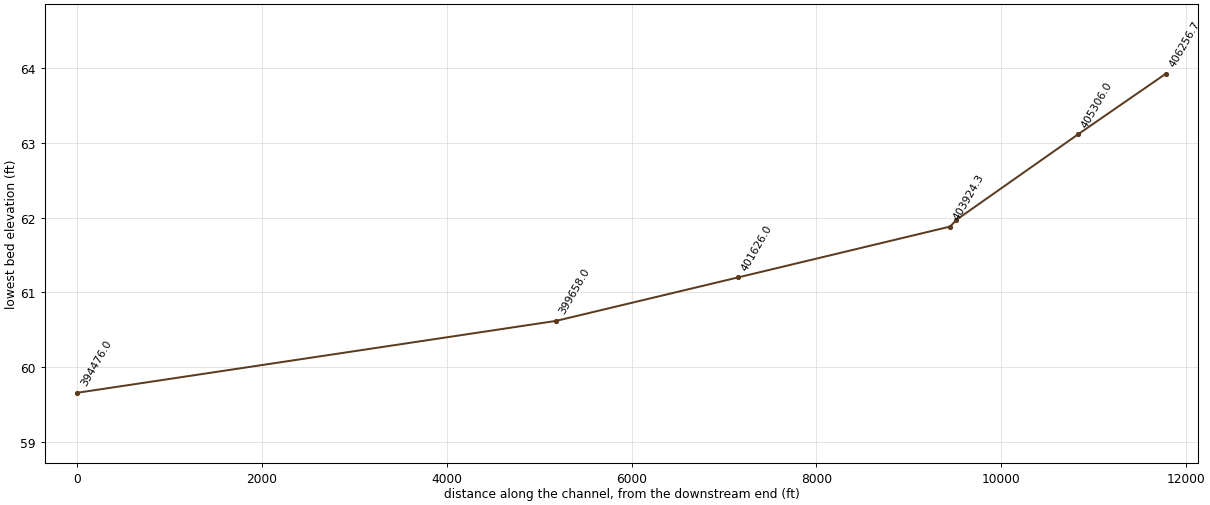
HEC-RAS study CONTENTNEA_FINAL.PRJ: Contentnea

--- CONTENTNEA_FINAL.g01 (geometry) --- (continued)

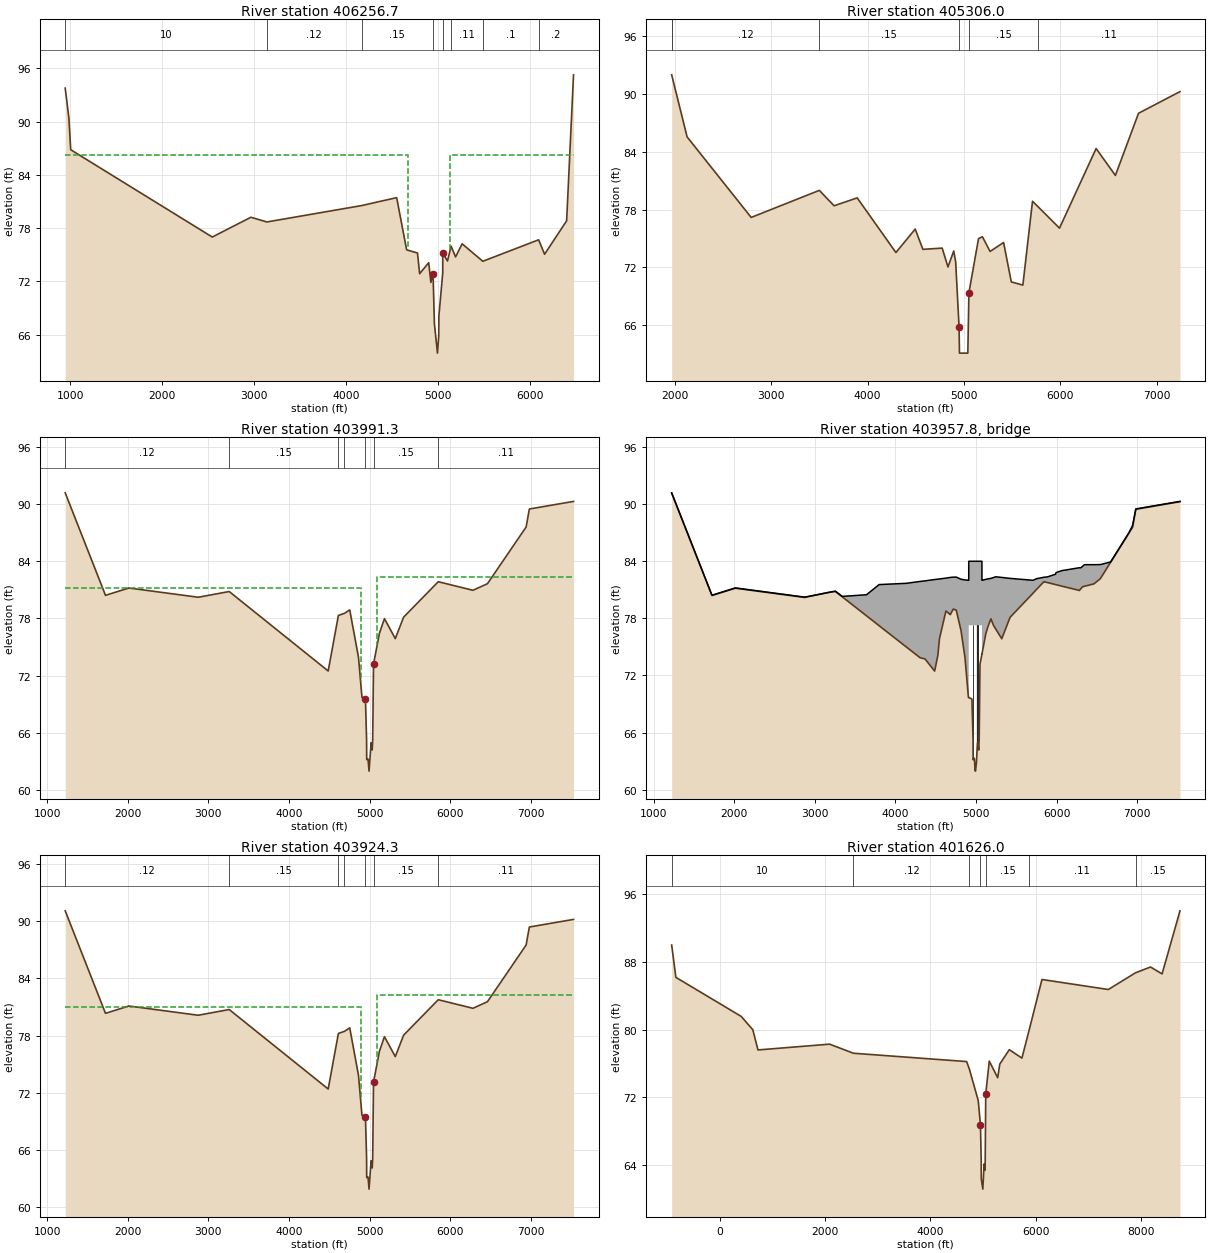
Type RM Length L Ch R = 1 ,406256.7,950.7,950.7,950.7
BEGIN DESCRIPTION:
Downstream Section of Bridge/Culvert/Weir
END DESCRIPTION:
#Sta/Elev= 30
   945.3   93.78   985.3   90.41  1005.3   86.84  2545.3      77  2965.3   79.23
  3139.7    78.7  4171.7   80.55  4551.5   81.44  4659.9   75.56  4777.8    75.2
  4801.5   72.87  4899.7   74.11  4923.7   71.89  4942.6   72.87  4947.5   72.73
  4962.1   67.23  4995.2   63.92  5009.3   65.89  5010.9    68.1  5052.5   72.94
  5052.8   75.22  5104.5    74.3  5143.9   75.97  5192.4   74.76  5263.7   76.24
  5488.6   74.27  6096.1   76.69  6160.6   75.06  6400.6   78.83  6475.6   95.28
#Mann= 8 , 1 , 0
   945.3      10       0  3139.7     .12       0  4171.7     .15       0
  4942.6    .065       0  5052.8     .15       0  5143.9     .11       0
  5488.6      .1       0  6096.1      .2       0
#XS Ineff= 2 , 0
       0    4680    86.3    5135       0    86.3
Permanent Ineff=
       F       F
Bank Sta=4942.6,5052.8
XS Rating Curve= 0 ,0
Exp/Cntr=0.5,0.3

Type RM Length L Ch R = 1 ,405306.0,1314.7,1314.7,1314.7
BEGIN DESCRIPTION:
Cross Section Contentnea Creek 11.0
END DESCRIPTION:
#Sta/Elev= 30
  1967.2   91.99  2127.2   85.55  2792.1   77.19  3499.2      80  3652.1    78.4
  3892.1   79.22  4293.7   73.55  4493.7   75.98  4573.7   73.88  4773.7   74.01
  4833.7   72.05  4893.7   73.71  4913.7   72.57 4948.85   65.83 4953.15   63.11
 5039.65   63.11 5051.15   69.38  5150.8   74.99  5190.8   75.19  5270.8   73.66
  5410.8   74.59  5490.8    70.5  5610.8   70.17  5710.8   78.87  5768.5    78.3
  5990.8   76.08  6370.8   84.34  6570.8   81.55  6810.8      88    7241   90.25
#Mann= 6 , 1 , 0
  1967.2      10       0  1967.2     .12       0  3499.2     .15       0
 4948.85    .065       0 5051.15     .15       0  5768.5     .11       0
Bank Sta=4948.85,5051.15
XS Rating Curve= 0 ,0
Exp/Cntr=0.5,0.3

Type RM Length L Ch R = 1 ,403991.3,67,67,67
BEGIN DESCRIPTION:
Upstream Section of Bridge/Culvert/Weir
END DESCRIPTION:
#Sta/Elev= 30
  1223.9   91.18  1723.9   80.42  2014.1   81.19  2874.1   80.22  3258.9   80.82
  4486.9   72.48  4613.6   78.31  4689.2   78.53  4754.4   78.89  4863.1   73.91
  4905.9   69.72  4949.2   69.55  4963.4   65.25  4964.6   63.18    4981   63.24
  4993.8   61.97  5019.4   64.95  5033.1   64.19  5039.1   65.22  5049.4   73.19
  5122.3   76.43    5185   77.97  5319.6   75.88  5422.9   78.13  5852.8   81.85
  6282.9   80.95  6462.9   81.64  6942.9   87.59  6982.9   89.48  7531.1   90.28
#Mann= 7 , 1 , 0
  1223.9     .12       0  3258.9     .15       0  4613.6     .12       0
  4689.2     .15       0  4949.2    .065       0  5049.4     .15       0
  5852.8     .11       0
#XS Ineff= 2 , 0
       0    4890    81.2    5090       0    82.3
Permanent Ineff=
       F       F
Bank Sta=4949.2,5049.4
XS Rating Curve= 0 ,0
Exp/Cntr=0.5,0.3

Type RM Length L Ch R = 3 ,403957.8,,,
BEGIN DESCRIPTION:
OLD BLACK CREEK ROAD (SR 1606)
Structure ID: WI_CONCR1
END DESCRIPTION:
Bridge Culvert--1,0,-1,-1, 0
Deck Dist Width WeirC Skew NumUp NumDn MinLoCord MaxHiCord MaxSubmerge Is_Ogee
10,47,2.6,0, 54, 54, , , 0.95, 0, 1,1,,
  1223.9  1723.9  2014.1  2874.1  3254.1  3340.9  3641.3  3797.4  4132.9  4306.9
  4366.9  4486.9  4526.9  4546.9  4626.9    4682  4716.6  4754.4  4813.2  4863.1
  4905.9 4909.67 4909.78 4910.01  4910.1 5073.57 5073.68 5073.79  5073.9  5122.3
  5148.4    5185  5217.5  5244.2  5319.6  5422.9  5707.5  5752.5  5842.9  5887.5
  5987.5  5992.5  6067.5  6282.9  6300.1  6322.9  6345.1  6462.9  6542.9  6669.6
  6894.6  6942.9  6982.9  7531.1
   91.19   80.43    81.2   80.23   80.86   80.31   80.48   81.55   81.68   81.88
   81.94   82.08   82.12   82.14   82.23    82.3   82.33   82.34   82.11   82.04
      82      82      84      84      84      84      82      82      82    82.1
   82.15    82.2   82.29   82.37    82.3    82.2      82   82.17   82.32   82.36
   82.64   82.81   83.02   83.32   83.31   83.48   83.64   83.64   83.65   83.92
   86.96   87.76    89.5   90.29
   91.16    80.4   81.17    80.2   80.83   80.26   78.27   77.23   75.01   73.86
   73.74   72.46   74.12   75.87   78.77   78.39   78.97   78.87   76.76   73.89
    69.7   69.69   69.68   69.68   77.27   77.27   77.27   77.27   74.26   76.41
   77.13   77.95   77.26   76.89   75.86   78.11   80.64   81.05   81.85   81.76
   81.55   81.54   81.38   80.93    81.1   81.32   81.37   81.62   82.17   83.88
   86.92   87.57   89.46   90.26
  1223.9  1723.9  2014.1  2874.1  3254.1  3340.9  3641.3  3797.4  4132.9  4306.9
  4366.9  4486.9  4526.9  4546.9  4626.9    4682  4716.6  4754.4  4813.2  4863.1
  4905.9 4909.67 4909.78 4910.01  4910.1 5073.57 5073.68 5073.79  5073.9  5122.3
  5148.4    5185  5217.5  5244.2  5319.6  5422.9  5707.5  5752.5  5842.9  5887.5
  5987.5  5992.5  6067.5  6282.9  6300.1  6322.9  6345.1  6462.9  6542.9  6669.6
  6894.6  6942.9  6982.9  7531.1
   91.19   80.43    81.2   80.23   80.86   80.31   80.48   81.55   81.68   81.88
   81.94   82.08   82.12   82.14   82.23    82.3   82.33   82.34   82.11   82.04
      82      82      84      84      84      84      82      82      82    82.1
   82.15    82.2   82.29   82.37    82.3    82.2      82   82.17   82.32   82.36
   82.64   82.81   83.02   83.32   83.31   83.48   83.64   83.64   83.65   83.92
   86.96   87.76    89.5   90.29
   91.09   80.33    81.1   80.13   80.76   80.19    78.2   77.16   74.94   73.79
   73.67   72.39   74.05    75.8    78.7   78.32    78.9    78.8   76.69   73.82
   69.63   69.62   69.61   69.61    77.2    77.2    77.2    77.2   74.19   76.34
   77.06   77.88   77.19   76.82   75.79   78.04   80.57   80.98   81.78   81.69
   81.48   81.47   81.31   80.86   81.03   81.25    81.3   81.55    82.1   83.81
   86.85    87.5   89.39   90.19
Pier Skew, UpSta & Num, DnSta & Num=  ,4964.6, 2 ,4964.6, 2 , 0 , 0 , 0 ,,
       3       3
    62.2   78.27
       3       3
   62.13    78.2
Pier Skew, UpSta & Num, DnSta & Num=  ,5019.4, 2 ,5019.4, 2 , 0 , 0 , 0 ,,
       3       3
   63.75   78.27
       3       3
   63.68    78.2
BR Coef= 1 , 1 , 0 ,1.25, 0 ,,,0.8,0,2,0,
WSPro=,,,, 1 ,,,, 0 ,,,, 0 ,,,,-1 ,-1 ,-1 , 0 , 0 , 0 , 0 , 0
BR U #Sta/Elev= 94
  1223.9   91.16  1723.9    80.4  2014.1   81.17  2874.1    80.2  3174.1   80.73
  3254.1   80.83  3258.9    80.8  3340.9   80.26  3641.3   78.27  3797.4   77.23
  4132.9   75.01  4306.9   73.86  4366.9   73.74  4486.9   72.46  4526.9   74.12
  4546.9   75.87  4613.6   78.29  4626.9   78.77    4682   78.39  4689.2   78.51
  4716.6   78.97  4747.8   78.89  4754.4   78.87  4798.9   77.27  4813.2   76.76
  4853.2   74.46  4863.1   73.89  4905.9    69.7  4908.5   69.69 4909.67   69.69
 4909.78   69.68 4909.89   69.68 4910.01   69.68  4910.1   69.68  4910.2   69.68
  4949.2   69.53  4954.4   68.03  4958.6    66.7  4963.4   65.23  4964.6   63.16
  4971.7   63.35    4981   63.22  4988.5      62  4993.8   61.95  5005.4   62.84
  5013.9   64.26  5019.4   64.93  5023.2   64.94  5033.1   64.17  5039.1    65.2
  5041.3   66.82  5049.4   73.17  5073.4   74.24 5073.46   74.24 5073.57   74.24
 5073.68   74.25 5073.79   74.25  5073.9   74.26  5075.6   74.33  5122.3   76.41
  5129.2    76.6  5148.4   77.13    5185   77.95  5190.7   77.83  5217.5   77.26
  5244.2   76.89  5319.6   75.86  5422.9   78.11  5596.4   79.65  5707.5   80.64
  5752.5   81.05  5837.5    81.8  5842.9   81.85  5852.8   81.83  5887.5   81.76
  5987.5   81.55  5992.5   81.54  6067.5   81.38  6130.1   81.25  6270.1   80.96
  6282.9   80.93  6300.1    81.1  6322.9   81.32  6345.1   81.37  6462.9   81.62
  6542.9   82.17  6669.6   83.88  6824.6   85.97  6894.6   86.92  6942.9   87.57
  6982.9   89.46    6998   89.48    7531   90.26  7531.1   90.26
BR U #Mann= 7
  1223.9     .12  3258.9     .15  4613.6     .12  4689.2     .15  4949.2    .065
  5049.4     .15  5852.8     .11
BR U Banks=4949.2,5049.4
BR D #Sta/Elev= 94
  1223.9   91.09  1723.9   80.33  2014.1    81.1  2874.1   80.13  3174.1   80.66
  3254.1   80.76  3258.9   80.73  3340.9   80.19  3641.3    78.2  3797.4   77.16
  4132.9   74.94  4306.9   73.79  4366.9   73.67  4486.9   72.39  4526.9   74.05
  4546.9    75.8  4613.6   78.22  4626.9    78.7    4682   78.32  4689.2   78.44
  4716.6    78.9  4747.8   78.82  4754.4    78.8  4798.9    77.2  4813.2   76.69
  4853.2   74.39  4863.1   73.82  4905.9   69.63  4908.5   69.62 4909.67   69.62
 4909.78   69.61 4909.89   69.61 4910.01   69.61  4910.1   69.61  4910.2   69.61
  4949.2   69.46  4954.4   67.96  4958.6   66.63  4963.4   65.16  4964.6   63.09
  4971.7   63.28    4981   63.15  4988.5   61.93  4993.8   61.88  5005.4   62.77
  5013.9   64.19  5019.4   64.86  5023.2   64.87  5033.1    64.1  5039.1   65.13
  5041.3   66.75  5049.4    73.1  5073.4   74.17 5073.46   74.17 5073.57   74.17
 5073.68   74.18 5073.79   74.18  5073.9   74.19  5075.6   74.26  5122.3   76.34
  5129.2   76.53  5148.4   77.06    5185   77.88  5190.7   77.76  5217.5   77.19
  5244.2   76.82  5319.6   75.79  5422.9   78.04  5596.4   79.58  5707.5   80.57
  5752.5   80.98  5837.5   81.73  5842.9   81.78  5852.8   81.76  5887.5   81.69
  5987.5   81.48  5992.5   81.47  6067.5   81.31  6130.1   81.18  6270.1   80.89
  6282.9   80.86  6300.1   81.03  6322.9   81.25  6345.1    81.3  6462.9   81.55
  6542.9    82.1  6669.6   83.81  6824.6    85.9  6894.6   86.85  6942.9    87.5
  6982.9   89.39    6998   89.41    7531   90.19  7531.1   90.19
BR D #Mann= 7
  1223.9     .12  3258.9     .15  4613.6     .12  4689.2     .15  4949.2    .065
  5049.4     .15  5852.8     .11
BR D Banks=4949.2,5049.4
BC Design=,, 0 ,, 0 ,,,,,,
BC HTab HWMax=91.18
BC Use User HTab Curves=0
BC User HTab FreeFlow(D)= 0

Type RM Length L Ch R = 1 ,403924.3,2298.3,2298.3,2298.3
BEGIN DESCRIPTION:
Downstream Section of Bridge/Culvert/Weir
END DESCRIPTION:
#Sta/Elev= 30
  1223.9   91.09  1723.9   80.33  2014.1    81.1  2874.1   80.13  3258.9   80.73
  4486.9   72.39  4613.6   78.22  4689.2   78.44  4754.4    78.8  4863.1   73.82
  4905.9   69.63  4949.2   69.46  4963.4   65.16  4964.6   63.09    4981   63.15
  4993.8   61.88  5019.4   64.86  5033.1    64.1  5039.1   65.13  5049.4    73.1
  5122.3   76.34    5185   77.88  5319.6   75.79  5422.9   78.04  5852.8   81.76
  6282.9   80.86  6462.9   81.55  6942.9    87.5  6982.9   89.39  7531.1   90.19
#Mann= 7 , 1 , 0
  1223.9     .12       0  3258.9     .15       0  4613.6     .12       0
  4689.2     .15       0  4949.2    .065       0  5049.4     .15       0
  5852.8     .11       0
#XS Ineff= 2 , 0
       0    4890      81    5090       0    82.3
Permanent Ineff=
       F       F
Bank Sta=4949.2,5049.4
XS Rating Curve= 0 ,0
Exp/Cntr=0.5,0.3

Type RM Length L Ch R = 1 ,401626.0,1968,1968,1968
BEGIN DESCRIPTION:
Cross Section Contentnea Creek 10.0
END DESCRIPTION:
#Sta/Elev= 30
  -910.8   89.96  -830.8   86.15   409.2   81.55   629.2   79.98   727.3    77.6
  2087.3   78.28    2539   77.21  4687.3   76.23  4738.9   75.35  4907.3   71.64
  4949.9   68.78  4964.1   64.48  4965.3   62.41  4994.5    61.2  5020.1   64.18
  5033.8   63.42  5039.8   64.45  5050.1   72.42  5116.9   76.28  5276.9   74.33
  5316.9   75.93  5496.9   77.63  5736.9   76.64  5874.8   79.96  6116.9    85.9
  7376.9   84.72    7893   86.69  8176.9   87.37  8396.9   86.56  8736.9   93.99
#Mann= 7 , 1 , 0
  -910.8      10       0    2539     .12       0  4738.9     .15       0
  4949.9    .065       0  5050.1     .15       0  5874.8     .11       0
    7893     .15       0
Bank Sta=4949.9,5050.1
XS Rating Curve= 0 ,0
Exp/Cntr=0.3,0.1

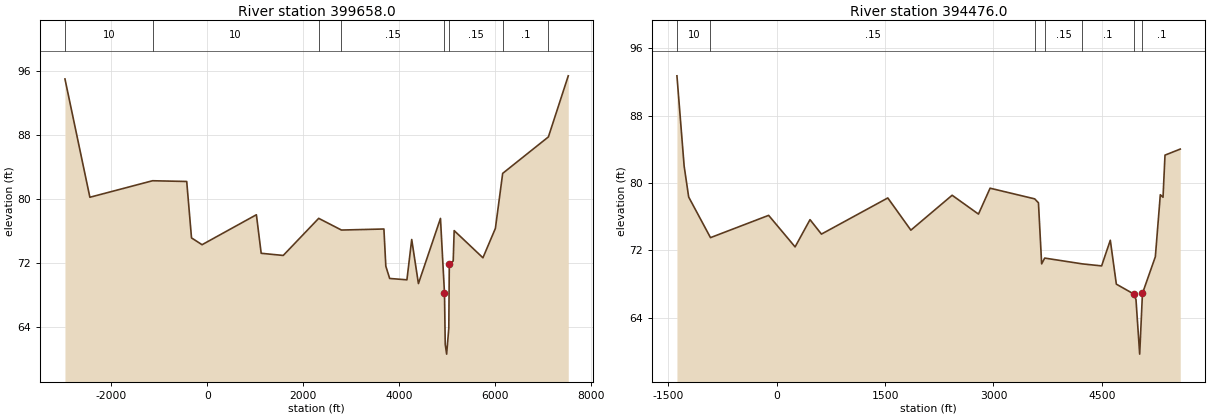
Type RM Length L Ch R = 1 ,399658.0,5182,5182,5182
BEGIN DESCRIPTION:
Cross Section Contentnea Creek 8.0
END DESCRIPTION:
#Sta/Elev= 30
 -2967.4   94.95 -2447.4   80.19   -1141   82.25  -427.4   82.16  -327.4   75.12
  -107.4   74.27    1026   78.01    1126    73.2    1586   72.93    2326   77.56
    2800    76.1    3686   76.23    3726   71.59    3806   70.06    4166   69.89
    4266   74.92    4406   69.42    4866   77.55  4949.9    68.2  4965.3   61.83
  4994.5   60.62  5039.8   63.87  5050.1   71.84  5131.7   72.24  5151.7   76.03
  5751.7   72.64  6011.7   76.31  6163.6   83.17  7117.3   87.72  7531.7   95.34
#Mann= 8 , 1 , 0
 -2967.4      10       0   -1141      10       0    2326     .12       0
    2800     .15       0  4949.9    .065       0  5050.1     .15       0
  6163.6      .1       0  7117.3     .11       0
Bank Sta=4949.9,5050.1
XS Rating Curve= 0 ,0
Exp/Cntr=0.3,0.1

Type RM Length L Ch R = 1 ,394476.0,1077,1077,1077
BEGIN DESCRIPTION:
Cross Section Contentnea Creek 4.0
END DESCRIPTION:
#Sta/Elev= 30
 -1380.2   92.75-1280.43   82.01-1217.74   78.34-915.875   73.51-111.355   76.16
 254.775   72.41 461.205   75.65 619.365   73.931537.435   78.231856.815    74.4
2427.635   78.552792.315   76.312952.935   79.393570.135   78.123622.305   77.65
3666.425   70.393708.655   71.084229.875   70.394496.245   70.154616.525    73.2
4700.095   67.984938.715   66.824971.805   66.155022.965   59.665061.285   66.88
5239.815   71.245308.535   78.615346.055   78.315373.315   83.325584.325   84.04
#Mann= 7 ,-1 , 0
 -1380.2      10       0-915.875     .15       03570.135    .065       0
3708.655     .15       04229.875      .1       04938.715     .05       0
5061.285      .1       0
Bank Sta=4938.715,5061.285
XS Rating Curve= 0 ,0
Exp/Cntr=0.3,0.1

Chan Stop Cuts=-1
Use User Specified Reach Order=0