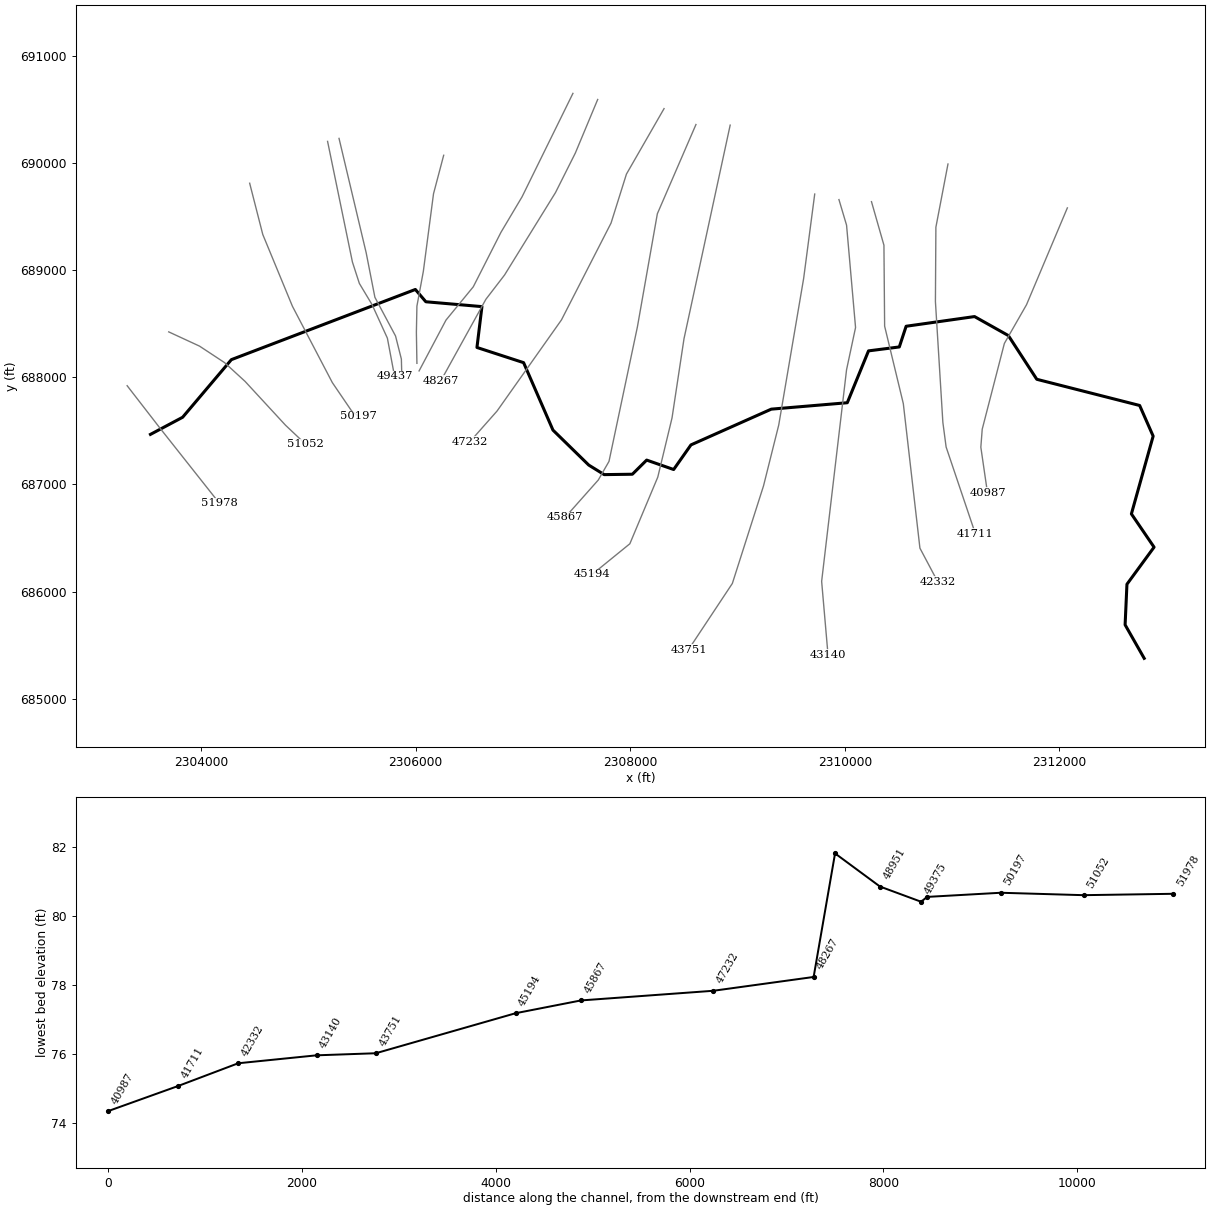
--- DTL_Black_Ck_US.prj (project) ---

Proj Title=dtl_black_crk_upstream
Current Plan=p01
Default Exp/Contr=0.3,0.1
English Units
Geom File=g01
Flow File=f01
Flow File=f03
Plan File=p01
Plan File=p02
Y Axis Title=Elevation
X Axis Title(PF)=Main Channel Distance
X Axis Title(XS)=Station
BEGIN DESCRIPTION:
END DESCRIPTION:
DSS Export Rating Curves= 0
DSS Export Rating Curve Sorted= 0
DSS Export Volume Flow Curves= 0
DXF OffsetX= 0
DXF OffsetY= 0
DXF ScaleX= 1
DXF ScaleY= 10

--- DTL_Black_Ck_US.p01 (plan) ---

Plan Title=dtl_black_crk_upstream
Program Version=4.00
Short Identifier=dtl_black_cr
Geom File=g01
Flow File=f03
Subcritical Flow
K Sum by GR= 0
Std Step Tol= 0.01
Critical Tol= 0.01
Num of Std Step Trials= 20
Max Error Tol= 0.3
Flow Tol Ratio= 0.001
Split Flow NTrial= 30
Split Flow Tol= 0.02
Split Flow Ratio= 0.02
Log Output Level= 0
Friction Slope Method= 1
Unsteady Friction Slope Method= 2
Unsteady Bridges Friction Slope Method= 1
Parabolic Critical Depth
Global Vel Dist= 0 , 0 , 0
Global Log Level= 0
CheckData=True
Encroach Param=-1 ,10,10, 2
Encroach River=Black Creek
Encroach Reach=Upstream
Encroach Node=51978
       1     382    1040
Encroach Node=51052
       1     400    1060
Encroach Node=50197
       1     980    1750
Encroach Node=49437
       1    1140    1685
Encroach Node=49375
       1    1140    1685
Encroach Node=48951
       1    1000    1470
Encroach Node=48488
       1    2010    2408
Encroach Node=48267
       1    1999    2458
Encroach Node=47232
       1    2465    3260
Encroach Node=45867
       1    2300    3640
Encroach Node=45194
       1    2300    3640
Encroach Node=43751
       1    1350    2500
Encroach Node=43140
       1    1145    2200
Encroach Node=42332
       1     800    1600
Encroach Node=41711
       1    1110    1800
Encroach Node=40987
       1    1180    1700
Encroach Node=39950
       1  964.67    1370
Encroach Node=39515
       1     832    1030
Encroach Node=39402
       1     810    1068
Encroach Node=38341
       1    1470    1975
Encroach Node=37771
       1    1295    1735
Encroach Node=36628
       1 1063.25 1513.25
Computation Interval=1HOUR
Output Interval=1HOUR
Run HTab= 0
Run UNet= 0
Run PostProcess= 0
Run WQNet= 0
UNET Theta= 1
UNET Theta Warmup= 1
UNET ZTol= 0.02
UNET ZSATol= 0.05
UNET MxIter= 20
UNET MaxInSteps= 0
UNET DtIC= 0
UNET DtMin= 0
UNET MaxCRTS= 20
UNET WFStab= 2
UNET SFStab= 1
UNET WFX= 1
UNET SFX= 1
UNET DSS MLevel= 4
UNET DZMax Abort= 100
UNET Convert EG Bridges= 0
UNET Use Existing IB Tables=-1
UNET Froude Reduction=False
UNET Froude Limit= 1
UNET Froude Power= 10
UNET Time Slicing=0,0, 5
Instantaneous Interval=1HOUR
Write IC File= 0
Echo Input=False
Echo Output=False
Write Detailed= 0
Detailed Automatic Start=False, 10
WQ ULTIMATE=-1
WQ Max Comp Step=1HOUR
WQ Output Interval=15MIN
WQ Output Selected Increments= 0
WQ Output face flow=0
WQ Output face velocity=0
WQ Output face area=0
WQ Output face dispersion=0
WQ Output cell volume=0
WQ Output cell surface area=0
WQ Output cell continuity=0
WQ Output face conc=0
WQ Output face dconc_dx=0
WQ Output face courant=0
WQ Output face peclet=0
WQ Output face adv mass=0
WQ Output face disp mass=0
WQ Output cell mass=0
WQ Output cell source sink temp=0
WQ Output cell source sink nsm=0
WQ Output MaxMinRange=-1
WQ Daily Max Min Mean=-1
WQ Daily Range=0
WQ Daily Time=0
WQ Create Restart=0
WQ Fixed Restart=0
WQ System Summary=False
Sorting and Armoring Iterations= 10
XS Update Threshold= 0.02
Hydraulics Update Threshold= 0.02
Energy Slope Method= 1
Volume Change Method= 0
XS Weighting Method= 0
Number of US Weighted Cross Sections= 1
Number of DS Weighted Cross Sections= 1
Upstream XS Weight=0.25
Main XS Weight=0.5
Downstream XS Weight=0.25
Number of DS XS's Weighted with US Boundary= 1
Upstream Boundary Weight= 1
Weight of XSs Associated with US Boundary= 0
Number of US XS's Weighted with DS Boundary= 1
Downstream Boundary Weight= 0.5
Weight of XSs Associated with DS Boundary= 0.5
Sediment Output Level= 4
Mass or Volume Output= 0
Output Increment Type= 1
Profile and TS Output Increment= 10
XS Output Flag= 0
XS Output Increment= 10
Disregard all LS=0
Disregard all Conn=0
Disregard all Breaches=0
Disregard all Pumps=0

--- DTL_Black_Ck_US.p02 (plan) ---

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Plan Title=dtl_black_crk_upstream_future
Short Identifier=Future
Geom File=g01
Flow File=f01
Encroach Node=15321
       1     390     910
Encroach Node=14395
       1     512     990
Encroach Node=13541
       1     760  1759.5
Encroach Node=12781
       1 1557.99 1709.66
Encroach Node=12718
       1 1562.99 1704.66
Encroach Node=12295
Encroach Node=11831
       1    2051    2368
Encroach Node=11610
       1    2070    2388
Encroach Node=10576
       1    2522    3230
Encroach Node=9210
       1    2388    3640
Encroach Node=8537
       1    2250    3600
Encroach Node=7095
       1    1000    2500
Encroach Node=6484
       1  878.62    2000
Encroach Node=5676
Encroach Node=5055
Encroach Node=4330
Encroach Node=3294
       1  964.67 1465.13
Encroach Node=2858
       1  844.14 1018.76
Encroach Node=2745
       1  870.14 1008.76
Encroach Node=1684
Encroach Node=1114
       1    1295    1725
Encroach Node=8
       1 1343.91    1715

--- DTL_Black_Ck_US.f03 (steady flow) ---

Flow Title=dtl_black_crk_upstream
Program Version=4.00
Number of Profiles= 6
Profile Names=100-yr,FW,10-yr,25-yr,50-yr,500-yr
River Rch & RM=Black Creek,Upstream        ,51978
    5814    5814    2944    3967    4855    8477
River Rch & RM=Black Creek,Upstream        ,50197
    6450    6450    3290    4420    5390    9370
River Rch & RM=Black Creek,Upstream        ,48951
    7150    7150    3660    4910    5990   10350
River Rch & RM=Black Creek,Upstream        ,41711
    7280    7280    3730    5000    6100   10530
River Rch & RM=Black Creek,Upstream        ,38341
    7350    7350    3770    5050    6160   10630
River Rch & RM=Black Creek,Upstream        ,36628
    7429    7429    3816    5109    6228   10746
Boundary for River Rch & Prof#=Black Creek,Upstream        , 1
Up Type= 0
Dn Type= 1
Dn Known WS=88.05
Boundary for River Rch & Prof#=Black Creek,Upstream        , 2
Up Type= 0
Dn Type= 1
Dn Known WS=88.69
Boundary for River Rch & Prof#=Black Creek,Upstream        , 3
Up Type= 0
Dn Type= 1
Dn Known WS=84.56
Boundary for River Rch & Prof#=Black Creek,Upstream        , 4
Up Type= 0
Dn Type= 1
Dn Known WS=85.86
Boundary for River Rch & Prof#=Black Creek,Upstream        , 5
Up Type= 0
Dn Type= 1
Dn Known WS=87.05
Boundary for River Rch & Prof#=Black Creek,Upstream        , 6
Up Type= 0
Dn Type= 1
Dn Known WS=90.37
DSS Import GetInterval= 0
DSS Import GetPeak= 0
DSS Import FillOption= 0

--- DTL_Black_Ck_US.f01 (steady flow) ---

Flow Title=dtl_black_crk_upstream_future
Program Version=4.00
Number of Profiles= 3
Profile Names=100-yr-10%,100-yr-20%,100-yr-35%
River Rch & RM=Black Creek,Upstream        ,51978
    5990    7680    9380
River Rch & RM=Black Creek,Upstream        ,50197
    6610    8470   10400
River Rch & RM=Black Creek,Upstream        ,48951
    7290    9340   11400
River Rch & RM=Black Creek,Upstream        ,41711
    7410    9500   11600
River Rch & RM=Black Creek,Upstream        ,38341
    7480    9590   11700
River Rch & RM=Black Creek,Upstream        ,36628
    7560    9690   11800
Boundary for River Rch & Prof#=Black Creek,Upstream        , 1
Up Type= 0
Dn Type= 1
Dn Known WS=88.13
Boundary for River Rch & Prof#=Black Creek,Upstream        , 2
Up Type= 0
Dn Type= 1
Dn Known WS=89.65
Boundary for River Rch & Prof#=Black Creek,Upstream        , 3
Up Type= 0
Dn Type= 1
Dn Known WS=91.01
DSS Import GetInterval= 0
DSS Import GetPeak= 0
DSS Import FillOption= 0

--- DTL_Black_Ck_US.g01 (geometry) ---

Geom Title=dtl_black_crk_upstream
Program Version=4.00

River Reach=Black Creek     ,Upstream
Reach XY= 30
2303529.05967025 687466.981016012303828.86586556 687626.68572849
2304283.21581545688164.0888950682305998.02046514688818.743661597
2306095.73013179688703.9348032922306618.47684839688658.744082451
2306572.06475669688277.6763825422307006.87277325688135.997365892
 2307280.4598399687506.9913868462307613.89407735687180.885374412
2307758.01583564687091.7253036052308020.61056475687095.389416099
2308153.73998554687227.2974660692308405.34237719687139.358766094
2308566.56332715687368.9764827042309315.26364784687702.410720155
2310023.65873103687762.257890984  2310221.520806688245.920740873
2310508.54295176688282.5618658812310572.05423512688475.538457498
2311209.60980998688565.9198991512311524.72348492688388.821128353
2311789.76095568687980.8832700852312748.53705966687736.609103471
2312874.33825547687450.808328539 2312671.5906972686725.314053684
 2312882.8878513686415.0858620552312630.06408885686069.437916294
 2312612.9648972685690.8129580322312790.83264422 685378.29604435

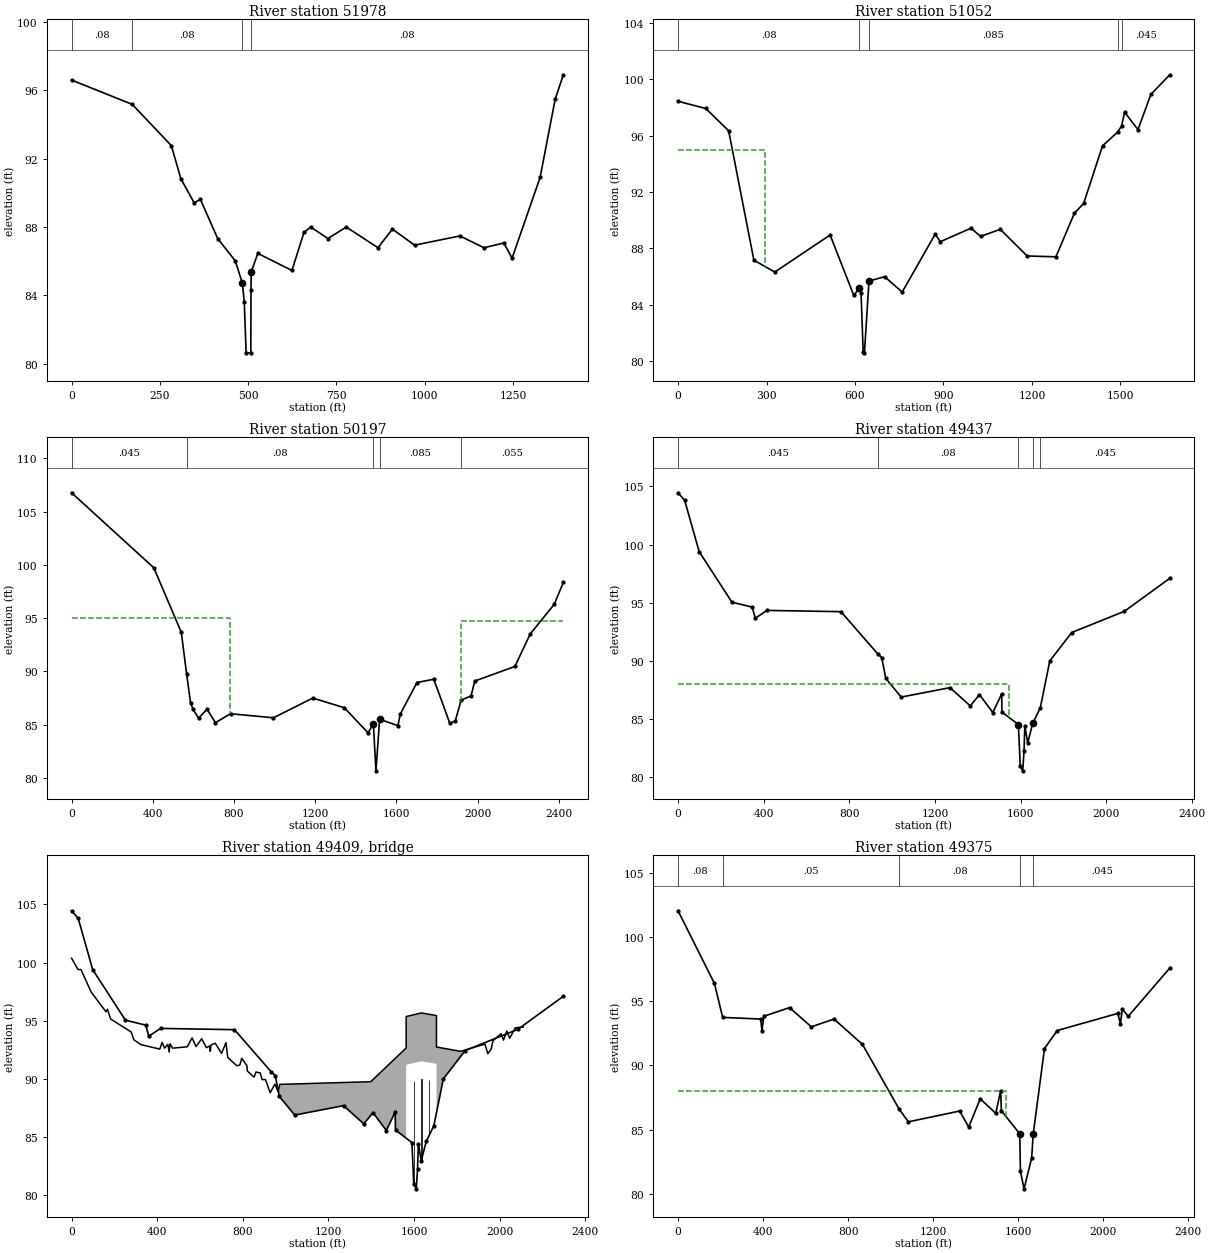
Type RM Length L Ch R = 1 ,51978   ,826.65,926.26,912.16
BEGIN DESCRIPTION:
Tie in Section to LDS Black Creek US (Sta. 51505)
END DESCRIPTION:
XS GIS Cut Line= 3
 2303311.7499911687921.0625178212303621.74997535687520.375045449
2304171.24997114686825.250028625
#Sta/Elev= 30
       0    96.6  171.72   95.18  282.76   92.76  309.23   90.84  347.35   89.41
  364.64   89.63  414.07   87.32  463.75   86.02  483.76   84.71   489.1   83.61
  494.39   80.64  507.59   80.64  508.19   84.34  508.75   85.37   527.4   86.46
  624.03   85.46  658.24   87.69  677.22      88  725.95   87.33  778.03      88
  867.74   86.79  908.63   87.88  971.41   86.94 1099.74   87.48 1167.94   86.79
  1224.3   87.07 1247.51   86.18 1326.86    90.9 1369.48   95.47 1392.69   96.91
#Mann= 4 ,-1 , 0
       0     .08       0  171.72     .08       0  483.76     .05       0
  508.75     .08       0
Bank Sta=483.76,508.75
XS Rating Curve= 0 ,0
Exp/Cntr=0.3,0.1

Type RM Length L Ch R = 1 ,51052   ,920.44,854.52,692.16
XS GIS Cut Line= 6
2303699.35104503688423.1160755012303986.22364351688290.304687321
2304219.97168669688136.2434770462304411.22008564687960.932444647
2304788.40442802687551.8733690982304974.34037146687376.562336698
#Sta/Elev= 30
       0   98.44   93.91   97.93  171.63   96.35  257.19   87.17   328.1   86.33
  515.75   88.96  595.76   84.68  615.15   85.18  620.55   84.83  627.89   80.63
  632.02    80.6   647.5   85.69  700.39      86  760.05   84.91  872.04   89.02
  889.25   88.48  993.26   89.44 1025.93   88.86 1092.71   89.36 1183.69   87.47
 1281.32   87.41    1344    90.5 1375.55    91.2 1439.31   95.28 1491.44   96.27
 1504.11    96.7 1514.39   97.67 1559.53   96.43 1603.42   98.93 1667.53  100.32
#Mann= 5 ,-1 , 0
       0     .08       0  615.15     .05       0   647.5    .085       0
 1491.44    .055       0 1504.11    .045       0
#XS Ineff= 2 , 0
       0     295      95               0
Permanent Ineff=
       F       F
Bank Sta=615.15,647.5
XS Rating Curve= 0 ,0
Exp/Cntr=0.3,0.1

Type RM Length L Ch R = 1 ,50197   ,670.6,759.58,656.5
XS GIS Cut Line= 6
2304453.71972986689809.666967988  2304575.906207689331.545970574
2304852.15389438688662.1765741852305224.02578124687950.307533607
2305404.64926915687684.6847572622305468.39873545687636.872657523
#Sta/Elev= 30
       0  106.77     405   99.73  540.44   93.68  566.83   89.74  586.01   87.08
  598.29   86.44  625.92   85.61  667.05   86.46  708.75   85.19  782.92   86.03
   994.4   85.65 1188.08    87.5 1342.88    86.6 1460.34   84.24 1486.59   85.08
 1499.36   80.67 1517.36   85.51 1607.59   84.91 1619.33   86.01 1701.49   88.96
 1784.34   89.27 1863.12   85.13 1889.95   85.35 1918.98   87.31 1967.77    87.7
 1986.11    89.1 2183.98   90.47 2259.22   93.52 2377.61    96.3 2422.34   98.36
#Mann= 5 ,-1 , 0
       0    .045       0  566.83     .08       0 1486.59     .05       0
 1517.36    .085       0 1918.98    .055       0
#XS Ineff= 2 , 0
       0     782      95    1917       0    94.7
Permanent Ineff=
       F       F
Bank Sta=1486.59,1517.36
XS Rating Curve= 0 ,0
Exp/Cntr=0.5,0.3

Type RM Length L Ch R = 1 ,49437   ,141.38,62.61,66.26
BEGIN DESCRIPTION:
Surveyed Section
END DESCRIPTION:
XS GIS Cut Line= 6
2305179.91611366690199.7513836772305411.51254442689074.085010827
2305476.14410649 688874.804361092305594.64330003688676.972900003
2305737.23564385688364.5993886892305804.26937848688008.295403249
#Sta/Elev= 30
       0  104.45   31.05   103.8   98.69   99.39  251.59   95.05  346.32   94.62
  361.02   93.67  415.76   94.34  761.02   94.23   933.1    90.6  951.46   90.29
  970.36    88.5 1042.36   86.89 1270.37    87.7 1365.24   86.13 1408.14    87.1
 1470.53   85.56 1511.77   87.16 1513.26    85.61589.986   84.531598.639   80.96
1610.141   80.551616.204   82.221620.021   84.421633.586   82.96 1656.81   84.63
1692.217   85.961736.742      90 1839.17   92.44 2084.94   94.26  2297.3    97.1
#Mann= 5 ,-1 , 0
       0    .045       0   933.1     .08       01589.986    .055       0
 1656.81    .085       01692.217    .045       0
#XS Ineff= 2 , 0
       0 1547.99      88 1719.66       0      88
Permanent Ineff=
       F       F
Bank Sta=1589.986,1656.81
XS Rating Curve= 0 ,0
Exp/Cntr=0.5,0.3

Type RM Length L Ch R = 3 ,49409   ,,,
BEGIN DESCRIPTION:
Glory Rd
END DESCRIPTION:
Bridge Culvert--1,0,-1,-1, 0
Deck Dist Width WeirC Skew NumUp NumDn MinLoCord MaxHiCord MaxSubmerge Is_Ogee
13.8,29,2.6,0, 60, 60, , , 0.95, 0, 0,0,,
       0   30.06   43.92   91.12  160.63  167.58  182.93  278.61  290.58  323.31
  412.06     423  434.28  449.61  455.93  459.86  472.25  540.51  563.01   581.4
  607.92  629.76  644.05   647.8  651.77  671.39  700.56  721.42  729.56  771.86
  786.06  794.74  819.21  821.04  852.67  861.39  881.19  890.21  906.01  927.68
  949.85  964.64  972.97 1397.791562.9921562.9921634.3591704.6611704.6611817.793
1931.115 1944.55 1960.24 1968.66 2006.33 2017.85 2033.09 2046.61 2073.07 2110.44
  100.37    99.4    99.4   97.48   95.77   95.98   95.14   94.03   93.37   92.95
   92.56   93.14   92.64   92.97   92.31   93.01   92.64   92.76   93.53   92.78
   93.45   92.68   92.83   92.37   92.93   93.06   92.19   93.12   91.85   91.13
   91.19   91.77   91.14   90.68   90.15   90.59   90.52   89.94   89.94   88.81
   89.55    88.9   89.53   89.76   92.66   95.36   95.67   95.44   92.74   92.37
   92.99   92.17   92.56   93.29   93.88   93.33   94.12   93.49    94.4   94.45
                                                                                
                                                                                
                                                                                
                                                                                
                                           91.21   91.52   91.29
                                                                                
       0   30.06   43.92   91.12  160.63  167.58  182.93  278.61  290.58  323.31
  412.06     423  434.28  449.61  455.93  459.86  472.25  540.51  563.01   581.4
  607.92  629.76  644.05   647.8  651.77  671.39  700.56  721.42  729.56  771.86
  786.06  794.74  819.21  821.04  852.67  861.39  881.19  890.21  906.01  927.68
  949.85  964.64  972.97 1397.791562.9921562.9921634.3591704.6611704.6611817.793
1931.115 1944.55 1960.24 1968.66 2006.33 2017.85 2033.09 2046.61 2073.07 2110.44
  100.37    99.4    99.4   97.48   95.77   95.98   95.14   94.03   93.37   92.95
   92.56   93.14   92.64   92.97   92.31   93.01   92.64   92.76   93.53   92.78
   93.45   92.68   92.83   92.37   92.93   93.06   92.19   93.12   91.85   91.13
   91.19   91.77   91.14   90.68   90.15   90.59   90.52   89.94   89.94   88.81
   89.55    88.9   89.53   89.76   92.66   95.36   95.67   95.44   92.74   92.37
   92.99   92.17   92.56   93.29   93.88   93.33   94.12   93.49    94.4   94.45
                                                                                
                                                                                
                                                                                
                                                                                
                                           91.21   91.52   91.29
                                                                                
Pier Skew, UpSta & Num, DnSta & Num=  ,1598.619, 2 ,1598.619, 2 , 2 , 2 , 0 ,,
       1     2.5
      80  89.846
       1     2.5
      80  89.846
Pier Skew, UpSta & Num, DnSta & Num=  ,1634.359, 2 ,1634.359, 2 , 2 , 2 , 0 ,,
       1     2.5
      80  89.965
       1     2.5
      80  89.965
Pier Skew, UpSta & Num, DnSta & Num=  ,1669.913, 2 ,1669.913, 2 , 2 , 2 , 0 ,,
       1     2.5
      80   89.87
       1     2.5
      80   89.87
Abutment Skew #Up #Dn= , 2 , 2
 1562.99 1575.34
   91.21   84.88
 1562.99  1578.8
   91.21    85.4
Abutment Skew #Up #Dn= , 2 , 2
  1686.6 1704.66
   85.76   91.29
  1686.6 1704.66
   85.76   91.29
BR Coef=-1 , 0 , 0 ,, 0 ,,,0.8,0,,0,
WSPro=,,,, 1 ,,,, 0 ,,,, 0 ,,,,-1 ,-1 ,-1 , 0 , 0 , 0 , 0 , 0
BC Design=,, 0 ,, 0 ,,,,,,
BC Use User HTab Curves=0
BC User HTab FreeFlow(D)= 0

Type RM Length L Ch R = 1 ,49375   ,560.78,423.75,253.25
BEGIN DESCRIPTION:
Surveyed Section
END DESCRIPTION:
XS GIS Cut Line= 6
2305286.56593998690227.7538641692305539.68153568689160.563785076
2305620.88620003688745.5658999982305813.30333915688384.609666437
2305867.64214367 688169.304969492305871.74318546688011.414858416
#Sta/Elev= 30
       0  102.03   171.3   96.38   209.9   93.74  388.76   93.61  394.64   92.72
  403.84   93.83  524.39    94.5  626.95   93.01  733.79   93.61  866.96   91.65
 1040.67   86.59 1083.48   85.62  1324.5   86.46 1367.14   85.22 1421.38   87.41
 1494.33   86.28 1517.27   88.021521.014   86.481607.196   84.691610.401   81.79
1627.443   80.411663.172    82.81670.568   84.671723.602   91.32 1783.67   92.72
 2068.28   94.05 2080.76   93.24 2089.66   94.39 2117.53   93.82    2313   97.58
#Mann= 5 ,-1 , 0
       0     .08       0   209.9     .05       0 1040.67     .08       0
1607.196    .055       01670.568    .045       0
#XS Ineff= 2 , 0
       0 1542.99      88 1724.66       0      88
Permanent Ineff=
       F       F
Bank Sta=1607.196,1670.568
XS Rating Curve= 0 ,0
Exp/Cntr=0.5,0.3

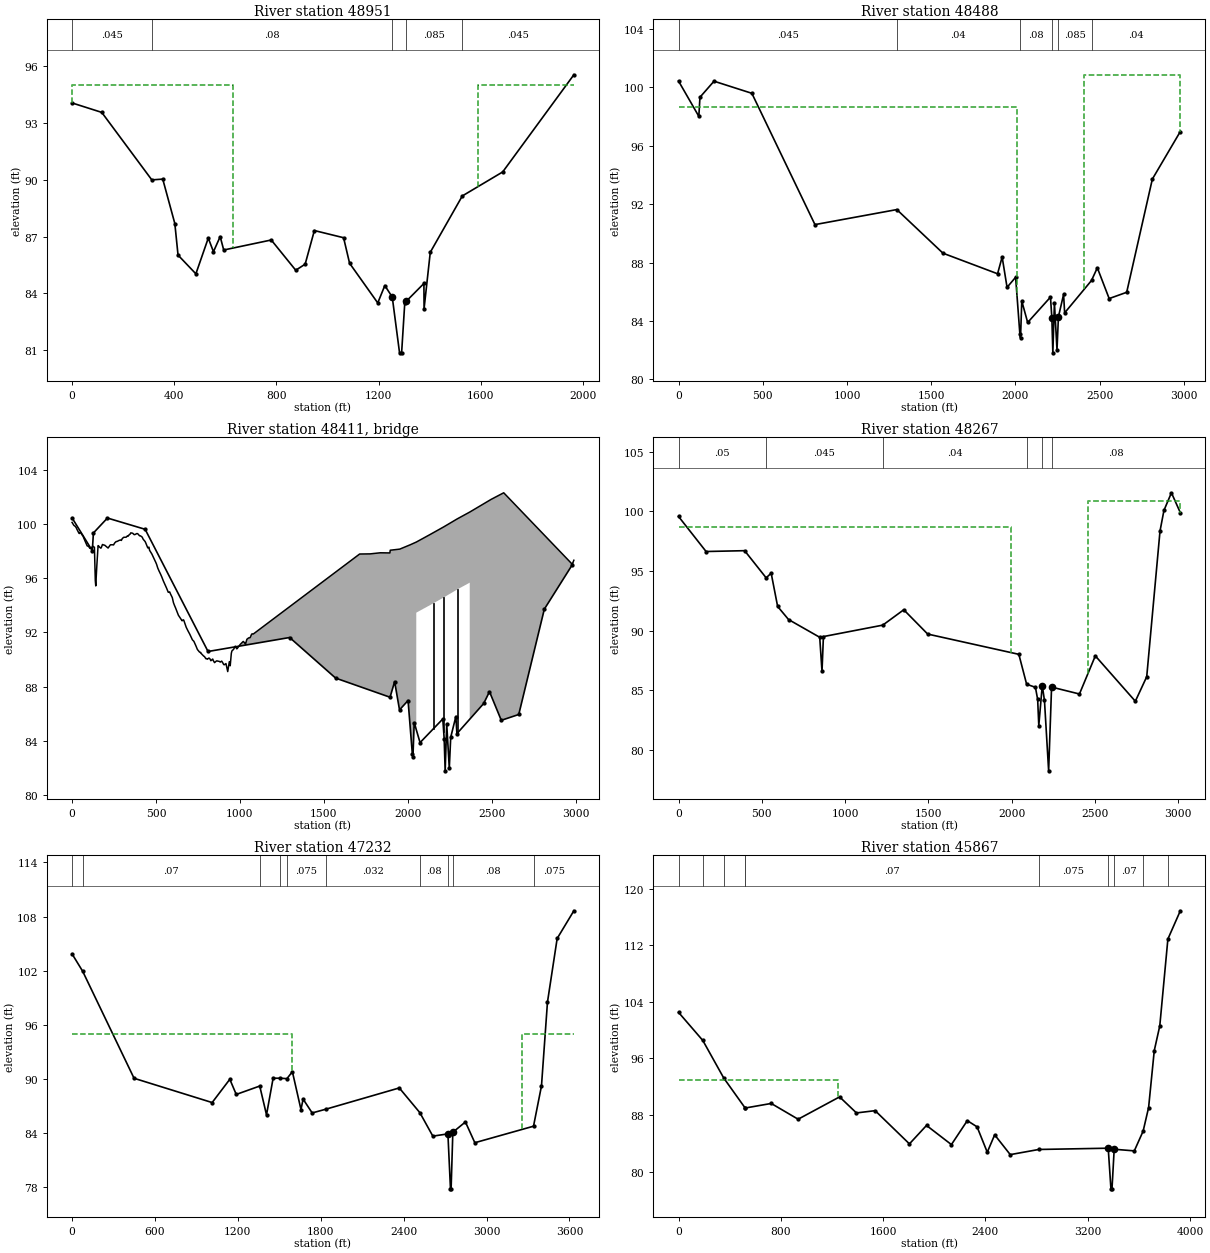
Type RM Length L Ch R = 1 ,48951   ,530.26,463.3,231.01
XS GIS Cut Line= 6
2306261.99152152690070.3253749912306167.20551153689711.136284396
2306072.41950151688987.7693658322306012.55465308688663.501436815
2306007.56591567 688419.053305732306012.55465308 688129.70653832
#Sta/Elev= 30
       0   94.07  116.24   93.57  312.19      90  355.05   90.04  402.35   87.69
  414.91   86.02  484.75   85.03   533.3   86.92  553.57    86.2  579.93      87
  593.71   86.29  779.88   86.82  875.73   85.22  912.61   85.54  948.69   87.32
 1063.05   86.94 1086.54   85.59 1196.86   83.49 1224.55   84.41 1253.66    83.8
 1282.19   80.85 1290.29   80.85 1302.53   83.47 1309.26   83.59 1377.58   84.52
  1378.2   83.19 1402.52   86.17 1527.93   89.15 1686.05   90.42 1964.68   95.56
#Mann= 5 ,-1 , 0
       0    .045       0  312.19     .08       0 1253.66     .05       0
 1309.26    .085       0 1527.93    .045       0
#XS Ineff= 2 , 0
       0     630      95    1590       0      95
Permanent Ineff=
       F       F
Bank Sta=1253.66,1309.26
XS Rating Curve= 0 ,0
Exp/Cntr=0.5,0.3

Type RM Length L Ch R = 1 ,48488   ,198.46,220.84,235.97
BEGIN DESCRIPTION:
Surveyed Section
END DESCRIPTION:
XS GIS Cut Line= 6
2307466.55967234690647.5451861472306992.51730318689682.919866383
2306795.63268515689351.4304584262306537.96590003688843.676400021
2306283.57119998688533.0691000072306032.76765564688059.047854856
#Sta/Elev= 30
       0  100.44  120.52   98.02  127.17   99.33  210.64  100.43  435.29    99.6
  810.01    90.6 1296.04   91.63 1570.08   88.64 1894.27   87.23 1921.45   88.38
1950.602    86.32001.488   86.992026.819   83.082030.562   82.832038.064   85.36
    2073   83.892208.423   85.63 2216.64   84.192222.463   81.812231.857   85.24
2247.108   82.012255.553   84.282286.218   85.812292.536   84.55 2452.04   86.77
 2486.59   87.64 2556.87   85.53 2660.93   85.96 2813.31   93.72 2979.39   96.98
#Mann= 6 ,-1 , 0
       0    .045       0 1296.04     .04       02026.819     .08       0
 2216.64     .05       02255.553    .085       0 2452.04     .04       0
#XS Ineff= 2 , 0
       0    2010   98.66    2408       0  100.87
Permanent Ineff=
       F       F
Bank Sta=2216.64,2255.553
XS Rating Curve= 0 ,0
Exp/Cntr=0.5,0.3

Type RM Length L Ch R = 3 ,48411   ,,,
BEGIN DESCRIPTION:
I-795
END DESCRIPTION:
Bridge Culvert--1,0,-1,-1, 0
Deck Dist Width WeirC Skew NumUp NumDn MinLoCord MaxHiCord MaxSubmerge Is_Ogee
47,130,2.6,0, 191, 94, , , 0.98, 0, 1,1,,
       0    9.58   13.74   17.21   24.28   29.33   39.91   41.03    43.3   50.53
   55.92   60.76   63.93   77.88    87.3   90.43   97.47    99.9  105.71  110.68
  119.53  123.09  127.63  133.11  138.42  141.11  147.67  154.96  160.65  164.14
  171.67  174.64  180.98  189.36  194.35  214.49  228.41  241.61  247.33  251.62
  255.88  262.79  266.16  268.89  281.56  288.62  293.51  299.23  307.51  322.34
   329.4  333.41  341.09  346.21  349.87  360.22  361.16  369.55  374.05  386.35
   391.5  402.29  407.06   413.6  414.04  417.93  423.51  435.15  438.58  451.03
  457.62  461.86   475.3  489.33  495.11  498.79  503.53  510.42  518.47  526.72
  534.18  543.01  543.59  562.07  562.71  562.84  572.36  573.12  580.65  581.86
  585.58     597  604.05   609.6  617.13  633.43  640.61   643.2  643.66  655.41
  657.56  663.74  665.45  675.38  680.07  691.74  700.93  711.38  716.83  725.51
  726.71  737.66  738.29  738.94  746.54  758.37  764.58  766.28  769.39   784.1
  788.58  796.94  802.64  805.92   815.6   821.2  826.87  836.93  837.95  841.11
  848.68  859.67  863.63  868.16   874.3  878.83  882.53  891.39  898.45  903.17
  906.87  916.72  927.22  936.76  942.12  948.63  951.65  955.08  960.54  970.05
  971.69  972.63  980.68  983.02 1000.11 1001.15  1001.6 1019.58 1029.88 1032.84
 1035.31 1041.11 1043.11 1051.74 1060.61 1069.48 1072.66  1079.81712.6361712.966
1775.2981775.3251835.5781892.9181893.1541895.4011951.7882014.3362050.4132050.413
2133.1232214.0942294.7322368.8262368.8262434.5312497.1122497.1252571.341 2979.39
 2989.16
  100.11   99.91   99.86   99.84   99.73   99.59   99.34   99.31   99.29   99.38
   99.26   99.17   99.14   98.72   98.47   98.37   98.36   98.31    98.2   98.21
   98.29   98.37   98.31   98.28   95.82   95.43   96.95    98.4   98.34   98.28
   98.21   98.27   98.48   98.44   98.43   98.22   98.46   98.46   98.45   98.55
   98.62    98.7    98.7   98.71   98.79   98.81   98.78   98.92   99.01   99.02
   99.11   99.09   99.21   99.25   99.34   99.32   99.31   99.21   99.21   99.29
   99.27   99.12   99.12   99.07   99.06   99.02   98.87    98.7   98.61   98.23
   98.29   98.05   97.78   97.42   97.28   97.16   97.02   96.75   96.52   96.31
    96.1   95.82    95.8   95.29   95.27   95.27   94.97   94.96   94.99   94.98
   94.86   94.57   94.19   94.01   93.79   93.27   93.13   93.09   93.08   92.86
   92.89   92.93    92.9   92.56   92.38   92.09   91.88   91.61   91.46   91.35
   91.32   91.02   91.01   90.98   90.75   90.57   90.52   90.53   90.45   90.26
   90.23   90.07   90.08   90.03   90.12   90.06   89.92   90.04   90.04   89.94
   89.78    89.9   89.91   89.89   89.88   89.86   89.82   89.89   89.75   89.64
   89.62   89.71   89.12   89.85   89.55   90.46   90.62   90.69   90.73   90.93
   90.99   90.99    90.8   90.81    91.1   91.11   91.12   91.34   91.22   91.13
   91.24   91.49   91.52    91.6   91.62   91.87    91.9   91.89   97.78   97.78
   97.79   97.79   97.87   97.86   97.86   98.06   98.14   98.46   98.66   98.66
   99.22   99.78  100.37  100.87  100.87  101.35  101.81  101.81  102.29   97.03
   97.32
                                                                                
                                                                                
                                                                                
                                                                                
                                                                                
                                                                                
                                                                                
                                                                                
                                                                                
                                                                                
                                                                                
                                                                                
                                                                                
                                                                                
                                                                                
                                                                                
                                                                                
                                                                           93.46
   94.02   94.58   95.17   95.67
        
       0    9.58   13.74   17.21   24.28   29.33   39.91   41.03    43.3   50.53
   55.92   60.76   63.93   77.88    87.3   90.43   97.47    99.9  105.71  110.68
  119.53  123.09  127.63  133.11  138.42  141.11  147.67  154.96  160.65  164.14
  171.67  174.64  180.98  189.36  194.35  214.49  228.41  241.61  247.33  251.62
  255.88  262.79  266.16  268.89  281.56  288.62  293.51  299.23  307.51  322.34
   329.4  333.41  341.09  346.21  349.87  360.22  361.16  369.55  374.05  386.35
1772.1941830.3021888.9381951.0412009.601 2069.572069.572 2152.522233.3892315.582
2315.9692388.2642388.2642423.2212482.2242542.3352603.586 2844.18 2850.45 2862.47
 2866.04  2883.7 2884.27    2895 2906.82 2910.88  2914.8 2925.98  2930.8 2934.64
 2943.37 2949.05 2970.97 2989.16
  100.11   99.91   99.86   99.84   99.73   99.59   99.34   99.31   99.29   99.38
   99.26   99.17   99.14   98.72   98.47   98.37   98.36   98.31    98.2   98.21
   98.29   98.37   98.31   98.28   95.82   95.43   96.95    98.4   98.34   98.28
   98.21   98.27   98.48   98.44   98.43   98.22   98.46   98.46   98.45   98.55
   98.62    98.7    98.7   98.71   98.79   98.81   98.78   98.92   99.01   99.02
   99.11   99.09   99.21   99.25   99.34   99.32   99.31   99.21   99.21   99.29
   97.63   97.59   97.75   97.92   98.28   98.71   98.71   99.24    99.8  100.44
  100.44  100.91  100.91  101.14  101.61  102.02  102.37   94.04   94.09   93.36
    93.5   94.56   94.54   94.07   94.97   95.47   95.53    95.6   95.84   95.98
   95.95   96.09   96.78   97.32
                                                                                
                                                                                
                                                                                
                                                                                
                                                                                
                                                                                
                                                   93.51   94.04    94.6   95.24
   95.24   95.71
                                                                                
                                
Pier Skew, UpSta & Num, DnSta & Num=  ,2152.52, 2 ,2133.123, 2 , 0 , 0 , 0 ,,
     3.4     3.4
      75   95.67
     3.4     3.4
      75   95.67
Pier Skew, UpSta & Num, DnSta & Num=  ,2214.094, 2 ,2233.389, 2 , 0 , 0 , 0 ,,
     3.4     3.4
      75   95.67
     3.4     3.4
      75   95.67
Pier Skew, UpSta & Num, DnSta & Num=  ,2294.732, 2 ,2315.582, 2 , 0 , 0 , 0 ,,
     3.4     3.4
      75   95.67
     3.4     3.4
      75   95.67
Abutment Skew #Up #Dn= , 2 , 2
 2050.41 2066.68
   93.46    84.9
 2069.57 2092.48
   93.51   85.43
Abutment Skew #Up #Dn= , 2 , 2
 2336.89 2368.83
   85.04   95.67
  2354.6 2388.64
   84.98   95.71
BR Coef=-1 , 0 , 0 ,, 0 ,,,0.8,0,,0,
WSPro=,,,, 1 ,,,, 0 ,,,, 0 ,,,,-1 ,-1 ,-1 , 0 , 0 , 0 , 0 , 0
BC Design=,, 0 ,, 0 ,,,,,,
BC Use User HTab Curves=0
BC User HTab FreeFlow(D)= 0

Type RM Length L Ch R = 1 ,48267   ,686.51,1034.46,611.7
BEGIN DESCRIPTION:
Surveyed Section
Surveyed Section
END DESCRIPTION:
XS GIS Cut Line= 6
2307697.41057102 690590.720349552307489.05283685690091.135327771
 2307304.1425506689722.3813328892306828.99549998688953.091299996
2306655.10990003688726.7831999962306235.67231962687967.257649705
#Sta/Elev= 30
       0   99.58   165.4   96.64  397.01   96.71  526.26   94.43  556.43   94.82
  595.24   92.03  660.76   90.93  848.02   89.44  861.75   86.58  870.23    89.5
 1226.72   90.46 1352.85   91.75 1496.61   89.712044.074   88.012090.855    85.5
2143.755   85.242157.127   84.222163.911   82.032184.725   85.392197.972   84.14
 2223.07   78.232240.669   85.262408.064   84.682503.473   87.88 2743.83   84.07
 2812.23   86.13 2892.04   98.36 2915.65  100.09 2960.63  101.57 3014.06    99.9
#Mann= 6 ,-1 , 0
       0     .05       0  526.26    .045       0 1226.72     .04       0
2090.855     .08       02184.725    .053       02240.669     .08       0
#XS Ineff= 2 , 0
       0    1999   98.71    2458       0  100.91
Permanent Ineff=
       F       F
Bank Sta=2184.725,2240.669
XS Rating Curve= 0 ,0
Exp/Cntr=0.5,0.3

Type RM Length L Ch R = 1 ,47232   ,686.81,1365.92,1172.9
XS GIS Cut Line= 6
2308315.87489781690505.5986420212307965.25283308689894.666256413
2307821.81653388689437.7950810942307359.63290299688534.677641541
2306759.32542849687684.6847572622306504.39972399 687396.28186509
#Sta/Elev= 30
       0  103.86   76.63  101.94   448.7   90.08 1013.85   87.39 1141.73   89.97
 1188.29   88.29 1358.32   89.22 1407.31   86.03 1455.22   90.09 1507.5990.08662
 1555.17   90.04 1594.65   90.81 1656.72   86.62  1672.3   87.77 1737.82   86.24
 1838.09   86.66 2368.31   89.01 2517.25   86.27 2611.18   83.67 2720.28   83.92
 2738.84   77.83 2743.44   77.83 2755.87    84.1 2847.01   85.24 2915.15   82.94
 3339.87   84.77 3397.57   89.24 3440.88   98.52 3511.03  105.57 3631.88  108.64
#Mann= 10 ,-1 , 0
       0    .045       0   76.63     .07       0 1358.32    .075       0
 1507.59    .045       0 1555.17    .075       0 1838.09    .032       0
 2517.25     .08       0 2720.28    .053       0 2755.87     .08       0
 3339.87    .075       0
#XS Ineff= 2 , 0
       0    1595      95    3260       0      95
Permanent Ineff=
       F       F
Bank Sta=2720.28,2755.87
XS Rating Curve= 0 ,0
Exp/Cntr=0.3,0.1

Type RM Length L Ch R = 1 ,45867   ,458.81,673.06,569.96
XS GIS Cut Line= 6
2308613.13740315690357.0217974632308253.42808716689524.923138738
2308067.07265837688467.4644266222307802.70798038687214.982591376
2307703.02949524687041.6287041462307395.32634537 686694.92092967
#Sta/Elev= 30
       0  102.52  189.95   98.54  353.21   93.24  520.39      89  523.14   88.99
  724.91   89.63  935.29    87.4 1259.53   90.56 1391.49   88.29 1537.71   88.61
 1805.87   83.91 1939.39   86.52 2134.14   83.81 2258.45    87.2 2334.88   86.32
 2414.57   82.73 2472.51   85.19  2594.4   82.39  2817.4   83.12 3360.56    83.3
 3381.82   77.55 3390.06   77.55 3407.2683.15139 3564.62   82.92  3633.7   85.72
 3676.39   89.05 3720.71   97.11 3763.84  100.61 3827.18  112.89 3924.51  116.89
#Mann= 10 ,-1 , 0
       0    .045       0  189.95     .09       0  353.21     .07       0
  520.39     .09       0  523.14     .07       0  2817.4    .075       0
 3360.56     .05       0 3407.26     .07       0  3633.7     .09       0
 3827.18    .045       0
#XS Ineff= 2 , 0
       0    1250      93               0
Permanent Ineff=
       F       F
Bank Sta=3360.56,3407.26
XS Rating Curve= 0 ,0
Exp/Cntr=0.3,0.1

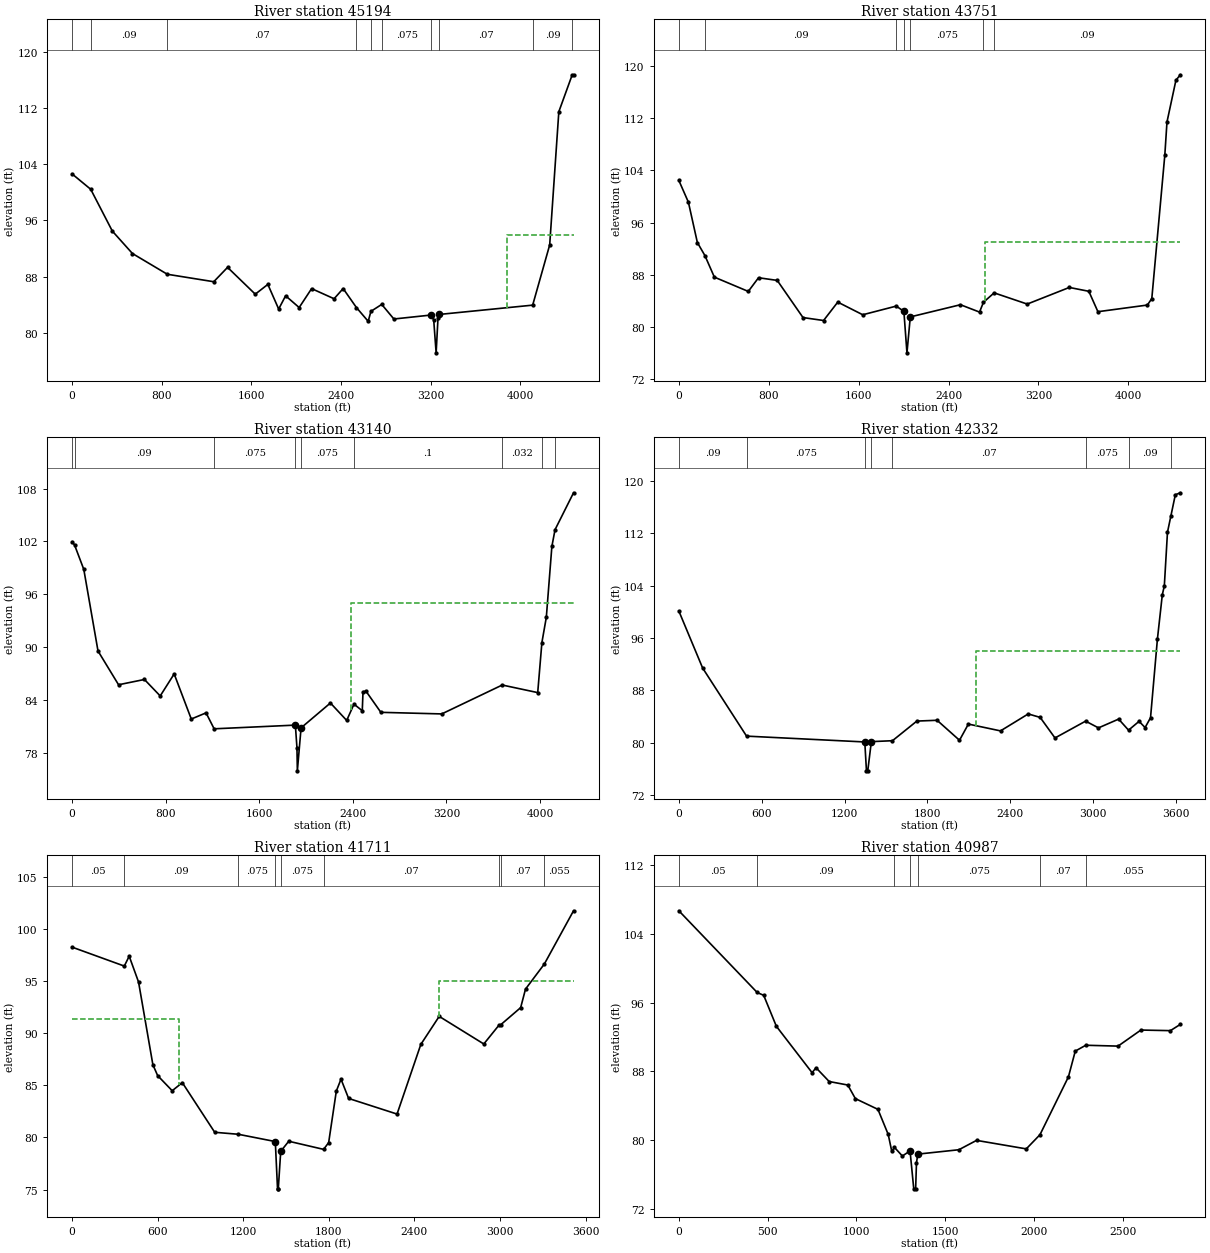
Type RM Length L Ch R = 1 ,45194   ,1088.57,1442.36,1017.75
XS GIS Cut Line= 6
2308932.11973894690351.5374317172308501.81084129688359.366609171
2308390.24927521687620.9352909332308257.43788703687068.439916164
 2307997.1275662686446.8826195152307646.68948184 686161.85772644
#Sta/Elev= 30
       0  102.62  166.67  100.43  359.47   94.49  538.87    91.3  850.39   88.35
  1264.7   87.29 1388.04   89.33 1635.27   85.52 1747.56   86.91 1844.16   83.41
 1906.17   85.29 2027.03   83.62 2138.17   86.31 2338.84   84.87 2419.65   86.32
 2538.17   83.62 2643.22   81.66 2667.66   83.08 2763.9984.06424 2872.48   81.99
    3208   82.56 3228.17   81.81  3249.6   77.18 3266.28   82.12 3277.89   82.64
 4111.26   83.96 4263.17   92.52 4344.75  111.46 4464.32  116.71 4476.04  116.67
#Mann= 10 ,-1 , 0
       0    .045       0  166.67     .09       0  850.39     .07       0
 2538.17    .075       0 2667.66     .07       0 2763.99    .075       0
    3208     .05       0 3277.89     .07       0 4111.26     .09       0
 4464.32    .045       0
#XS Ineff= 2 , 0
       0                    3885       0      94
Permanent Ineff=
       F       F
Bank Sta=3208,3277.89
XS Rating Curve= 0 ,0
Exp/Cntr=0.3,0.1

Type RM Length L Ch R = 1 ,43751   ,574.57,610.71,885.23
XS GIS Cut Line= 6
2309720.11868393689708.6052393172309616.90431096688921.595645383
2309384.67197178687554.0052034712309242.75220893686986.326152101
2308952.46178497686076.749490261 2308543.7958483685459.774483159
#Sta/Elev= 30
       0  102.46   85.06   99.12  164.72   92.94  232.07   90.93  316.09   87.63
  617.86   85.44     709   87.54  875.55   87.13 1104.79   81.43 1287.81   80.98
 1414.16    83.8 1636.45   81.86 1934.63   83.19 2002.47   82.38 2029.91   76.02
 2059.59   81.53 2506.02    83.4 2675.83   82.27 2710.72   83.78 2805.7885.21808
 3100.28    83.5 3474.78   86.05 3648.42   85.46 3729.27   82.33 4169.33   83.35
 4208.86   84.34 4324.68  106.35 4343.92  111.43 4423.48  117.83 4462.82  118.67
#Mann= 7 ,-1 , 0
       0    .045       0  232.07     .09       0 1934.63    .075       0
 2002.47     .05       0 2059.59    .075       0 2710.72      .1       0
 2805.78     .09       0
#XS Ineff= 2 , 0
       0                    2722       0      93
Permanent Ineff=
       F       F
Bank Sta=2002.47,2059.59
XS Rating Curve= 0 ,0
Exp/Cntr=0.3,0.1

Type RM Length L Ch R = 1 ,43140   ,305.9,807.95,1201.52
XS GIS Cut Line= 6
2309945.90012485 689656.998052852310016.86000627689418.314815328
2310100.72168429688463.5818653112310016.86000627688070.077068344
2309784.62766704 686096.102185192309843.95000251685412.102164164
#Sta/Elev= 30
       0  101.96   21.01  101.61  100.46   98.82  221.95   89.56  397.55   85.73
  618.75   86.33  753.67   84.46  872.99   86.96 1019.26   81.84 1145.51   82.54
 1214.56   80.73 1909.08   81.15 1922.72   78.57 1926.07   75.96 1957.96   80.84
 2208.82   83.66 2347.87   81.68 2410.26   83.53 2481.03   82.78 2487.41   84.93
 2512.92      85 2639.96    82.6 3160.44   82.42 3677.55    85.7 3980.95   84.84
 4016.66   90.52 4054.55   93.39 4101.97  101.43 4128.99  103.33 4287.19  107.52
#Mann= 9 ,-1 , 0
       0    .045       0   21.01     .09       0 1214.56    .075       0
 1909.08     .05       0 1957.96    .075       0 2410.26      .1       0
 3677.55    .032       0 4016.66     .09       0 4128.99    .045       0
#XS Ineff= 2 , 0
       0                    2388       0      95
Permanent Ineff=
       F       F
Bank Sta=1909.08,1957.96
XS Rating Curve= 0 ,0
Exp/Cntr=0.3,0.1

Type RM Length L Ch R = 1 ,42332   ,495.92,621.08,436.06
XS GIS Cut Line= 6
2310249.09234546689637.6453579222310365.20851508689231.238764331
2310371.65941334 688476.483661922310545.83366774687753.983051121
2310700.65522723686405.745304123 2310866.7379372 686092.51617153
#Sta/Elev= 30
       0  100.13  172.25   91.43  490.51   81.03 1346.92   80.14  1359.1   75.73
 1368.49   75.73 1394.51   80.19 1547.48   80.33 1724.24   83.33 1870.77   83.45
 2033.09    80.4 2097.43   82.87 2330.21   81.83 2531.04   84.42 2617.42   83.89
 2724.91   80.75 2946.72   83.32 3039.99   82.29 3185.89   83.63 3257.74   81.94
 3334.01   83.29 3377.59   82.34 3416.97   83.84 3466.87   95.85  3502.5  102.64
 3516.94  103.96 3539.81  112.17 3563.68  114.57 3596.63  117.89 3632.98  118.19
#Mann= 8 ,-1 , 0
       0     .09       0  490.51    .075       0 1346.92     .05       0
 1394.51    .075       0 1547.48     .07       0 2946.72    .075       0
 3257.74     .09       0 3563.68    .055       0
#XS Ineff= 2 , 0
       0                 2152.17       0      94
Permanent Ineff=
       F       F
Bank Sta=1346.92,1394.51
XS Rating Curve= 0 ,0
Exp/Cntr=0.3,0.1

Type RM Length L Ch R = 1 ,41711   ,866.94,724.45,553.14
XS GIS Cut Line= 6
 2310962.0825752689988.6447870882310849.40254848689399.241570503
2310845.06870133688705.8260215822310914.41025618687579.025754556
2310944.74718647687349.3318539862311217.77955884 686538.90243116
#Sta/Elev= 30
       0   98.28  366.29   96.46  400.52   97.41  466.12   94.93  566.52   86.99
  600.09   85.94  702.08   84.49  772.84   85.27  999.99    80.5 1164.96   80.31
 1424.74   79.61 1440.32   75.07 1445.83    75.1 1462.71   78.67 1518.97   79.64
 1763.26   78.86 1798.72   79.51 1852.49   84.46 1885.32    85.6 1938.64   83.75
 2278.07   82.25 2444.86   88.94 2573.64   91.63 2886.25   88.98 2994.66   90.82
 3003.45   90.81 3144.57   92.47 3178.62   94.25 3310.69   96.66 3515.28  101.77
#Mann= 9 ,-1 , 0
       0     .05       0  366.29     .09       0 1164.96    .075       0
 1424.74     .05       0 1462.71    .075       0 1763.26     .07       0
 2994.66    .055       0 3003.45     .07       0 3310.69    .055       0
#XS Ineff= 2 , 0
       0     750   91.35    2573       0      95
Permanent Ineff=
       F       F
Bank Sta=1424.74,1462.71
XS Rating Curve= 0 ,0
Exp/Cntr=0.3,0.1

Type RM Length L Ch R = 1 ,40987   ,997.87,1036.48,807.39
XS GIS Cut Line= 6
2312074.69656748689579.5872731062311694.09356712688676.461509585
2311487.66482116688315.2112041712311281.23607522687515.299813598
2311268.33427857687347.5764575152311330.45958555686920.280983105
#Sta/Elev= 30
       0   106.7  441.08   97.19  477.77   96.86     549   93.26  750.16   87.86
  772.57   88.43  846.43   86.83  951.35   86.42  993.95   84.84 1120.98   83.59
  1178.9   80.67 1199.02   78.69 1214.23   79.16 1258.68   78.16 1301.77   78.76
  1322.7   74.34 1333.28   74.34 1338.09   77.39 1345.54   78.38 1576.75   78.89
 1676.32   79.98 1956.24   78.99 2033.41   80.64 2193.59   87.37 2232.17   90.37
 2291.22   91.05 2473.07   90.95 2601.72   92.82 2767.82   92.75 2823.79   93.48
#Mann= 7 ,-1 , 0
       0     .05       0  441.08     .09       0 1214.23    .075       0
 1301.77     .05       0 1345.54    .075       0 2033.41     .07       0
 2291.22    .055       0
Bank Sta=1301.77,1345.54
XS Rating Curve= 0 ,0
Exp/Cntr=0.3,0.1