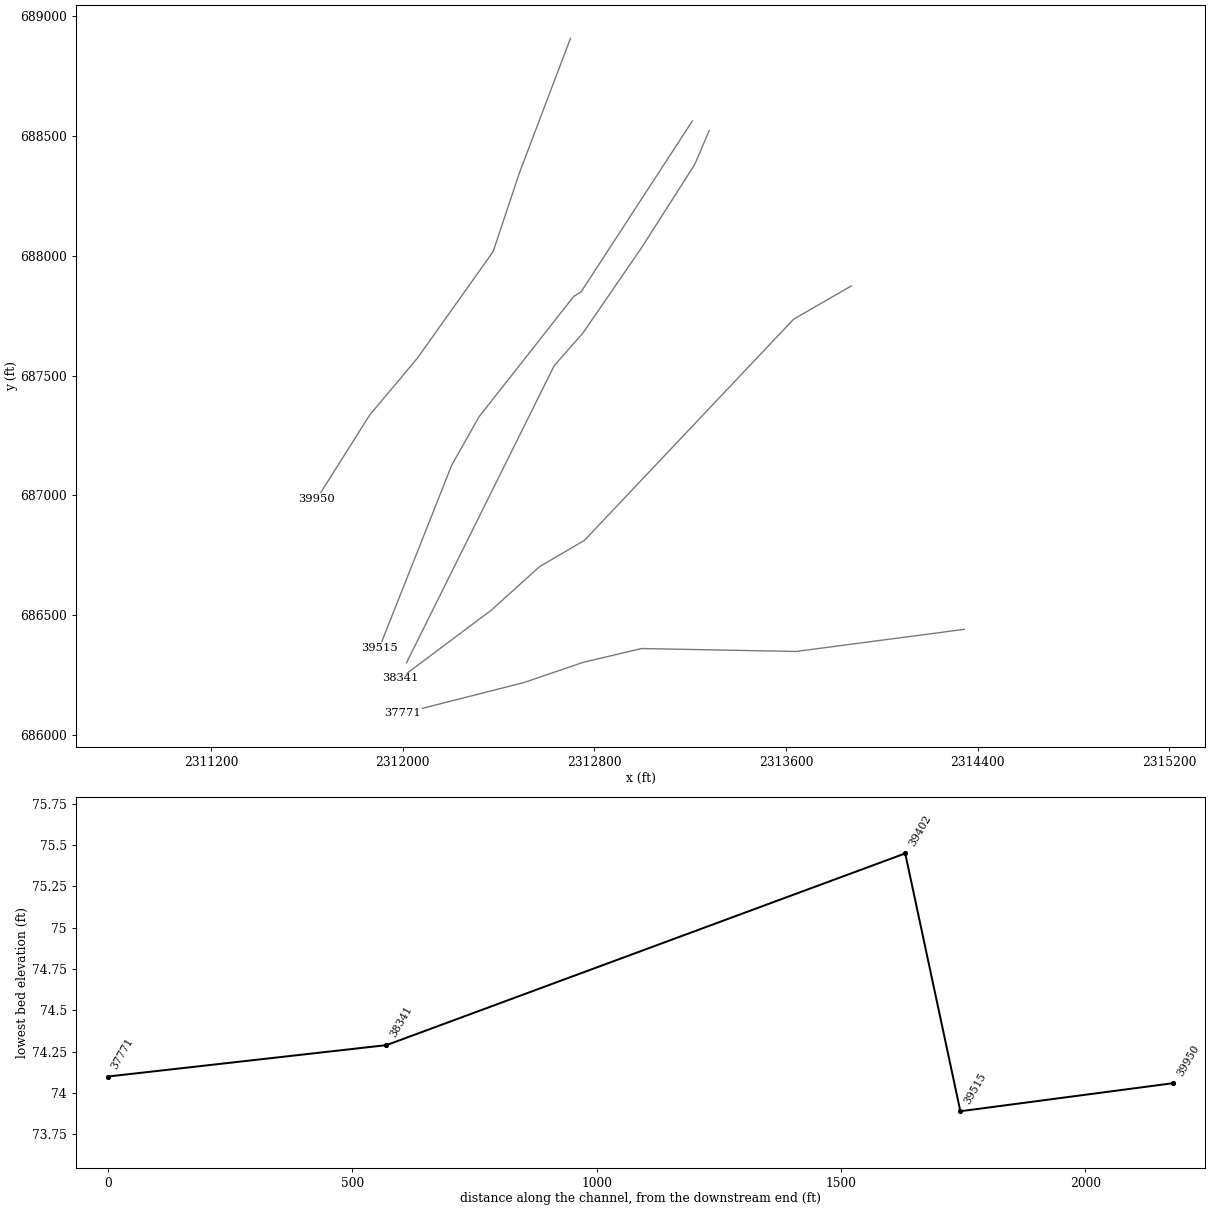
HEC-RAS study DTL_Black_Ck_US.prj: dtl_black_crk_upstream

--- DTL_Black_Ck_US.g01 (geometry) --- (continued)

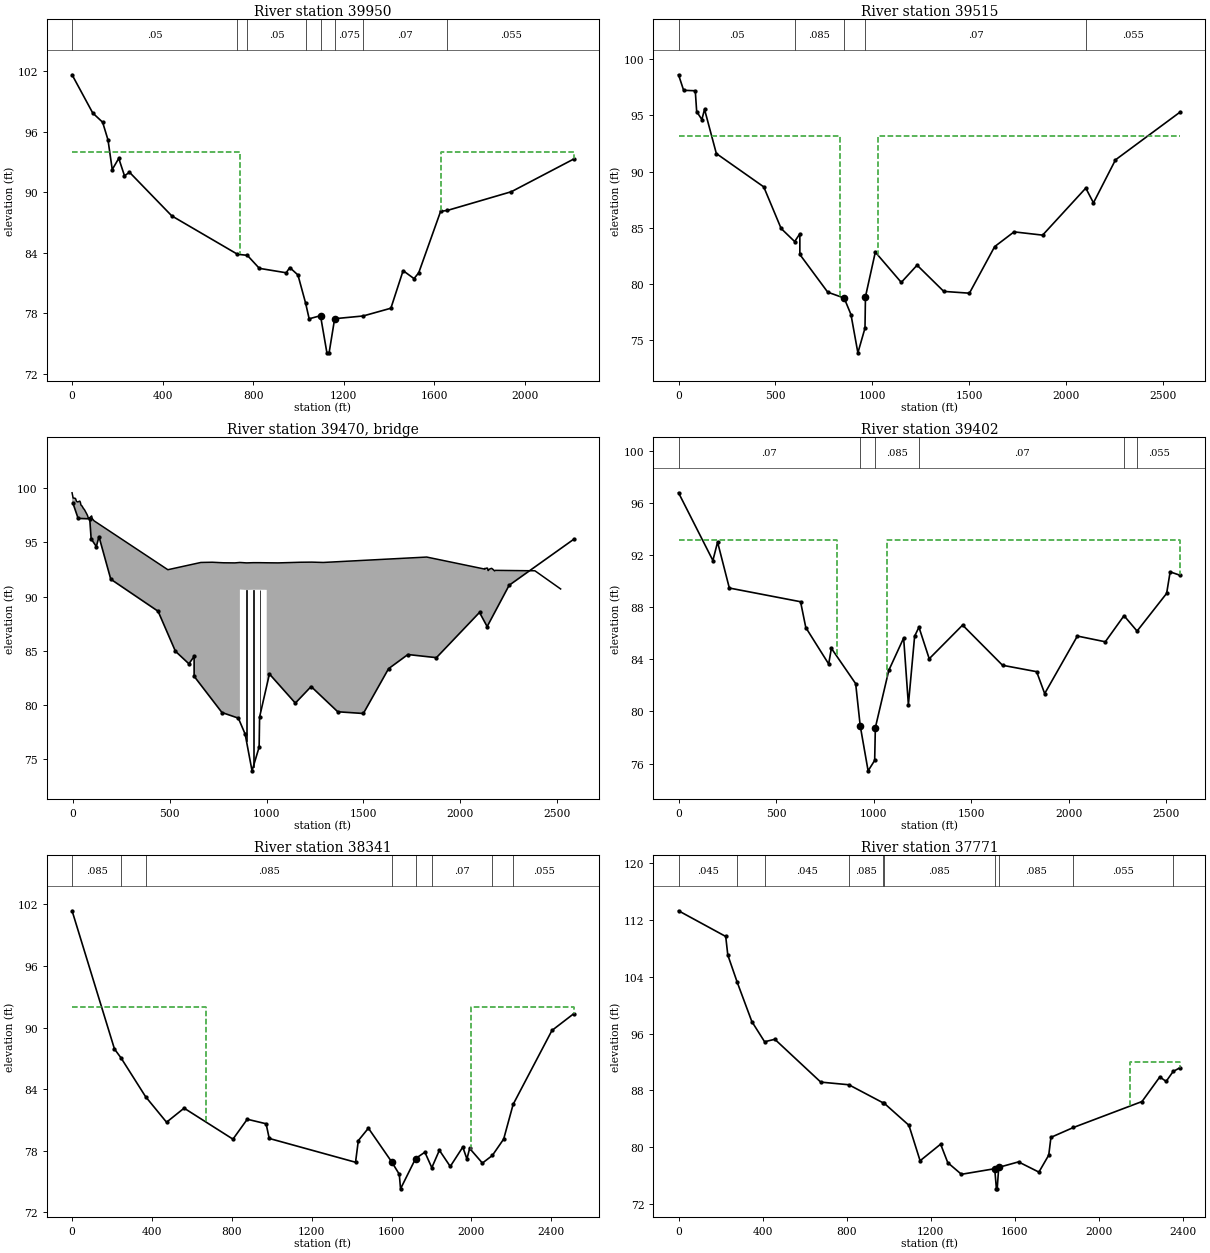
Type RM Length L Ch R = 1 ,39950   ,428.89,435.96,434.03
XS GIS Cut Line= 6
2312700.43370365688908.6938487592312487.55405937688347.465695724
2312377.88878813688018.4698818622312061.79477088687573.357898399
 2311861.8169232687334.6746609062311642.48638065686986.326152101
#Sta/Elev= 30
       0  101.67   91.42   97.87  134.92   96.96   158.7    95.2  177.45   92.26
   206.2   93.37  231.55   91.64  253.64   91.99  440.33   87.66  730.44   83.85
   774.1   83.74  827.05   82.45  945.68   82.01  961.46   82.53  997.59   81.79
 1031.62   78.98  1047.1   77.44 1097.22   77.75  1125.5   74.06 1135.18   74.06
 1159.71   77.45 1285.37   77.72 1408.05   78.49 1462.06   82.22 1510.28   81.43
 1531.04   82.01 1627.68   88.11 1657.46    88.2 1940.22   90.06 2216.15   93.31
#Mann= 8 ,-1 , 0
       0     .05       0  730.44    .085       0   774.1     .05       0
 1031.62    .075       0 1097.22     .05       0 1159.71    .075       0
 1285.37     .07       0 1657.46    .055       0
#XS Ineff= 2 , 0
       0     740      94    1630       0      94
Permanent Ineff=
       F       F
Bank Sta=1097.22,1159.71
XS Rating Curve= 0 ,0
Exp/Cntr=0.5,0.3

Type RM Length L Ch R = 1 ,39515   ,96.39,112.78,98.77
BEGIN DESCRIPTION:
Surveyed Section
END DESCRIPTION:
XS GIS Cut Line= 6
2313209.11630848688563.717186898    2312744.4647687849.701100007
2312714.44970003687831.4511000222312318.72827138687328.106377795
2312204.74738538687125.9259967362311902.42160663686362.806031272
#Sta/Elev= 30
       0    98.6   26.31   97.22    86.3   97.18   93.58   95.33  120.37   94.62
  134.06   95.53  194.97    91.6  439.39   88.64  529.11   84.94  598.82   83.78
  625.62   84.47 625.672   82.63 769.462   79.28 854.153   78.76 889.283   77.29
 924.935   73.89 961.588   76.09 963.964   78.871014.805   82.841148.692   80.15
 1230.24   81.68 1367.83   79.35 1500.06   79.19 1630.32   83.33 1730.36   84.64
 1877.62   84.35 2100.26   88.53 2139.77   87.22 2253.38   91.04  2587.8    95.3
#Mann= 5 ,-1 , 0
       0     .05       0  598.82    .085       0 854.153    .045       0
 963.964     .07       0 2100.26    .055       0
#XS Ineff= 2 , 0
       0     832   93.15    1030       0   93.12
Permanent Ineff=
       F       F
Bank Sta=854.153,963.964
XS Rating Curve= 0 ,0
Exp/Cntr=0.5,0.3

Type RM Length L Ch R = 3 ,39470   ,,,
BEGIN DESCRIPTION:
RT. 117
END DESCRIPTION:
Bridge Culvert--1,0,-1,-1, 0
Deck Dist Width WeirC Skew NumUp NumDn MinLoCord MaxHiCord MaxSubmerge Is_Ogee
26.55,35,2.6,0, 60, 58, , , 0.98, 0, 1,1,,
      -5   -2.59   -2.59     .57   10.85   10.85   13.39   17.62   24.11   24.11
    34.9   37.69   40.88   46.75   53.62   53.62   58.65   72.19   72.19   76.41
   76.91    81.6   83.28   96.09   99.45  108.56  489.88  660.32  719.33  777.71
 836.353 862.142 862.142 896.488 931.561 966.3071000.7621000.762 1059.411118.508
1176.5251234.2441292.805 1827.45 2123.77  2127.4 2128.77  2132.4 2138.16 2141.92
  2144.9  2149.5 2154.57 2163.07  2169.4 2170.11 2178.07 2181.88 2386.56 2519.49
   99.59   99.37   99.37   99.11   99.08   99.08   99.04    98.8   98.74   98.74
   98.82   98.72   98.46   98.36   98.14   98.14   98.04   97.59   97.59   97.42
   97.34    97.2   97.24   97.45    97.2      97   92.48   93.15   93.17   93.12
   93.11   93.15   93.15   93.11   93.13   93.13   93.12   93.12   93.11   93.14
   93.17   93.18   93.15   93.65   92.55    92.6   92.55    92.6   92.63   92.62
    92.4   92.49   92.56   92.61   92.51   92.51   92.37   92.42   92.38    90.7
                                                                                
                                                                                
                                                                                
                   90.65   90.61   90.63   90.63   90.62
                                                                                
                                                                                
       3    5.41    5.41    8.57   18.85   18.85   21.39   25.62   32.11   32.11
    42.9   45.69   48.88   54.75   61.62   61.62   66.65   80.19   80.19   84.41
   84.91    89.6   91.28  104.09  107.45  116.56  497.88  668.32  727.33  785.71
 844.353 870.142 870.142 904.488 939.561 974.3071008.7621008.762 1067.411126.508
1184.5251242.2441300.805 1835.45 2131.77  2135.4 2138.16 2141.92  2144.9  2149.5
 2154.57 2163.07  2169.4 2170.11 2178.07 2181.88 2386.56 2519.49
   99.59   99.37   99.37   99.11   99.08   99.08   99.04    98.8   98.74   98.74
   98.82   98.72   98.46   98.36   98.14   98.14   98.04   97.59   97.59   97.42
   97.34    97.2   97.24   97.45    97.2      97   92.48   93.15   93.17   93.12
   93.11   93.15   93.15   93.11   93.13   93.13   93.12   93.12   93.11   93.14
   93.17   93.18   93.15   93.65   92.55    92.6   92.63   92.62    92.4   92.49
   92.56   92.61   92.51   92.51   92.37   92.42   92.38    90.7
                                                                                
                                                                                
                                                                                
                   90.65   90.61   90.63   90.63   90.62
                                                                                
                                                                
Pier Skew, UpSta & Num, DnSta & Num=  ,896.488, 2 ,901.488, 2 , 0 , 0 , 0 ,,
     2.5     2.5
      70   90.67
     2.5     2.5
      70   90.67
Pier Skew, UpSta & Num, DnSta & Num=  ,931.561, 2 ,936.561, 2 , 0 , 0 , 0 ,,
     2.5     2.5
      70   90.67
     2.5     2.5
      70   90.67
Pier Skew, UpSta & Num, DnSta & Num=  ,966.307, 2 ,971.307, 2 , 0 , 0 , 0 ,,
     2.5     2.5
      70   90.67
     2.5     2.5
      70   90.67
Abutment Skew #Up #Dn= , 3 , 2
  862.14  879.14  880.54
   90.65  78.645   77.66
  870.14  892.14
   90.65   78.85
Abutment Skew #Up #Dn= , 2 , 2
  979.76 1000.76
   78.34   90.62
  988.76 1008.76
  78.349   90.62
BR Coef=-1 , 0 , 0 ,, 0 ,,,0.8,0,,0,
WSPro=,,,, 1 ,,,, 0 ,,,, 0 ,,,,-1 ,-1 ,-1 , 0 , 0 , 0 , 0 , 0
BC Design=,, 0 ,, 0 ,,,,,,
BC Use User HTab Curves=0
BC User HTab FreeFlow(D)= 0

Type RM Length L Ch R = 1 ,39402   ,672.8,1061.23,954.42
BEGIN DESCRIPTION:
Surveyed Section
END DESCRIPTION:
XS GIS Cut Line= 6
 2313279.4243103688523.5487651972313218.36312139688381.072657749
2312995.82901065688032.3454232812312751.79970004687677.285999998
 2312632.7845206687542.2757394312312016.18509507686301.048708931
#Sta/Elev= 30
       0   96.76  176.04   91.57   200.1   92.98  260.31   89.46   625.4   88.41
  652.22   86.43  769.48   83.64  783.29   84.84 907.816   82.13 930.933   78.92
 971.572   75.451005.195   76.251008.658   78.76 1077.55   83.15 1153.67   85.63
    1178   80.52 1209.96   85.77 1232.07   86.46 1284.81   84.04 1455.83   86.62
 1660.52   83.54 1835.29   83.05 1876.45   81.37 2043.98   85.78  2187.2   85.34
  2283.1   87.34 2349.96   86.16 2501.49   89.05 2519.49    90.7 2571.64   90.43
#Mann= 6 ,-1 , 0
       0     .07       0 930.933    .052       01008.658    .085       0
 1232.07     .07       0  2283.1    .085       0 2349.96    .055       0
#XS Ineff= 2 , 0
       0     810   93.15    1068       0   93.12
Permanent Ineff=
       F       F
Bank Sta=930.933,1008.658
XS Rating Curve= 0 ,0
Exp/Cntr=0.5,0.3

Type RM Length L Ch R = 1 ,38341   ,1175.48,569.97,448.28
XS GIS Cut Line= 6
2313872.30271727687874.7273513972313631.76235862687735.954067543
2312758.49178843686812.1518976992312571.41573738686702.486626431
2312371.43788975686521.8614737092311990.18201199686236.041001216
#Sta/Elev= 30
       0  101.38  212.44   87.91  245.04   87.05  368.19   83.27  473.17   80.78
  561.14   82.15  805.82   79.13   877.4   81.07  971.76   80.63  987.49    79.2
 1419.75   76.88 1433.74   78.99 1484.15    80.2 1600.05   76.94 1638.86   75.71
 1645.14   74.29 1720.48   77.24 1767.02   77.86 1801.72   76.35 1839.68   78.05
 1894.13   76.47 1956.99   78.36 1977.51    77.2  1991.3   78.23 2055.16    76.8
 2104.8177.53814 2161.71   79.14 2209.11   82.52 2403.46   89.72 2513.21   91.36
#Mann= 8 ,-1 , 0
       0    .085       0  245.04      .1       0  368.19    .085       0
 1600.05    .045       0 1720.48    .085       0 1801.72     .07       0
 2104.81    .085       0 2209.11    .055       0
#XS Ineff= 2 , 0
       0     670      92    2000       0      92
Permanent Ineff=
       F       F
Bank Sta=1600.05,1720.48
XS Rating Curve= 0 ,0
Exp/Cntr=0.3,0.1

Type RM Length L Ch R = 1 ,37771   ,595.298,1142.589,1173.521
XS GIS Cut Line= 6
2314344.13188234686440.7367516912313641.01391089686348.221229136
2312997.17502593686360.589015931 2312752.0408901686302.530931145
2312506.90675429686218.6692531112311999.93316814686089.773658887
#Sta/Elev= 30
       0  113.31  224.43  109.69   234.4  107.07  279.31  103.22  348.73   97.69
  409.41   94.84  458.07   95.19  676.61   89.15  810.2388.77629  974.95    86.2
  978.05   86.18 1096.11   83.06 1149.22   78.06 1246.86    80.4 1280.91   77.79
 1345.78   76.15  1504.2   76.94 1512.27    74.1 1515.97    74.1  1523.3   77.13
 1617.44    77.9 1714.43   76.46 1761.28   78.86 1771.61   81.36 1878.52   82.75
 2204.88   86.41 2289.65   89.88 2319.73   89.25  2353.1   90.65 2387.24    91.2
#Mann= 10 ,-1 , 0
       0    .045       0  279.31      .1       0  409.41    .045       0
  810.23    .085       0  974.95    .045       0  978.05    .085       0
  1504.2     .05       0  1523.3    .085       0 1878.52    .055       0
  2353.1    .085       0
#XS Ineff= 2 , 0
       0 1246.86      80    2150       0      92
Permanent Ineff=
       F       F
Bank Sta=1504.2,1523.3
XS Rating Curve= 0 ,0
Exp/Cntr=0.3,0.1