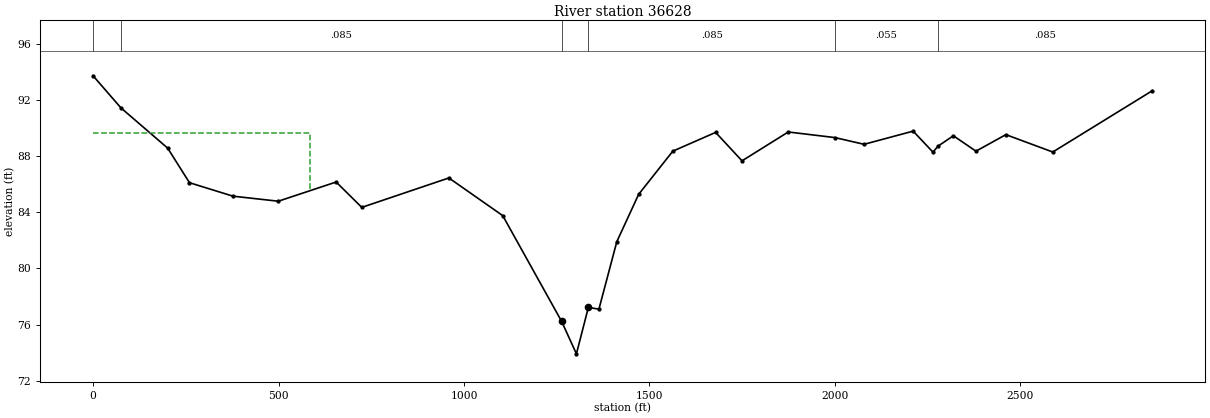
HEC-RAS study DTL_Black_Ck_US.prj: dtl_black_crk_upstream

--- DTL_Black_Ck_US.g01 (geometry) --- (continued)

Type RM Length L Ch R = 1 ,36628   ,380.62,12.97,18.62
BEGIN DESCRIPTION:
Tie to LDS Black Creek DS (Sta. 36628)
END DESCRIPTION:
XS GIS Cut Line= 6
2313835.25002436685951.3750060652313301.75002725685943.249995366
2312995.99996969685609.1250016692312775.99996851685380.999989793
2312613.89775659685206.163735211 2311647.7913741684314.806457341
#Sta/Elev= 30
       0   93.75   75.12   91.46  201.06   88.59  259.93   86.12  377.16   85.16
  499.44    84.8  655.39   86.17  724.49   84.36  959.36   86.46 1104.56   83.77
 1263.23   76.23  1303.2   73.91 1335.39   77.22  1363.9    77.1 1412.07   81.91
 1470.99   85.29 1563.03   88.37 1678.56   89.71  1749.7   87.68 1874.42   89.74
 2000.27   89.34 2078.75   88.86 2211.11    89.8 2264.53    88.3 2278.19   88.73
 2319.58   89.47 2380.46   88.37 2461.06   89.55 2587.57   88.31  2856.3   92.69
#Mann= 6 ,-1 , 0
       0    .045       0   75.12    .085       0 1263.23     .05       0
 1335.39    .085       0 2000.27    .055       0 2278.19    .085       0
#XS Ineff= 2 , 0
       0     586    89.7 1678.56       0   89.71
Permanent Ineff=
       F       F
Bank Sta=1263.23,1335.39
XS Rating Curve= 0 ,0
Exp/Cntr=0.3,0.1
Stream Node=Black Creek     ,Upstream        , 0 , 0 ,Upstream end
Stream Node=Black Creek     ,Upstream        , 0 , 1 ,Downstream end

Chan Stop Cuts=-1
Use User Specified Reach Order=0