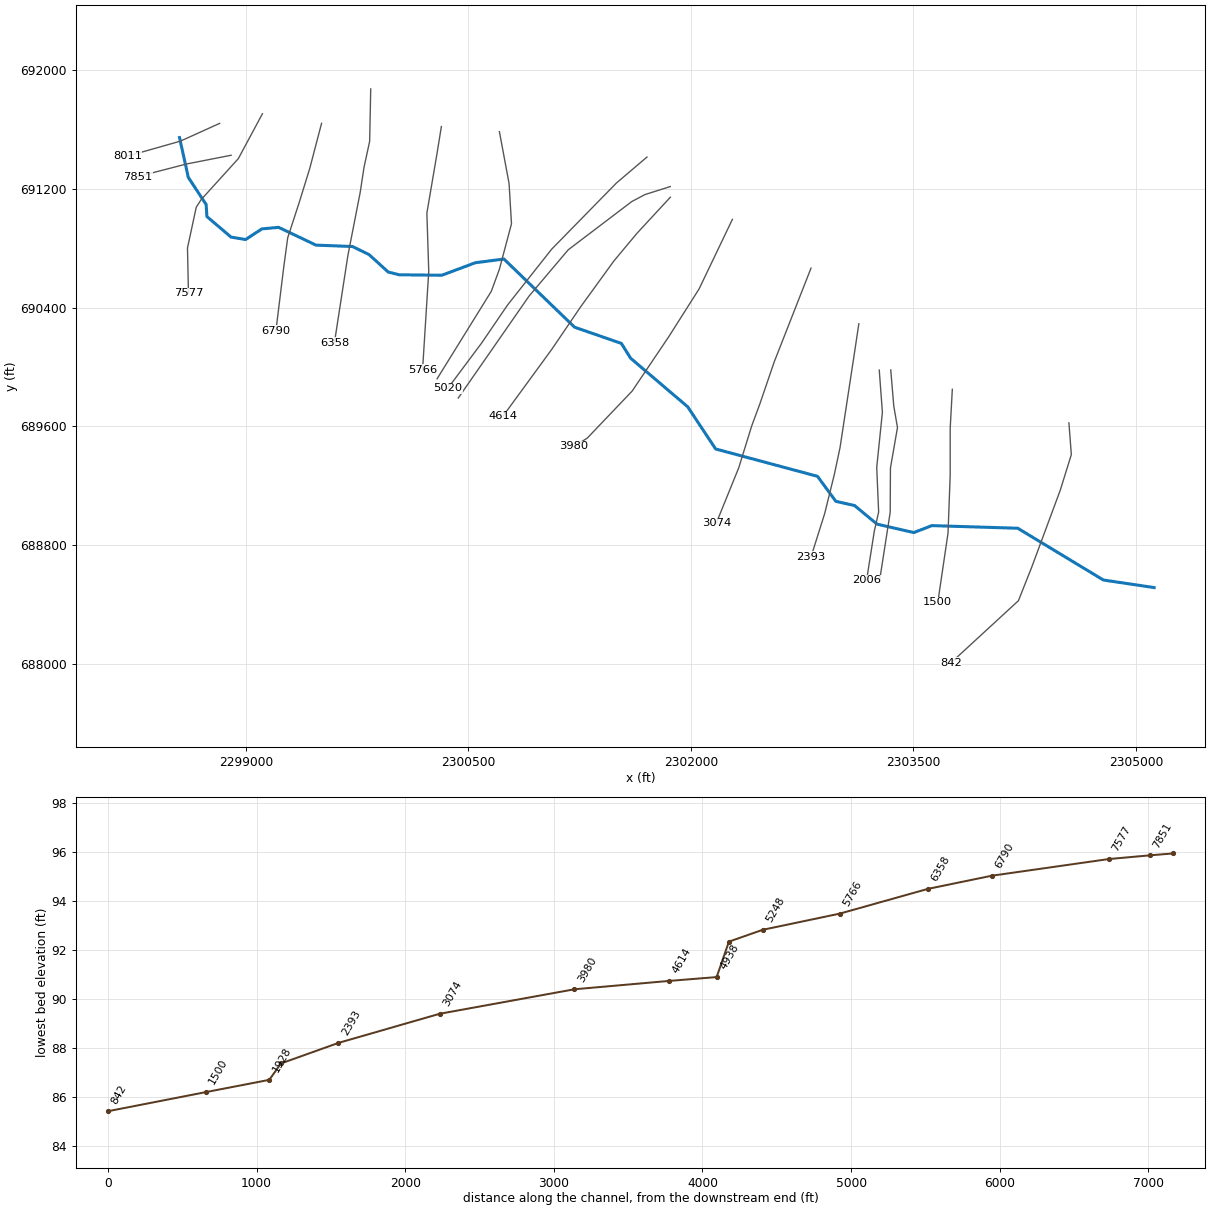
--- DTL_Black_Creek_Tributary.prj (project) ---

Proj Title=DTL_Black_Creek_Tributary
Current Plan=p02
Default Exp/Contr=0.3,0.1
English Units
Geom File=g01
Flow File=f02
Flow File=f01
Plan File=p02
Plan File=p01
Y Axis Title=Elevation
X Axis Title(PF)=Main Channel Distance
X Axis Title(XS)=Station
BEGIN DESCRIPTION:
END DESCRIPTION:
DSS Export Rating Curves= 0
DSS Export Rating Curve Sorted= 0
DSS Export Volume Flow Curves= 0
DXF OffsetX= 0
DXF OffsetY= 0
DXF ScaleX= 1
DXF ScaleY= 10

--- DTL_Black_Creek_Tributary.p02 (plan) ---

Plan Title=DTL_Black_Creek_Tributary
Program Version=4.00
Short Identifier=Multi Profil
Geom File=g01
Flow File=f02
Subcritical Flow
K Sum by GR= 0
Std Step Tol= 0.01
Critical Tol= 0.01
Num of Std Step Trials= 20
Max Error Tol= 0.3
Flow Tol Ratio= 0.001
Split Flow NTrial= 30
Split Flow Tol= 0.02
Split Flow Ratio= 0.02
Log Output Level= 0
Friction Slope Method= 1
Unsteady Friction Slope Method= 2
Unsteady Bridges Friction Slope Method= 1
Parabolic Critical Depth
Global Vel Dist= 0 , 0 , 0
Global Log Level= 0
CheckData=True
Encroach Param=-1 ,10,10, 2
Encroach River=Black Crk
Encroach Reach=Tributary
Encroach Node=8011
       1  169.55     345
Encroach Node=7851
       1     235     425
Encroach Node=7577
       1     644     925
Encroach Node=6790
       1     650  1008.5
Encroach Node=6358
       1    1015    1335
Encroach Node=5766
       1     925    1195
Encroach Node=5248
       1     725    1005
Encroach Node=5020
       1     993 1191.88
Encroach Node=4938
       1    1015 1197.96
Encroach Node=4614
       1     880    1100
Encroach Node=3980
       1    1060    1300
Encroach Node=3074
       1    1095    1438
Encroach Node=2393
       1     925    1268
Encroach Node=2006
       1     810    1080
Encroach Node=1928
       1     848  1083.5
Encroach Node=1500
       1     845    1072
Encroach Node=842
       4       1
Computation Interval=1HOUR
Output Interval=1HOUR
Run HTab= 0
Run UNet= 0
Run PostProcess= 0
Run WQNet= 0
UNET Theta= 1
UNET Theta Warmup= 1
UNET ZTol= 0.02
UNET ZSATol= 0.05
UNET MxIter= 20
UNET MaxInSteps= 0
UNET DtIC= 0
UNET DtMin= 0
UNET MaxCRTS= 20
UNET WFStab= 2
UNET SFStab= 1
UNET WFX= 1
UNET SFX= 1
UNET DSS MLevel= 4
UNET DZMax Abort= 100
UNET Convert EG Bridges= 0
UNET Use Existing IB Tables=-1
UNET Froude Reduction=False
UNET Froude Limit= 1
UNET Froude Power= 10
UNET Time Slicing=0,0, 5
Instantaneous Interval=1HOUR
Write IC File= 0
Echo Input=False
Echo Output=False
Write Detailed= 0
Detailed Automatic Start=False, 10
WQ ULTIMATE=-1
WQ Max Comp Step=1HOUR
WQ Output Interval=15MIN
WQ Output Selected Increments= 0
WQ Output face flow=0
WQ Output face velocity=0
WQ Output face area=0
WQ Output face dispersion=0
WQ Output cell volume=0
WQ Output cell surface area=0
WQ Output cell continuity=0
WQ Output face conc=0
WQ Output face dconc_dx=0
WQ Output face courant=0
WQ Output face peclet=0
WQ Output face adv mass=0
WQ Output face disp mass=0
WQ Output cell mass=0
WQ Output cell source sink temp=0
WQ Output cell source sink nsm=0
WQ Output MaxMinRange=-1
WQ Daily Max Min Mean=-1
WQ Daily Range=0
WQ Daily Time=0
WQ Create Restart=0
WQ Fixed Restart=0
WQ System Summary=False
Sorting and Armoring Iterations= 10
XS Update Threshold= 0.02
Hydraulics Update Threshold= 0.02
Energy Slope Method= 1
Volume Change Method= 0
XS Weighting Method= 0
Number of US Weighted Cross Sections= 1
Number of DS Weighted Cross Sections= 1
Upstream XS Weight=0.25
Main XS Weight=0.5
Downstream XS Weight=0.25
Number of DS XS's Weighted with US Boundary= 1
Upstream Boundary Weight= 1
Weight of XSs Associated with US Boundary= 0
Number of US XS's Weighted with DS Boundary= 1
Downstream Boundary Weight= 0.5
Weight of XSs Associated with DS Boundary= 0.5
Sediment Output Level= 4
Mass or Volume Output= 0
Output Increment Type= 1
Profile and TS Output Increment= 10
XS Output Flag= 0
XS Output Increment= 10
Disregard all LS=0
Disregard all Conn=0
Disregard all Breaches=0
Disregard all Pumps=0

--- DTL_Black_Creek_Tributary.p01 (plan) ---

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Plan Title=DTL_Black_Creek_Tributary_Future
Program Version=3.13
Short Identifier=Future
Geom File=g01
Flow File=f01
Encroach Param=-1 ,0,0, 0

--- DTL_Black_Creek_Tributary.f02 (steady flow) ---

Flow Title=DTL_Black_Creek_Tributary
Program Version=4.00
Number of Profiles= 6
Profile Names=100-yr,FW,10-yr,25-yr,50-yr,500-yr
River Rch & RM=Black Crk,Tributary       ,8011
    1462    1462     682     955    1194    2228
River Rch & RM=Black Crk,Tributary       ,7577
    1950    1950     930    1290    1600    2950
Boundary for River Rch & Prof#=Black Crk,Tributary       , 1
Up Type= 0
Dn Type= 3
Dn Slope=6.382979E-04
Boundary for River Rch & Prof#=Black Crk,Tributary       , 2
Up Type= 0
Dn Type= 3
Dn Slope=6.382979E-04
Boundary for River Rch & Prof#=Black Crk,Tributary       , 3
Up Type= 0
Dn Type= 3
Dn Slope=6.382979E-04
Boundary for River Rch & Prof#=Black Crk,Tributary       , 4
Up Type= 0
Dn Type= 3
Dn Slope=6.382979E-04
Boundary for River Rch & Prof#=Black Crk,Tributary       , 5
Up Type= 0
Dn Type= 3
Dn Slope=6.382979E-04
Boundary for River Rch & Prof#=Black Crk,Tributary       , 6
Up Type= 0
Dn Type= 3
Dn Slope=6.382979E-04
DSS Import GetInterval= 0
DSS Import GetPeak= 0
DSS Import FillOption= 0

--- DTL_Black_Creek_Tributary.f01 (steady flow) ---

Flow Title=DTL_Black_Creek_Tributary_Future
Program Version=4.00
Number of Profiles= 3
Profile Names=100-yr-10%,100-yr-20%,100-yr-35%
River Rch & RM=Black Crk,Tributary       ,8011
    1627    2073    2532
River Rch & RM=Black Crk,Tributary       ,7851
    1620    2070    2530
River Rch & RM=Black Crk,Tributary       ,7577
    2130    2730    3340
Boundary for River Rch & Prof#=Black Crk,Tributary       , 1
Up Type= 0
Dn Type= 3
Dn Slope=6.382979E-04
Boundary for River Rch & Prof#=Black Crk,Tributary       , 2
Up Type= 0
Dn Type= 3
Dn Slope=6.382979E-04
Boundary for River Rch & Prof#=Black Crk,Tributary       , 3
Up Type= 0
Dn Type= 3
Dn Slope=6.382979E-04
DSS Import GetInterval= 0
DSS Import GetPeak= 0
DSS Import FillOption= 0

--- DTL_Black_Creek_Tributary.g01 (geometry) ---

Geom Title=DTL_Black_Creek_Tributary
Program Version=4.00

River Reach=Black Crk       ,Tributary
Reach XY= 30
 2298553.3323467  691546.4618316 2298612.4689871  691278.1834143
 2298732.6203802  691095.6498739 2298737.8287136  691014.3998739
 2298900.3287136  690875.8582073 2298998.2453802  690859.1915406
 2299108.6620469  690931.0665406 2299221.1620469  690941.4832073
 2299473.2453802  690821.6915406 2299719.0787136  690812.3165406
 2299830.5370469  690758.1498739 2299959.7037136  690640.4415406
 2300033.6620469  690621.6915406 2300321.1620469  690618.5665406
 2300547.2037136  690702.9415406 2300739.9120469  690727.9415406
 2301215.9537135  690268.5665406 2301531.5787136  690159.1915406
 2301594.0787135  690059.1915406 2301978.4537135  689732.1082072
 2302166.9953802  689447.7332072 2302853.4537136  689263.3582072
 2302977.4120469  689094.6082073 2303103.4537135  689066.4832073
 2303254.6883132  688941.0986348 2303502.4120469  688884.1915406
 2303624.2870469  688931.0665406 2304203.4537135  688913.3582073
 2304780.5370469  688564.3998739 2305122.2975778  688513.4009533

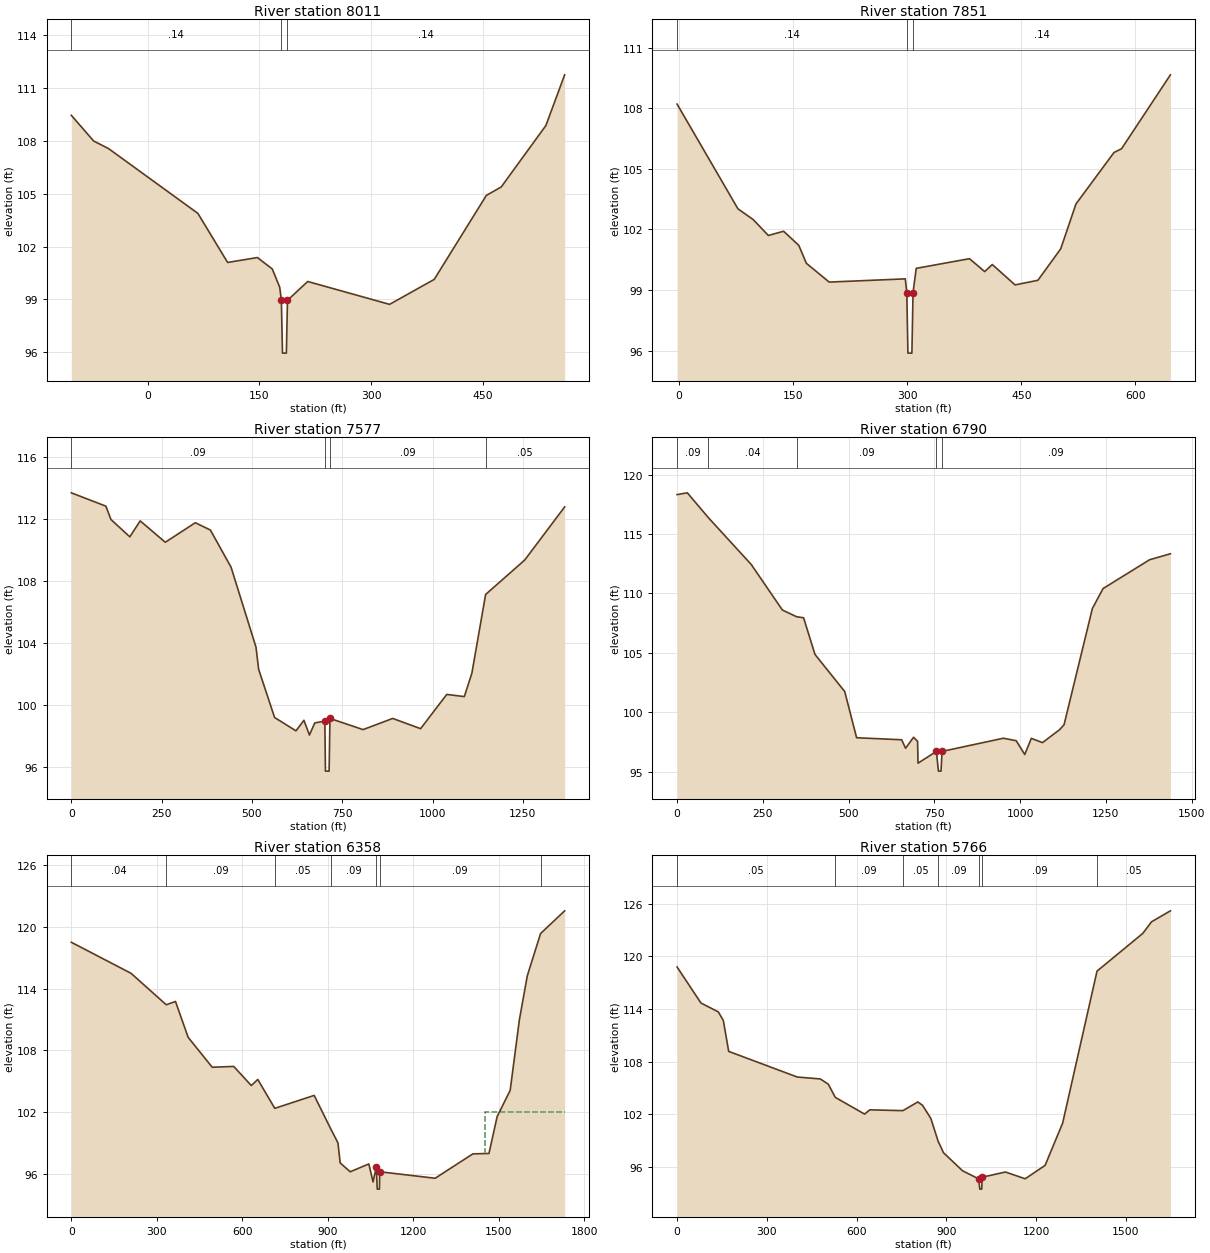
Type RM Length L Ch R = 1 ,8011    ,183.87,160.17,158.35
BEGIN DESCRIPTION:
Section taken from LDS (Section 8333.3)
END DESCRIPTION:
XS GIS Cut Line= 4
 2298823.7587364  691642.3455354 2298730.2500182  691600.0000228
 2298559.2500274  691522.5625133 2298200.9818652  691420.8297651
#Sta/Elev= 19
 -102.65  109.46  -72.65     108  -52.65  107.57   67.35  103.89  107.35   101.1
  147.35  101.38  167.35  100.73  177.35   99.69  179.55   98.95  181.05   95.95
  186.25   95.95  187.75   98.95  214.95  100.02  324.95   98.72  384.95  100.14
  454.95  104.91  474.95  105.39  534.95  108.88  560.15  111.76
#Mann= 3 ,-1 , 0
 -102.65     .14       0  179.55    .047       0  187.75     .14       0
Bank Sta=179.55,187.75
XS Rating Curve= 0 ,0
Exp/Cntr=0.3,0.1

Type RM Length L Ch R = 1 ,7851    ,174.31,274.2,499.99
XS GIS Cut Line= 4
 2298900.8799135  691427.3905663 2298898.2499662  691426.8750304
 2298599.5000085  691368.3125127 2298268.9105612  691282.7488783
#Sta/Elev= 24
   -2.68  108.21   77.32  103.02   97.32  102.49  117.32   101.7  137.32  101.91
  157.32  101.21  167.32  100.32  197.32   99.39  297.32   99.55  299.32   98.87
  300.82   95.87  306.02   95.87  307.52   98.87  311.72  100.07  381.72  100.55
  401.72   99.91  411.72  100.26  441.72   99.25  471.72   99.48  501.72  101.04
  521.72  103.26  571.72  105.81  581.72     106  645.92  109.66
#Mann= 3 ,-1 , 0
   -2.68     .14       0  299.32    .047       0  307.52     .14       0
Bank Sta=299.32,307.52
XS Rating Curve= 0 ,0
Exp/Cntr=0.3,0.1

Type RM Length L Ch R = 1 ,7577    ,582.04,786.8,727.54
XS GIS Cut Line= 6
  2299112.073774  691707.0640428 2298949.5967915  691404.7334552
     2298698.414     691127.6199    2298665.8451     691076.7109
  2298606.874314  690801.9036782  2298613.583346  690497.7608976
#Sta/Elev= 30
       0  113.68   95.66  112.82  109.64  111.96  161.92  110.84  190.62  111.87
  260.13  110.49  343.23  111.75  384.97  111.28  442.24  108.88  511.25  103.72
  518.55  102.29  562.76   99.18  621.89   98.32  643.94      99  659.21   98.05
   673.9   98.83  701.84   98.95  703.46   95.72  713.65   95.72  715.98   99.12
  716.04   99.12  807.61    98.4  889.71   99.12  966.94   98.46 1039.31  100.67
 1087.95  100.53 1108.87  102.04 1146.93  107.12 1255.05  109.34 1365.71  112.77
#Mann= 4 ,-1 , 0
       0     .09       0  701.84     .05       0  716.04     .09       0
 1146.93     .05       0
Bank Sta=701.84,715.98
XS Rating Curve= 0 ,0
Exp/Cntr=0.3,0.1

Type RM Length L Ch R = 1 ,6790    ,403.75,431.54,449.44
XS GIS Cut Line= 6
 2299510.7045558  691642.6389848 2299431.0302344  691338.4279395
 2299360.4098132  691110.2696556 2299282.5462718  690871.2466915
 2299255.3845714   690670.250108 2299202.8719505  690242.9060207
#Sta/Elev= 30
       0  118.32   29.87  118.47   91.46  116.37   216.1  112.44  307.07   108.6
   348.3  108.04  368.78  107.95  401.88  104.87  488.66  101.74  523.32   97.85
  654.55   97.68  666.08   96.97  689.37   97.89  701.05   97.55  702.31   95.71
  755.86    96.7  761.85   95.04  769.34   95.04  772.39    96.7  951.18   97.81
  988.53    97.6 1013.42   96.44  1032.6    97.8 1065.26   97.44 1115.44   98.54
 1128.07   98.95 1210.61  108.73 1241.72  110.41 1377.66  112.84 1438.08  113.34
#Mann= 5 ,-1 , 0
       0     .09       0   91.46     .04       0   348.3     .09       0
  755.86     .05       0  772.39     .09       0
Bank Sta=755.86,772.39
XS Rating Curve= 0 ,0
Exp/Cntr=0.3,0.1

Type RM Length L Ch R = 1 ,6358    ,606.95,592.49,602.55
XS GIS Cut Line= 6
 2299842.0773015  691874.4188288 2299834.8341813  691521.3167227
 2299796.8078007  691345.6710596 2299771.4568803  691179.0792968
 2299688.1609988  690751.7352094 2299597.6219972  690165.0424793
#Sta/Elev= 30
       0  118.52  209.49   115.5  332.93  112.44  365.39  112.76  409.79  109.27
  494.26  106.36  569.68  106.44  631.23  104.58  654.06  105.17  713.63  102.36
  851.82  103.62   910.9  100.31  935.27      99  943.03   97.05  978.21   96.19
 1043.52   96.95 1058.39    95.2 1069.75   96.66 1073.04    94.5 1080.72    94.5
 1081.52   96.19 1276.22   95.56  1408.5   97.93 1464.95   97.97 1493.65  101.56
 1539.35  104.11 1571.78     111 1599.41  115.26 1645.98  119.37 1730.42  121.58
#Mann= 7 ,-1 , 0
       0     .04       0  332.93     .09       0  713.63     .05       0
   910.9     .09       0 1069.75     .05       0 1081.52     .09       0
 1645.98     .05       0
#XS Ineff= 2 , 0
       0                    1450       0     102
Permanent Ineff=
       F       F
Bank Sta=1069.75,1081.52
XS Rating Curve= 0 ,0
Exp/Cntr=0.3,0.1

Type RM Length L Ch R = 1 ,5766    ,628.37,518.07,536.52
XS GIS Cut Line= 5
 2300318.3124497  691620.9096244 2300287.5291891  691430.7777211
  2300220.530328  691037.8384543 2300233.2057882  690644.8991876
 2300191.5578475  689982.1536962
#Sta/Elev= 30
       0  118.79    79.7  114.69  137.73  113.68  154.56  112.69  172.44  109.18
  401.46  106.26  478.63  106.04  505.09  105.45  528.65  103.94  626.34  102.04
  644.06  102.52  754.48  102.43  804.41  103.42   820.1  103.04  848.06  101.53
  872.01   98.97  890.09   97.64  953.81   95.58 1007.68   94.66 1011.51   93.49
 1017.81   93.49 1019.71   94.85 1097.14   95.44 1163.16   94.67 1229.57   96.19
 1288.34  101.01 1403.13  118.32 1556.15  122.62 1585.26  123.94 1648.41  125.19
#Mann= 7 ,-1 , 0
       0     .05       0  528.65     .09       0  754.48     .05       0
  872.01     .09       0 1007.68     .05       0 1019.71     .09       0
 1403.13     .05       0
Bank Sta=1007.68,1019.71
XS Rating Curve= 0 ,0
Exp/Cntr=0.3,0.1

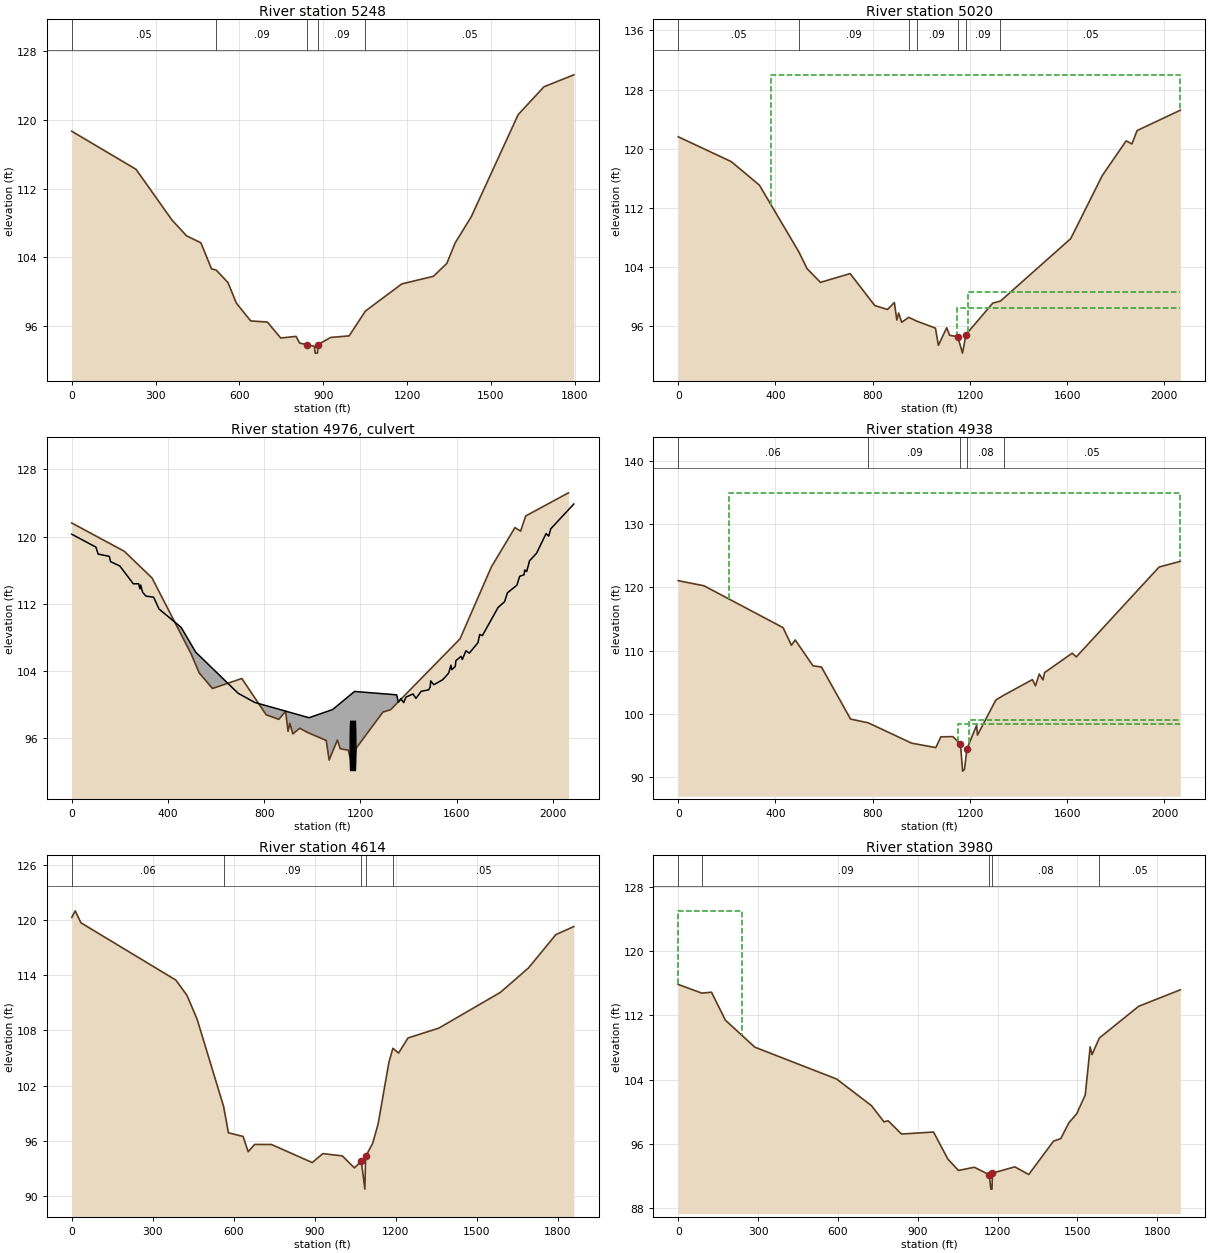
Type RM Length L Ch R = 1 ,5248    ,408.9,227.4,176.11
XS GIS Cut Line= 6
 2300709.4409364  691586.5048038 2300774.6290175  691237.0242578
 2300790.9260378  690965.4072531 2300709.4409364  690659.3854278
 2300655.1175355  690510.9014653 2300289.3399692  689920.5871751
#Sta/Elev= 30
       0  118.67  229.87  114.24  358.67  108.33  410.82  106.49  462.16  105.68
  500.08  102.65  516.96   102.5  559.03  101.05  589.14   98.65  640.43   96.58
  700.11   96.45  747.82   94.59  802.81   94.78  815.52      94  841.48   93.81
  868.42   93.62  871.19   92.83  879.08   92.83  881.18   93.83  926.79   94.66
  992.79   94.84  1050.8   97.73 1181.19  100.89  1294.5  101.78 1342.24  103.28
 1372.01  105.66    1430  108.73 1597.54   120.6 1689.96  123.85 1796.86  125.24
#Mann= 5 ,-1 , 0
       0     .05       0  516.96     .09       0  841.48     .05       0
  881.18     .09       0  1050.8     .05       0
Bank Sta=841.48,881.18
XS Rating Curve= 0 ,0
Exp/Cntr=0.5,0.3

Type RM Length L Ch R = 1 ,5020    ,90.37,82.67,74.65
BEGIN DESCRIPTION:
Surveyed Section
END DESCRIPTION:
XS GIS Cut Line= 6
 2301704.1090851  691415.2870609 2301498.1767217  691240.2507094
 2301061.8528494  690794.4870469 2300763.9239752  690417.4448679
 2300590.5074974  690162.8547197 2300361.7453353  689856.6085993
#Sta/Elev= 30
       0  121.62  218.57  118.25  333.96  115.07   496.3  106.04  530.08  103.77
  585.06  101.92  707.11  103.11  808.44   98.79  860.87   98.25  889.09    99.2
  899.29   96.82  906.82   97.77  919.18   96.52  947.99   97.19  980.21   96.69
 1058.14   95.73 1070.13    93.4 1104.24   95.781116.312 94.7556 1149.77 94.5733
1169.391 92.34641183.435 94.8513  1294.1   99.12 1325.53   99.39 1614.35  107.83
 1744.14  116.36 1842.66  121.07 1866.18  120.65  1887.6  122.46 2065.33  125.21
#Mann= 7 ,-1 , 0
       0     .05       0   496.3     .09       0  947.99     .05       0
  980.21     .09       0 1149.77     .05       01183.435     .09       0
 1325.53     .05       0
#XS Ineff= 3 ,-1
     381     381     130 1146.88 1146.88   98.44 1191.88 1191.88  100.64
Permanent Ineff=
       F       F       F
Bank Sta=1149.77,1183.435
XS Rating Curve= 0 ,0
Exp/Cntr=0.5,0.3

Type RM Length L Ch R = 2 ,4976    ,,,
BEGIN DESCRIPTION:
Blaylock Rd
END DESCRIPTION:
Bridge Culvert--1,0,-1,-1, 0
Deck Dist Width WeirC Skew NumUp NumDn MinLoCord MaxHiCord MaxSubmerge Is_Ogee
33,19,2.6,0, 60, 60, , , 0.95, 0, 1,1,,
       0   100.3  109.68     156  161.29  199.75  255.88  277.93  283.22  286.65
  294.36  308.25  340.29  362.91  454.68  515.24  691.79  760.86 986.6031084.721
 1175.74 1350.89  1358.1 1367.83 1380.37 1389.43  1418.6 1431.21 1453.22 1483.87
 1490.46 1492.34 1505.61  1542.5 1566.87 1576.65 1579.82 1594.56  1597.1 1618.78
 1623.84    1639 1652.88 1688.95 1696.07 1707.33 1772.52 1799.55 1811.47 1850.67
 1862.28 1880.72 1883.25 1891.59 1903.27 1932.35    1972 1983.18 1991.62 2087.61
  120.28  118.75  117.92  117.65  117.02   116.5  114.38  114.39  113.79  114.24
  113.38  112.92  112.79  111.38   109.2  106.25  101.35  100.26  98.442  99.416
 101.569 101.167   100.3   100.7  100.24  100.89  101.27  100.75  101.59  101.76
  102.11  102.82  102.37  102.97  103.74   104.7  104.16  104.54  105.23  105.75
  105.37  106.41  106.13  107.37  108.35  108.22  111.56  112.25  113.31  114.21
  115.27  115.46  116.03  115.84  117.12  118.01  120.35  120.06  120.93  123.88
                                                                                
                                                                                
                                                                                
                                                                                
                                                                                
                                                                                
       0   100.3  109.68     156  161.29  199.75  255.88  277.93  283.22  286.65
  294.36  308.25  340.29  362.91  454.68  515.24  691.79  760.86 986.6031084.721
 1175.74 1350.89  1358.1 1367.83 1380.37 1389.43  1418.6 1431.21 1453.22 1483.87
 1490.46 1492.34 1505.61  1542.5 1566.87 1576.65 1579.82 1594.56  1597.1 1618.78
 1623.84    1639 1652.88 1688.95 1696.07 1707.33 1772.52 1799.55 1811.47 1850.67
 1862.28 1880.72 1883.25 1891.59 1903.27 1932.35    1972 1983.18 1991.62 2087.61
  120.28  118.75  117.92  117.65  117.02   116.5  114.38  114.39  113.79  114.24
  113.38  112.92  112.79  111.38   109.2  106.25  101.35  100.26  98.442  99.416
 101.569 101.167   100.3   100.7  100.24  100.89  101.27  100.75  101.59  101.76
  102.11  102.82  102.37  102.97  103.74   104.7  104.16  104.54  105.23  105.75
  105.37  106.41  106.13  107.37  108.35  108.22  111.56  112.25  113.31  114.21
  115.27  115.46  116.03  115.84  117.12  118.01  120.35  120.06  120.93  123.88
                                                                                
                                                                                
                                                                                
                                                                                
                                                                                
                                                                                
BR Coef=-1 , 0 , 0 ,, 0 ,,,0.8,-1,,0,
WSPro=,,,, 1 ,,,, 0 ,,,, 0 ,,,,-1 ,-1 ,-1 , 0 , 0 , 0 , 0 , 0
Multiple Barrel Culv=1,6,,42,0.024,0.5,1,2,1,92.0855,92.0308, 3,Culvert #1  , 0 ,22
 1160.38 1164.35 1169.38 1173.35 1178.38 1182.35
Culvert Bottom n=0.024
BC Design=,, 0 ,, 0 ,,,,,,
BC Use User HTab Curves=0
BC User HTab FreeFlow(D)= 0

Type RM Length L Ch R = 1 ,4938    ,280.46,323.86,329.01
BEGIN DESCRIPTION:
Surveyed Section
END DESCRIPTION:
XS GIS Cut Line= 6
 2301861.4547107  691216.4594066 2301689.8049373   691162.103645
  2301601.119221  691114.8999573 2301173.4252021  690790.1958026
    2300909.6188     690478.5095 2300432.4185195  689791.2687851
#Sta/Elev= 30
       0  121.08  106.07  120.27  431.17  113.64  465.74  110.85  481.13  111.69
  554.26  107.59  589.19   107.4  708.82   99.15  781.72   98.55  960.13   95.33
  1059.6   94.63 1080.36 96.33781129.514 96.36751160.907 95.21451169.788  90.899
1177.223 91.16271187.962  94.451 1227.41 98.1695 1230.92   96.61 1306.42  102.17
 1340.59  102.96 1456.82   105.4 1469.41  104.42 1485.09  106.29  1500.4  105.36
 1506.86  106.51 1620.55  109.59 1637.45     109 1977.95  123.24  2065.3  124.15
#Mann= 5 ,-1 , 0
       0     .06       0  781.72     .09       01160.907     .05       0
1187.962     .08       0 1340.59     .05       0
#XS Ineff= 3 ,-1
  210.75  210.75     135 1150.85 1150.85   98.44 1197.96 1197.96   99.03
Permanent Ineff=
       F       F       F
Bank Sta=1160.907,1187.962
XS Rating Curve= 0 ,0
Exp/Cntr=0.5,0.3

Type RM Length L Ch R = 1 ,4614    ,632.7,634.25,620.84
XS GIS Cut Line= 6
 2301861.7046881   691144.432633 2301637.1679642  690901.7881088
 2301481.4408815  690715.2777656 2301256.9041577  690405.6343803
 2301061.3399143  690117.7203553 2300733.2408562  689668.1702646
#Sta/Elev= 30
       0  120.27   12.74  120.99   33.92  119.69  385.76  113.46  427.06  111.79
  464.37  109.21  562.48   99.73  580.43   96.86  634.73   96.47  653.45   94.81
   677.6    95.6   739.8   95.59  890.77   93.63  930.33    94.6 1002.35   94.35
  1047.2   93.05  1072.7   93.77  1085.8   90.74  1088.7   94.29 1114.78   95.72
 1135.06   97.84 1174.95  104.53  1189.7  106.05 1210.72  105.53 1245.61  107.17
 1359.83  108.24 1587.55  112.12  1692.3  114.79 1793.27   118.4 1860.06  119.28
#Mann= 5 ,-1 , 0
       0     .06       0  562.48     .09       0  1072.7     .05       0
  1088.7     .08       0  1189.7     .05       0
Bank Sta=1072.7,1088.7
XS Rating Curve= 0 ,0
Exp/Cntr=0.3,0.1

Type RM Length L Ch R = 1 ,3980    ,789.84,905.71,951.65
XS GIS Cut Line= 6
 2302279.8444842  690995.2231409 2302055.3077604  690526.2311128
 2301850.6896168  690203.9122673 2301604.4235326   689838.134701
 2301302.0232674  689521.2481955 2301212.7511473  689464.3590525
#Sta/Elev= 30
       0  115.85   88.29  114.77  125.06  114.88  177.33   111.4  287.79  108.05
  595.17  104.09  726.17  100.78  773.19   98.76  788.67    98.9  839.17   97.25
   959.3    97.5 1013.32   94.13 1052.98   92.72 1112.45   93.12 1168.77   92.19
 1174.65    90.4 1178.89    90.4 1180.85   92.39 1264.72   93.17 1317.02   92.22
 1410.24   96.37 1437.49   96.68    1468   98.66 1496.87   99.74 1529.46  102.11
 1547.99  108.09 1554.78  107.12 1582.51  109.19 1730.01  113.13 1886.64  115.18
#Mann= 5 ,-1 , 0
       0     .06       0   88.29     .09       0 1168.77     .05       0
 1180.85     .08       0 1582.51     .05       0
#XS Ineff= 2 , 0
       0  239.83     125               0
Permanent Ineff=
       F       F
Bank Sta=1168.77,1180.85
XS Rating Curve= 0 ,0
Exp/Cntr=0.3,0.1

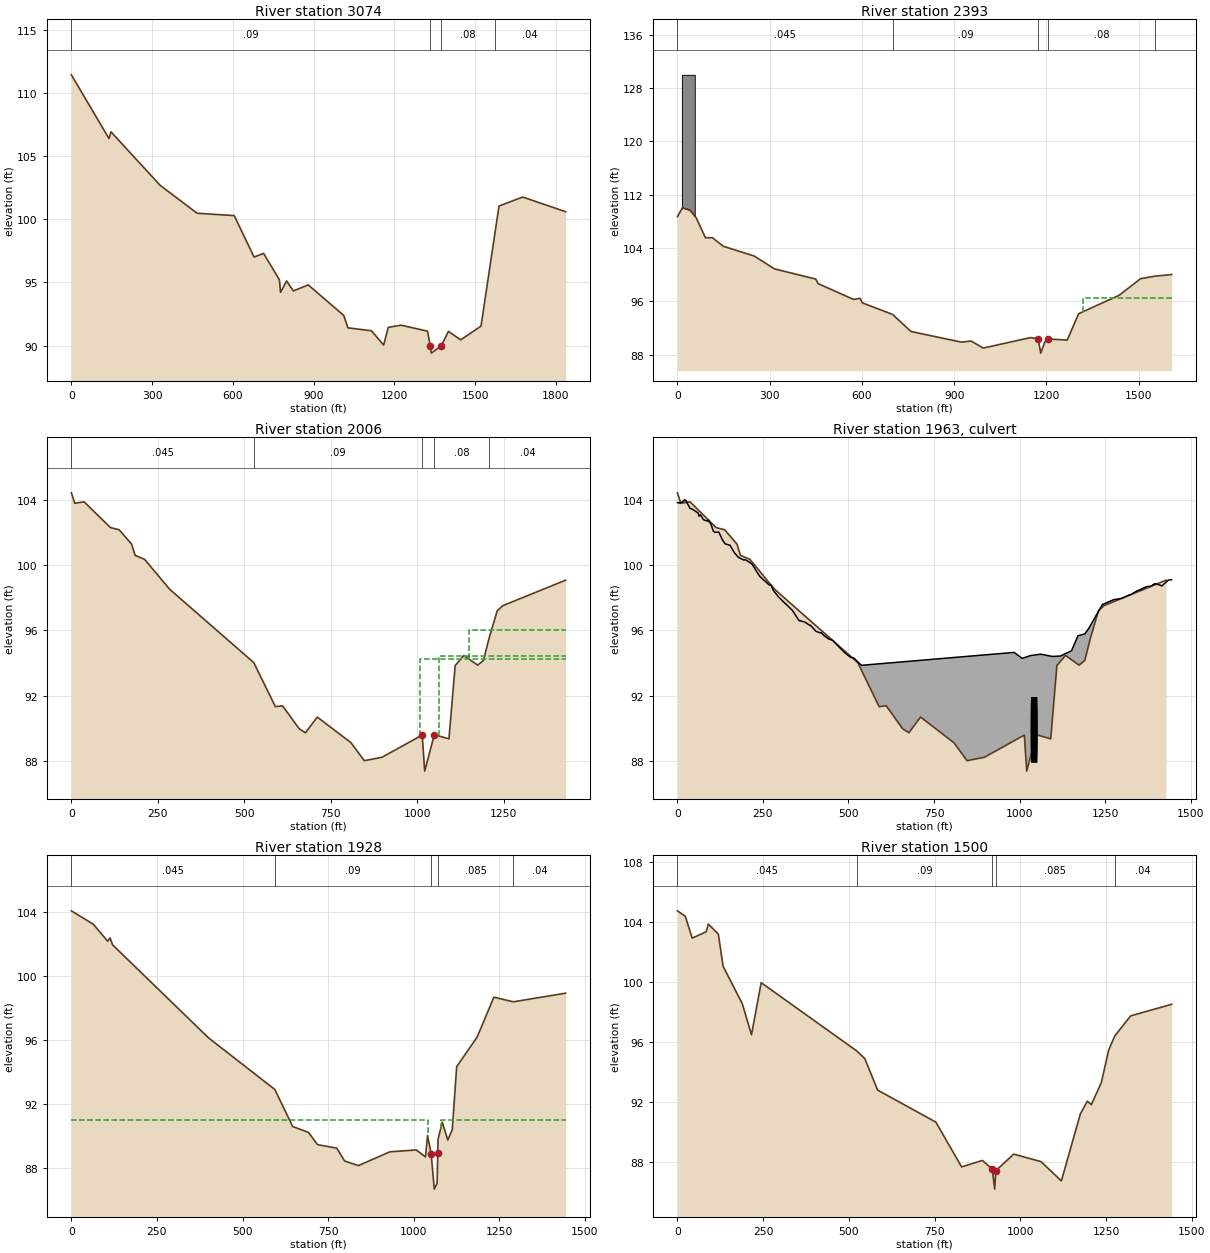
Type RM Length L Ch R = 1 ,3074    ,606.46,680.7,656.16
XS GIS Cut Line= 6
 2302809.9457726  690666.6285479 2302561.8689084   690034.666317
 2302465.8975667  689753.9954122 2302409.7633857  689601.8898896
 2302322.8459442  689321.2189848 2302170.7404216  688946.3875183
#Sta/Elev= 30
       0  111.42  139.71  106.38  147.16  106.91  329.65  102.68  466.94  100.47
  604.97  100.28  678.84      97  714.12   97.29  772.74   95.21  777.02   94.21
  799.75   95.11  824.75   94.32  879.94    94.8    1012   92.38 1027.37    91.4
 1114.74   91.17 1160.11   90.04 1177.37   91.44 1224.88   91.61 1323.15   91.14
 1332.88      90 1337.45    89.4 1374.81      90 1400.74   91.12 1446.43   90.45
 1521.87   91.54 1572.03   98.67 1588.74  101.04 1676.57  101.75 1836.06  100.59
#Mann= 4 ,-1 , 0
       0     .09       0 1332.88     .05       0 1374.81     .08       0
 1572.03     .04       0
Bank Sta=1332.88,1374.81
XS Rating Curve= 0 ,0
Exp/Cntr=0.3,0.1

Type RM Length L Ch R = 1 ,2393    ,274.85,386.67,363.29
XS GIS Cut Line= 6
 2303132.2646182  690291.7970815 2303101.4813576   690087.178938
  2303005.510016  689457.0274871 2302967.4836353   689277.760264
 2302902.2955542  689013.3863795 2302809.9457726  688720.0400144
#Sta/Elev= 30
       0   108.7   16.31  110.05   40.61  109.69   61.28  108.51   91.02  105.54
  113.88  105.54  148.93  104.26  249.69  102.79  315.55  100.86  449.86   99.33
  457.47   98.65  572.97   96.27  594.16   96.43  601.33   95.76  699.87   94.02
  759.55   91.46  923.81   89.86  955.06   90.03  994.44   88.97 1148.15   90.54
  1173.2   90.34 1181.68   88.21  1194.5   89.87 1206.34   90.33 1267.79   90.17
 1304.96   94.13 1436.82    96.9 1506.17   99.38 1551.81   99.76 1607.43  100.01
#Mann= 5 ,-1 , 0
       0    .045       0  699.87     .09       0  1173.2     .05       0
 1206.34     .08       0 1551.81     .04       0
#XS Ineff= 2 , 0
       0                    1320       0    96.5
Permanent Ineff=
       F       F
#Block Obstruct= 1 ,-1
    14.5    56.3     130
Bank Sta=1173.2,1206.34
XS Rating Curve= 0 ,0
Exp/Cntr=0.5,0.3

Type RM Length L Ch R = 1 ,2006    ,104.96,78.47,79.12
BEGIN DESCRIPTION:
Surveyed Section
END DESCRIPTION:
XS GIS Cut Line= 6
 2303269.8630739  689979.3179669 2303291.0298591  689694.8351998
 2303252.7746606  689323.7597748    2303265.7284     689022.6937
    2303236.6597     688894.5508 2303184.1689991  688561.7521267
#Sta/Elev= 30
       0  104.41     9.8  103.77    36.8  103.86  113.05  102.28  138.04  102.15
  174.15  101.27  184.26  100.58   211.6  100.34  283.38   98.52  527.2594.01514
  589.57   91.32  610.38   91.37  658.33   89.97  676.59   89.72  710.78   90.68
  808.26   89.11  846.64   88.01  897.62   88.22 1014.07  89.5771021.213  87.371
1049.068  89.603 1091.35  89.3481109.349  93.8361134.633  94.452 1174.18   93.86
 1190.78   94.14 1207.4895.51733 1230.74   97.18 1246.82    97.5 1428.47   99.06
#Mann= 5 ,-1 , 0
       0    .045       0  527.25     .09       0 1014.07     .05       0
1049.068     .08       0 1207.48     .04       0
#XS Ineff= 3 ,-1
 1009.07 1009.07   94.25 1061.71 1061.71   94.39    1150    1150      96
Permanent Ineff=
       F       F       F
Bank Sta=1014.07,1049.068
XS Rating Curve= 0 ,0
Exp/Cntr=0.5,0.3

Type RM Length L Ch R = 2 ,1963    ,,,
BEGIN DESCRIPTION:
Dirt Road (off Blaylock Road)
END DESCRIPTION:
Bridge Culvert--1,0,-1,-1, 0
Deck Dist Width WeirC Skew NumUp NumDn MinLoCord MaxHiCord MaxSubmerge Is_Ogee
36,11,2.6,0, 108, 108, , , 0.95, 0, 1,1,,
       0    2.53    7.23   13.99   20.55   25.17   30.68   36.39   44.12   60.32
   63.25   67.49   75.73   86.88   91.58   92.98   93.38   96.28  100.34   104.8
  107.58  110.43  120.73  130.79  132.53  139.25  139.77  140.31  153.59  166.62
  167.75   176.7  181.76   193.4   198.5  200.61  203.25  218.61  232.69  236.82
  241.33  255.22  267.52   273.8  280.87   281.4  294.54  314.01  316.29  317.88
  323.93   335.8  355.41  355.45  355.48   372.2  387.13  389.16   391.5  405.06
   409.1  417.31  421.39   424.5  440.21  447.65  453.82   462.3  479.58     490
   504.8  516.94  530.65  537.76  538.17 984.5081007.6251033.0541061.8061095.904
1119.7441152.108 1159.13 1170.91  1190.8 1201.64 1242.21  1275.5 1288.73 1294.34
 1300.47  1309.3 1317.41 1326.11  1340.7 1345.07 1347.72 1366.35 1373.49 1382.53
 1395.71 1409.56 1416.32 1433.89 1435.34 1435.65 1438.88 1444.83
  103.81   103.8  103.79  103.85  103.98  103.94   103.7  103.47   103.4  103.18
  102.98  103.06  102.77  102.68  102.74  102.63  102.62  102.55  102.35  102.07
  102.02  101.99  102.01  101.57   101.5   101.3  101.29  101.28   101.2  100.74
  100.71  100.49  100.42   100.3  100.31  100.28  100.26  100.04   99.55   99.42
   99.28   99.02   98.78   98.75   98.42   98.41   98.06   97.65   97.64   97.58
   97.46   97.22   96.59   96.59   96.59    96.5   96.29    96.3   96.24   95.93
    95.9   95.84   95.84   95.74   95.49   95.42   95.38   95.19   94.82    94.6
   94.36   94.28   93.99   93.86   93.85   94.64  94.274  94.449  94.532  94.394
  94.418  94.743   95.08   95.66   95.77   96.08   97.57   97.87   97.91   97.93
   97.96   98.05   98.13   98.19   98.37   98.43   98.43   98.62   98.68   98.68
   98.85   98.77   98.71   99.04   99.07   99.07   99.08   99.09
                                                                                
                                                                                
                                                                                
                                                                                
                                                                                
                                                                                
                                                                                
                                                                                
                                                                                
                                                                                
                                                                
       0    2.53    7.23   13.99   20.55   25.17   30.68   36.39   44.12   60.32
   63.25   67.49   75.73   86.88   91.58   92.98   93.38   96.28  100.34   104.8
  107.58  110.43  120.73  130.79  132.53  139.25  139.77  140.31  153.59  166.62
  167.75   176.7  181.76   193.4   198.5  200.61  203.25  218.61  232.69  236.82
  241.33  255.22  267.52   273.8  280.87   281.4  294.54  314.01  316.29  317.88
  323.93   335.8  355.41  355.45  355.48   372.2  387.13  389.16   391.5  405.06
   409.1  417.31  421.39   424.5  440.21  447.65  453.82   462.3  479.58     490
   504.8  516.94  530.65  537.76  538.17 984.5081007.6251033.0541061.8061095.904
1119.7441152.108 1159.13 1170.91  1190.8 1201.64 1242.21  1275.5 1288.73 1294.34
 1300.47  1309.3 1317.41 1326.11  1340.7 1345.07 1347.72 1366.35 1373.49 1382.53
 1395.71 1409.56 1416.32 1433.89 1435.34 1435.65 1438.88 1444.83
  103.81   103.8  103.79  103.85  103.98  103.94   103.7  103.47   103.4  103.18
  102.98  103.06  102.77  102.68  102.74  102.63  102.62  102.55  102.35  102.07
  102.02  101.99  102.01  101.57   101.5   101.3  101.29  101.28   101.2  100.74
  100.71  100.49  100.42   100.3  100.31  100.28  100.26  100.04   99.55   99.42
   99.28   99.02   98.78   98.75   98.42   98.41   98.06   97.65   97.64   97.58
   97.46   97.22   96.59   96.59   96.59    96.5   96.29    96.3   96.24   95.93
    95.9   95.84   95.84   95.74   95.49   95.42   95.38   95.19   94.82    94.6
   94.36   94.28   93.99   93.86   93.85   94.64  94.274  94.449  94.532  94.394
  94.418  94.743   95.08   95.66   95.77   96.08   97.57   97.87   97.91   97.93
   97.96   98.05   98.13   98.19   98.37   98.43   98.43   98.62   98.68   98.68
   98.85   98.77   98.71   99.04   99.07   99.07   99.08   99.09
                                                                                
                                                                                
                                                                                
                                                                                
                                                                                
                                                                                
                                                                                
                                                                                
                                                                                
                                                                                
                                                                
BR Coef=-1 , 0 , 0 ,, 0 ,,,0.8,-1,,0,
WSPro=,,,, 1 ,,,, 0 ,,,, 0 ,,,,-1 ,-1 ,-1 , 0 , 0 , 0 , 0 , 0
Multiple Barrel Culv=1,4,,25,0.012,0.2,1,1,3,87.9,87, 4,Culvert #1  , 0 ,28.9
 1036.21 1053.14 1040.71 1057.64 1045.21 1062.14 1049.71 1066.64
Culvert Bottom n=0.012
Culvert Bottom Depth=4
Culvert Depth Blocked=2
BC Design=,, 0 ,, 0 ,,,,,,
BC Use User HTab Curves=0
BC User HTab FreeFlow(D)= 0

Type RM Length L Ch R = 1 ,1928    ,477.1,427.77,427.09
XS GIS Cut Line= 6
 2303347.2974789  689980.3504257 2303367.9466535   689735.657706
 2303392.7256631  689592.1459421 2303345.2325614  689319.5768366
    2303343.6774      689021.006 2303270.7136487   688551.441803
#Sta/Elev= 30
       0  104.07   64.34  103.23  106.25  102.17  112.84  102.38  120.71  101.94
  400.85   96.14  594.4692.92027  646.49   90.61  692.89   90.24  719.01   89.48
   775.4   89.26  798.09   88.46  838.56   88.17  930.47   89.031007.702 89.1463
1034.558 88.71471040.623 90.04971051.163   88.91 1060.26 86.7018 1068.49 87.0671
 1070.49   88.931071.089 89.79221083.651  90.8781099.823 89.76631112.818 90.4148
  1125.7   94.34  1185.7    96.2 1234.41   98.68 1291.1498.39162 1443.91   98.93
#Mann= 5 ,-1 , 0
       0    .045       0  594.46     .09       01051.163     .05       0
 1070.49    .085       0 1291.14     .04       0
#XS Ineff= 2 , 0
       0 1041.14      91 1078.64       0      91
Permanent Ineff=
       F       F
Bank Sta=1051.163,1070.49
XS Rating Curve= 0 ,0
Exp/Cntr=0.5,0.3

Type RM Length L Ch R = 1 ,1500    ,743.76,658.18,586.94
XS GIS Cut Line= 6
  2303762.416069  689849.9667539 2303747.9298288  689585.5928693
 2303747.9298288  689268.7063639 2303733.4435885  688881.1994372
 2303664.6339473  688414.0181891 2303664.5523385  688413.4641082
#Sta/Elev= 30
       0  104.72   22.85  104.36   43.07   102.9   83.87  103.33      90  103.84
  119.34  103.17  133.15  101.03  189.37   98.53  215.98   96.47  244.24   99.94
  522.89    95.4  546.48   94.89  583.98   92.79  753.81   90.66  829.03   87.68
  889.75   88.11  918.28   87.53  925.47    86.2  928.72   87.43  981.06   88.53
 1060.56   88.03 1119.98   86.75 1175.42   91.21 1195.72   92.05 1207.48   91.82
 1236.48   93.29  1257.8   95.44 1275.58   96.39 1322.19   97.73 1441.66    98.5
#Mann= 5 ,-1 , 0
       0    .045       0  522.89     .09       0  918.28     .05       0
  928.72    .085       0 1275.58     .04       0
Bank Sta=918.28,928.72
XS Rating Curve= 0 ,0
Exp/Cntr=0.3,0.1

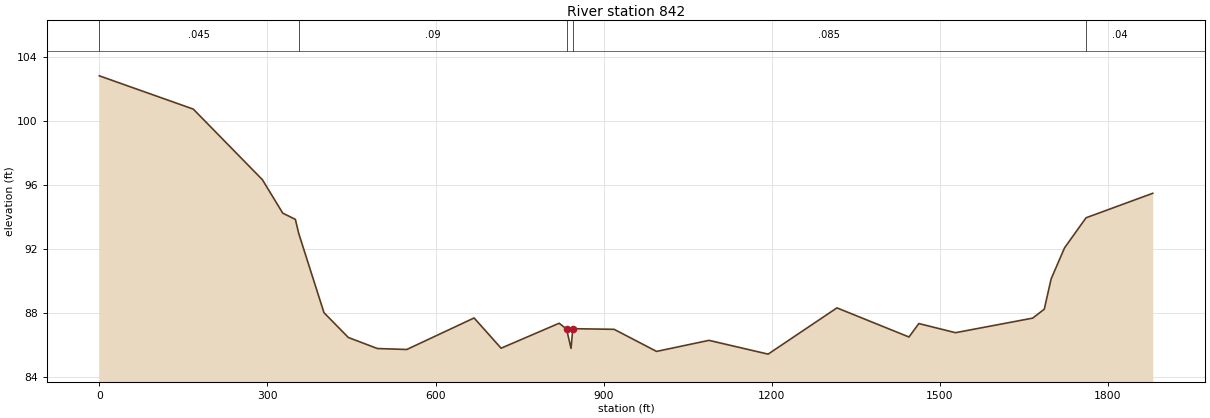
Type RM Length L Ch R = 1 ,842     ,1039.99,842,1153.09
XS GIS Cut Line= 6
 2304548.2946025    689623.61925 2304564.5916228  689409.9472063
 2304490.3496416  689170.9242422 2304298.4069582  688653.0411533
 2304207.8679567  688424.8828693 2303753.3621689  688006.5926821
#Sta/Elev= 30
       0  102.81  167.71  100.73     291   96.32  327.35   94.23  349.89   93.84
  355.89   92.96  400.93   88.01  444.41   86.46  496.33   85.77  548.74   85.71
  668.89   87.68  717.03   85.79  820.65   87.35  833.84   86.99  841.86   85.78
  845.02   87.01  918.79   86.97  994.48   85.59 1088.06   86.28 1193.62   85.42
 1316.44   88.31 1444.99   86.49 1462.57   87.33 1528.05   86.76 1665.81   87.67
 1686.47   88.23 1698.68   90.12 1722.63   92.06 1761.04   93.94 1880.05   95.47
#Mann= 5 ,-1 , 0
       0    .045       0  355.89     .09       0  833.84     .05       0
  845.02    .085       0 1761.04     .04       0
#XS Ineff= 2 , 0
       0  668.89         1316.44       0
Permanent Ineff=
       F       F
Bank Sta=833.84,845.02
XS Rating Curve= 0 ,0
Exp/Cntr=0.3,0.1

Chan Stop Cuts=-1
Use User Specified Reach Order=0
User Specified Reach Order=Black Crk       ,Tributary