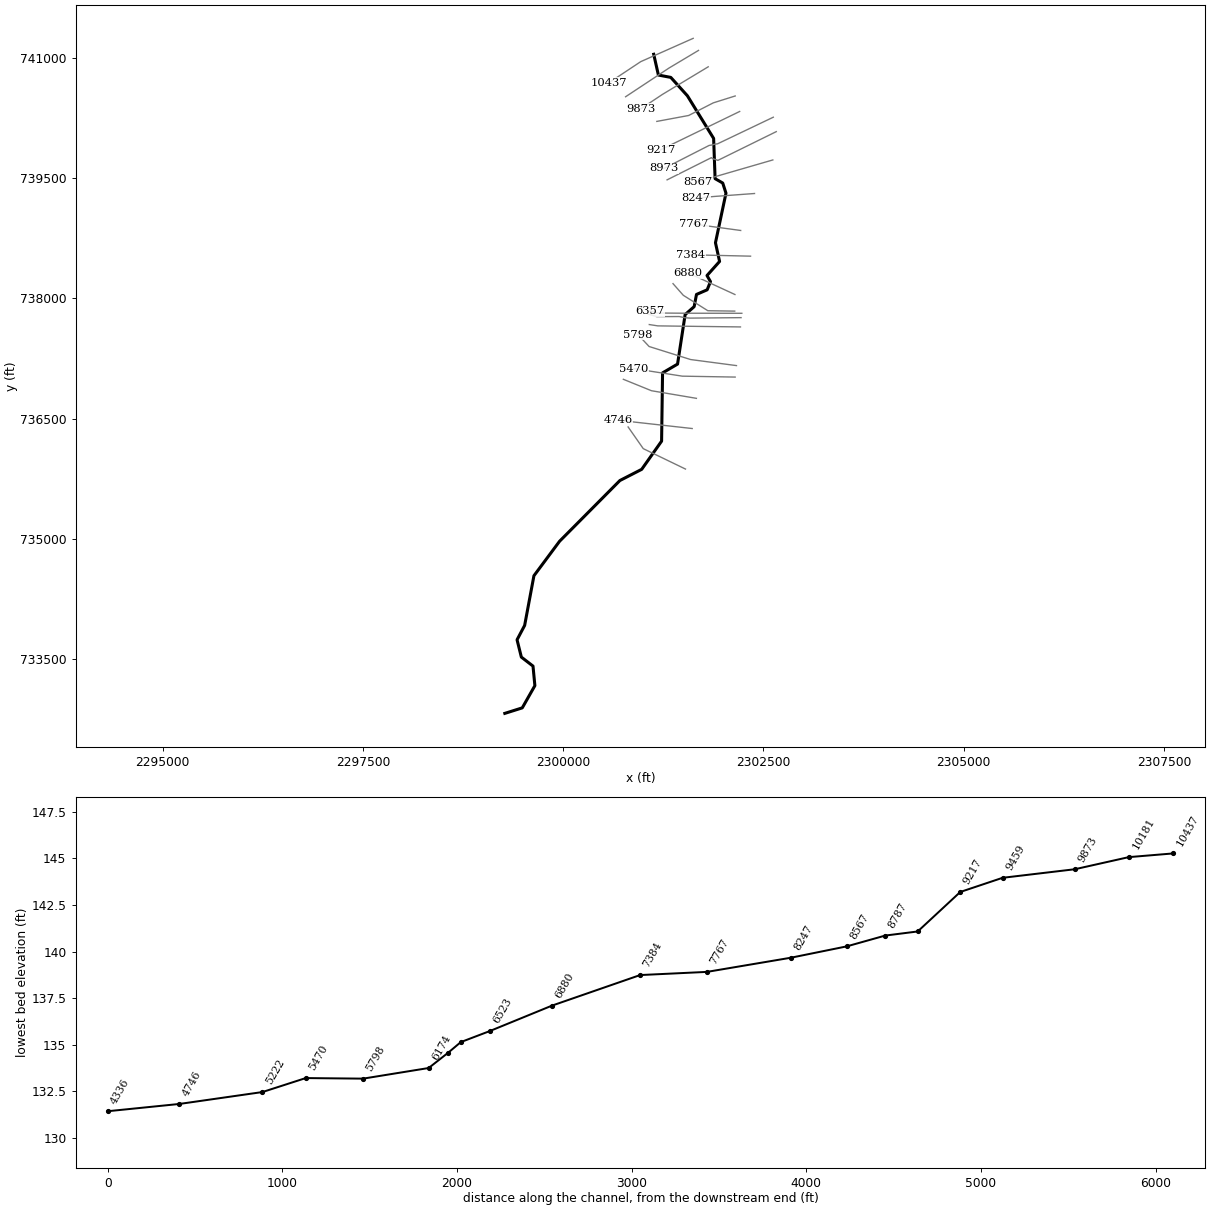
--- DTL_Bloomery_Swp_T3.prj (project) ---

Proj Title=DTL_Bloomery_Swp_T3
Current Plan=p01
Default Exp/Contr=0.3,0.1
English Units
Geom File=g01
Flow File=f01
Flow File=f02
Plan File=p01
Plan File=p02
Y Axis Title=Elevation
X Axis Title(PF)=Main Channel Distance
X Axis Title(XS)=Station
BEGIN DESCRIPTION:
END DESCRIPTION:
DSS Export Rating Curves= 0
DSS Export Rating Curve Sorted= 0
DSS Export Volume Flow Curves= 0
DXF OffsetX= 0
DXF OffsetY= 0
DXF ScaleX= 1
DXF ScaleY= 10

--- DTL_Bloomery_Swp_T3.p01 (plan) ---

Plan Title=DTL_Bloomery_Swp_T3
Program Version=4.00
Short Identifier=Multi Profile
Geom File=g01
Flow File=f01
Subcritical Flow
K Sum by GR= 0
Std Step Tol= 0.01
Critical Tol= 0.01
Num of Std Step Trials= 20
Max Error Tol= 0.3
Flow Tol Ratio= 0.001
Split Flow NTrial= 30
Split Flow Tol= 0.02
Split Flow Ratio= 0.02
Log Output Level= 0
Friction Slope Method= 1
Unsteady Friction Slope Method= 2
Unsteady Bridges Friction Slope Method= 1
Parabolic Critical Depth
Global Vel Dist= 0 , 0 , 0
Global Log Level= 0
CheckData=True
Encroach Param=-1 ,10,10, 2
Encroach River=Bloomery Swamp
Encroach Reach=Trib 3
Encroach Node=10437
       1     498     575
Encroach Node=10181
       1     537     613
Encroach Node=9873
       1     428     502
Encroach Node=9459
       1     490     565
Encroach Node=9217
       1     425     505
Encroach Node=8973
       1     731     853
Encroach Node=8787
       1     765     887
Encroach Node=8567
       1     687     795
Encroach Node=8247
       1     300     394
Encroach Node=7767
       1     221     304
Encroach Node=7384
       1     380     451
Encroach Node=6880
       1     318     362
Encroach Node=6523
       1     474     541
Encroach Node=6357
       1  652.25     810
Encroach Node=6286
       1  677.34     835
Encroach Node=6174
       1     642     905
Encroach Node=5798
       1   617.5    1020
Encroach Node=5470
       1     670    1070
Encroach Node=5222
       1     419     463
Encroach Node=4746
       1     330     405
Encroach Node=4336
       1     420     480
Encroach Node=3896
       1     422     476
Encroach Node=3492
       1     303     360
Encroach Node=2983
       1     465     526
Encroach Node=2476
       1     180     250
Encroach Node=2326
       1  251.75     327
Encroach Node=2261
       1  253.24     327
Encroach Node=2084
       1     180     214
Encroach Node=1851
       1     310     346
Encroach Node=1708
       1     869     911
Encroach Node=1477
       1     850  888.25
Encroach Node=1284
       1     675     775
Encroach Node=831
       1     230     335
Encroach Node=578
       1   69.18     215
Encroach Node=233
       1  139.55     280
Encroach Node=58
       1     370     490
Computation Interval=1HOUR
Output Interval=1HOUR
Run HTab= 0
Run UNet= 0
Run PostProcess= 0
Run WQNet= 0
UNET Theta= 1
UNET Theta Warmup= 1
UNET ZTol= 0.02
UNET ZSATol= 0.05
UNET MxIter= 20
UNET MaxInSteps= 0
UNET DtIC= 0
UNET DtMin= 0
UNET MaxCRTS= 20
UNET WFStab= 2
UNET SFStab= 1
UNET WFX= 1
UNET SFX= 1
UNET DSS MLevel= 4
UNET DZMax Abort= 100
UNET Convert EG Bridges= 0
UNET Use Existing IB Tables=-1
UNET Froude Reduction=False
UNET Froude Limit= 1
UNET Froude Power= 10
UNET Time Slicing=0,0, 5
Instantaneous Interval=1HOUR
Write IC File= 0
Echo Input=False
Echo Output=False
Write Detailed= 0
Detailed Automatic Start=False, 10
WQ ULTIMATE=-1
WQ Max Comp Step=1HOUR
WQ Output Interval=15MIN
WQ Output Selected Increments= 0
WQ Output face flow=0
WQ Output face velocity=0
WQ Output face area=0
WQ Output face dispersion=0
WQ Output cell volume=0
WQ Output cell surface area=0
WQ Output cell continuity=0
WQ Output face conc=0
WQ Output face dconc_dx=0
WQ Output face courant=0
WQ Output face peclet=0
WQ Output face adv mass=0
WQ Output face disp mass=0
WQ Output cell mass=0
WQ Output cell source sink temp=0
WQ Output cell source sink nsm=0
WQ Output MaxMinRange=-1
WQ Daily Max Min Mean=-1
WQ Daily Range=0
WQ Daily Time=0
WQ Create Restart=0
WQ Fixed Restart=0
WQ System Summary=False
Sorting and Armoring Iterations= 10
XS Update Threshold= 0.02
Hydraulics Update Threshold= 0.02
Energy Slope Method= 1
Volume Change Method= 0
XS Weighting Method= 0
Number of US Weighted Cross Sections= 1
Number of DS Weighted Cross Sections= 1
Upstream XS Weight=0.25
Main XS Weight=0.5
Downstream XS Weight=0.25
Number of DS XS's Weighted with US Boundary= 1
Upstream Boundary Weight= 1
Weight of XSs Associated with US Boundary= 0
Number of US XS's Weighted with DS Boundary= 1
Downstream Boundary Weight= 0.5
Weight of XSs Associated with DS Boundary= 0.5
Sediment Output Level= 4
Mass or Volume Output= 0
Output Increment Type= 1
Profile and TS Output Increment= 10
XS Output Flag= 0
XS Output Increment= 10
Disregard all LS=0
Disregard all Conn=0
Disregard all Breaches=0
Disregard all Pumps=0

--- DTL_Bloomery_Swp_T3.p02 (plan) ---

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Plan Title=DTL_Bloomery_Swp_T3_Future
Short Identifier=Future
Geom File=g01
Flow File=f02
Encroach Param=-1 ,0,0, 0

--- DTL_Bloomery_Swp_T3.f01 (steady flow) ---

Flow Title=DTL_Bloomery_Swp_T3
Program Version=4.00
Number of Profiles= 6
Profile Names=100-yr,FW,10-yr,25-yr,50-yr,500-yr
River Rch & RM=Bloomery Swamp,Trib 3          ,10437
     680     680     280     420     540    1100
River Rch & RM=Bloomery Swamp,Trib 3          ,3492
     750     750     310     460     600    1210
Boundary for River Rch & Prof#=Bloomery Swamp,Trib 3          , 1
Up Type= 0
Dn Type= 3
Dn Slope=3.714286E-03
Boundary for River Rch & Prof#=Bloomery Swamp,Trib 3          , 2
Up Type= 0
Dn Type= 3
Dn Slope=3.714286E-03
Boundary for River Rch & Prof#=Bloomery Swamp,Trib 3          , 3
Up Type= 0
Dn Type= 3
Dn Slope=3.714286E-03
Boundary for River Rch & Prof#=Bloomery Swamp,Trib 3          , 4
Up Type= 0
Dn Type= 3
Dn Slope=3.714286E-03
Boundary for River Rch & Prof#=Bloomery Swamp,Trib 3          , 5
Up Type= 0
Dn Type= 3
Dn Slope=3.714286E-03
Boundary for River Rch & Prof#=Bloomery Swamp,Trib 3          , 6
Up Type= 0
Dn Type= 3
Dn Slope=3.714286E-03
DSS Import GetInterval= 0
DSS Import GetPeak= 0
DSS Import FillOption= 0

--- DTL_Bloomery_Swp_T3.f02 (steady flow) ---

Flow Title=DTL_Bloomery_Swp_T3_Future
Program Version=4.00
Number of Profiles= 3
Profile Names=100-yr-10%,100-yr-20%,100-yr-35%
River Rch & RM=Bloomery Swamp,Trib 3          ,10437
    1190    1520    1860
River Rch & RM=Bloomery Swamp,Trib 3          ,3492
    1310    1680    2050
Boundary for River Rch & Prof#=Bloomery Swamp,Trib 3          , 1
Up Type= 0
Dn Type= 3
Dn Slope=3.714286E-03
Boundary for River Rch & Prof#=Bloomery Swamp,Trib 3          , 2
Up Type= 0
Dn Type= 3
Dn Slope=3.714286E-03
Boundary for River Rch & Prof#=Bloomery Swamp,Trib 3          , 3
Up Type= 0
Dn Type= 3
Dn Slope=3.714286E-03
DSS Import GetInterval= 0
DSS Import GetPeak= 0
DSS Import FillOption= 0

--- DTL_Bloomery_Swp_T3.g01 (geometry) ---

Geom Title=DTL_Bloomery_Swp_T3
Program Version=4.00

River Reach=Bloomery Swamp  ,Trib 3
Reach XY= 30
 2301129.8178698  741050.8927999 2301188.2432718  740791.1456386
 2301342.9638176  740762.0284879 2301550.2094194  740532.5168297
 2301877.9200956  739999.2733253 2301896.1896803  739496.8597451
 2301991.5340756  739442.0509909 2302032.0697168  739315.3057469
 2301900.7570765   738696.423564 2301952.1402835  738462.3445096
 2301795.1360398  738286.4997566 2301838.5263035  738210.5667951
 2301797.4197378  738108.3713054 2301663.8233995  738050.1370041
 2301634.7062488  737897.7001565 2301522.0834837  737798.3661559
 2301427.4606469  737180.0480312 2301240.2946135  737070.1628534
 2301228.2079885  736217.4692855  2300979.855821  735865.2088549
 2300707.5248236  735725.3323468 2299954.4753779  734966.5736559
 2299634.1867205  734535.5256411  2299518.274238  733914.9536568
 2299423.5155716  733735.6603845 2299477.1824767  733519.2799903
 2299622.7682301  733406.8078593 2299646.1761355  733162.4521635
 2299488.6009672  732884.9828454  2299270.755986  732816.1924755

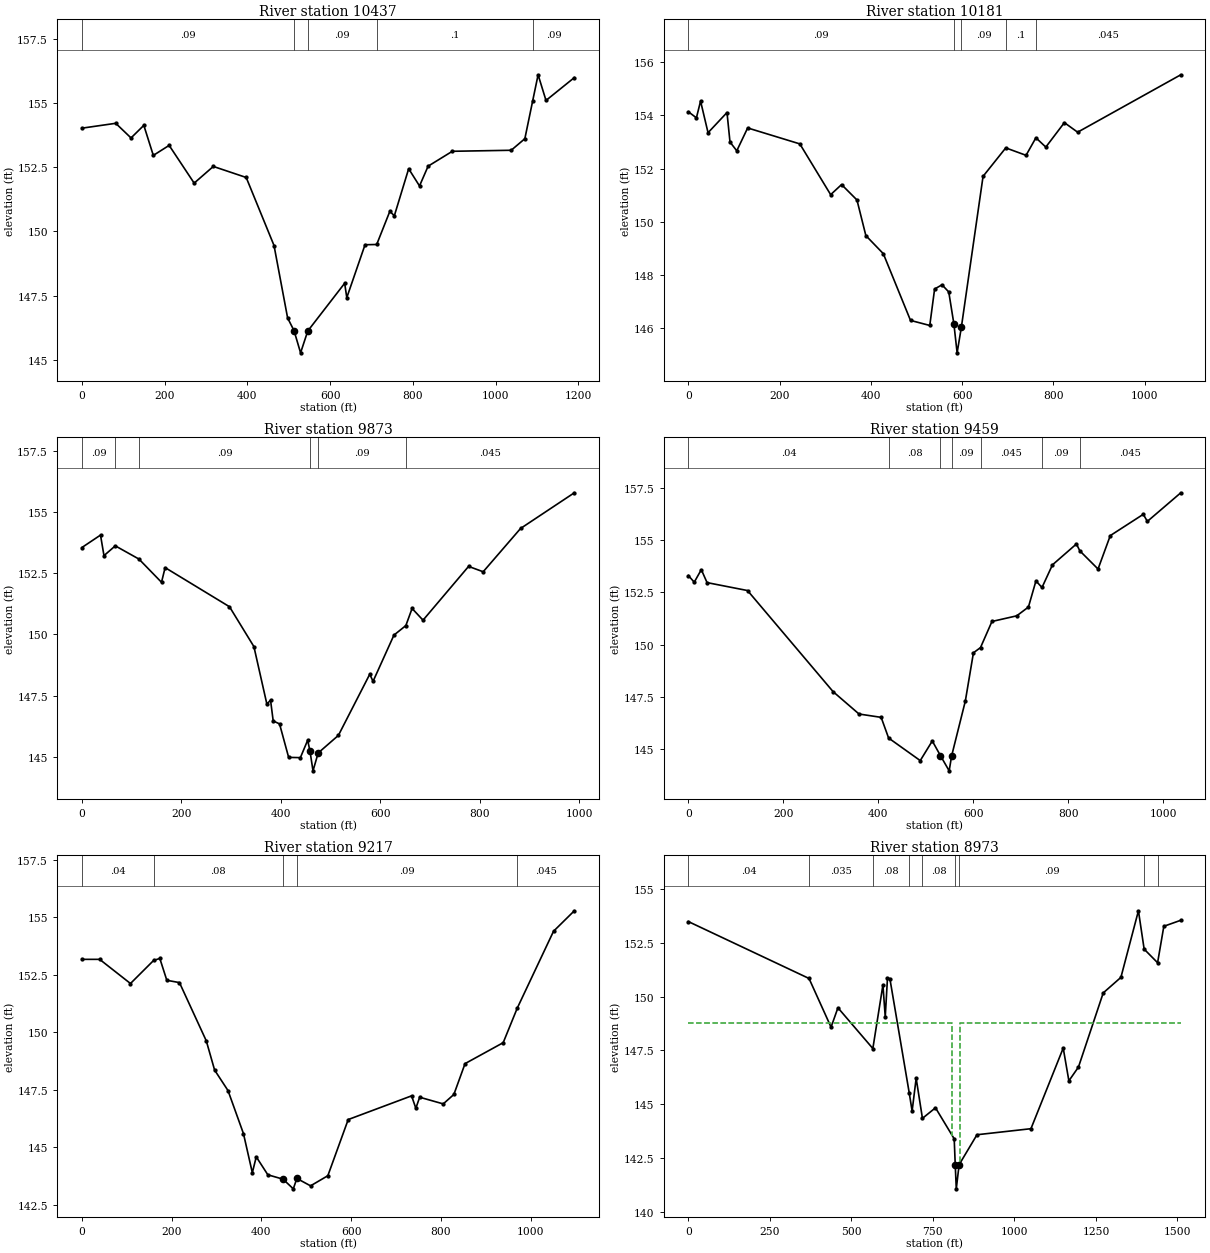
Type RM Length L Ch R = 1 ,10437   ,218.04,255.86,254.33
XS GIS Cut Line= 3
 2301622.7233446  741249.9842852 2300967.5829108  740958.5584768
 2300573.1469479  740696.7957844
#Sta/Elev= 30
       0  154.02   81.91  154.21  118.85  153.64  149.79  154.13  172.74  152.96
     211  153.35  271.48  151.88  317.77  152.53  397.27   152.1  464.53  149.45
  497.36  146.63  512.98  146.13  528.72  145.27  546.08  146.12  635.28  147.98
  640.41  147.42  684.53  149.48  712.71  149.49  744.44  150.78  755.39  150.61
  789.98  152.44  816.21  151.77  836.98  152.54  895.53  153.12 1037.83  153.16
 1070.83  153.61 1089.72  155.08 1102.86   156.1 1121.96   155.1 1190.43  155.99
#Mann= 5 ,-1 , 0
       0     .09       0  512.98     .05       0  546.08     .09       0
  712.71      .1       0 1089.72     .09       0
Bank Sta=512.98,546.08
XS Rating Curve= 0 ,0
Exp/Cntr=0.3,0.1

Type RM Length L Ch R = 1 ,10181   ,245.16,308.83,245.49
XS GIS Cut Line= 3
 2301689.1289149  741099.1169841 2301320.6877448  740878.8320517
 2300778.7478226  740520.1380025
#Sta/Elev= 30
       0  154.14   17.73  153.91   26.84  154.54   43.22  153.35   84.76  154.11
   91.32     153  106.18  152.67  130.03  153.53  244.34  152.93   311.9  151.02
  335.81   151.4  369.54  150.82  389.05  149.48   427.3   148.8  486.89  146.29
  529.09   146.1  539.68  147.47  555.91  147.63  570.72  147.36  582.01  146.15
  589.03  145.07  598.29  146.03  645.88  151.71  695.63  152.78  740.08   152.5
  761.67  153.16  783.39  152.81  824.05  153.73  853.12  153.37 1079.16  155.53
#Mann= 5 ,-1 , 0
       0     .09       0  582.01     .05       0  598.29     .09       0
  695.63      .1       0  761.67    .045       0
Bank Sta=582.01,598.29
XS Rating Curve= 0 ,0
Exp/Cntr=0.3,0.1

Type RM Length L Ch R = 1 ,9873    ,414.06,413.64,410.81
XS GIS Cut Line= 3
 2301810.4123002  740894.3631061 2301237.4670672  740548.6202931
 2300970.7511829  740370.8097035
#Sta/Elev= 30
       0  153.55   37.49  154.06   44.47  153.22    67.2  153.62  114.71  153.08
  160.08  152.13  167.35  152.73  296.72  151.13  345.78   149.5  371.83  147.15
  379.21  147.31  384.55  146.46   397.3  146.34  415.59  144.97   439.2  144.96
   453.8  145.67  458.37  145.24  464.55  144.42  474.92  145.15  515.59  145.87
   578.6  148.37  585.24  148.08  627.21  149.97  651.15  150.36  663.68  151.06
  685.65  150.58  777.24  152.78  806.54  152.56  881.66  154.33  989.73  155.79
#Mann= 6 ,-1 , 0
       0     .09       0    67.2     .04       0  114.71     .09       0
  458.37     .05       0  474.92     .09       0  651.15    .045       0
#XS Ineff= 2 , 0
       0                     595       0
Permanent Ineff=
       F       F
Bank Sta=458.37,474.92
XS Rating Curve= 0 ,0
Exp/Cntr=0.3,0.1

Type RM Length L Ch R = 1 ,9459    ,239.14,241.96,244.67
XS GIS Cut Line= 4
 2302147.2435973  740529.8851233 2301874.3242121  740444.1104594
 2301566.3151916  740286.2071008 2301168.6326587  740212.1289819
#Sta/Elev= 30
       0  153.31   12.48  152.99   27.35  153.59   39.46  152.97  124.67  152.59
   304.8  147.75  359.37  146.68  405.94  146.52  421.64  145.53  488.24  144.45
   513.6  145.39   530.7  144.69  549.13  143.96  554.26  144.67  583.15   147.3
  600.21  149.61  615.09  149.86  639.21  151.11  691.37  151.38  715.97   151.8
   731.8  153.05  744.58152.7372  766.56  153.82  817.04  154.82   824.2  154.49
  862.53  153.62   888.3  155.22   957.8  156.24  966.35   155.9 1036.73  157.27
#Mann= 7 ,-1 , 0
       0     .04       0  421.64     .08       0   530.7     .05       0
  554.26     .09       0  615.09    .045       0  744.58     .09       0
   824.2    .045       0
#XS Ineff= 2 , 0
       0     350                       0
Permanent Ineff=
       F       F
Bank Sta=530.7,554.26
XS Rating Curve= 0 ,0
Exp/Cntr=0.3,0.1

Type RM Length L Ch R = 1 ,9217    ,245.69,243.75,221.93
XS GIS Cut Line= 2
 2302203.0773521  740336.2354222 2301216.1480147  739857.2238691
#Sta/Elev= 30
       0  153.17   39.64  153.17   108.3  152.12  159.73  153.12  173.66  153.21
  189.28  152.26  217.43  152.16  277.18  149.63  295.72  148.36  325.54  147.47
  359.99   145.6  379.75   143.9   388.5  144.59   414.3  143.81  448.14  143.62
     471   143.2  478.96143.6518  509.45  143.33  547.96  143.77  593.33  146.21
   734.5  147.24  743.98   146.7  752.55  147.18  805.01  146.89   828.7   147.3
  853.61  148.64  938.58  149.55  969.89  151.05 1050.71  154.39 1097.03  155.28
#Mann= 5 ,-1 , 0
       0     .04       0  159.73     .08       0  448.14     .05       0
  478.96     .09       0  969.89    .045       0
#XS Ineff= 2 , 0
       0                     655       0
Permanent Ineff=
       F       F
Bank Sta=448.14,478.96
XS Rating Curve= 0 ,0
Exp/Cntr=0.5,0.3

Type RM Length L Ch R = 1 ,8973    ,191.68,185.8,148.53
BEGIN DESCRIPTION:
Surveyed Section
END DESCRIPTION:
XS GIS Cut Line= 6
 2302622.9079108  740264.6172681    2301926.4127     739931.8181
    2301883.2372     739925.9248    2301863.1907     739918.9922
    2301821.6179     739911.8708 2301259.6933909  739624.9930641
#Sta/Elev= 30
       0  153.48  370.16  150.84  437.72  148.58   458.8  149.48  565.89  147.59
  596.79  150.54  603.89  149.06   610.7  150.84  618.13  150.83  677.34  145.54
  686.29  144.69  698.72  146.21  717.97  144.35  757.99  144.84 815.369   143.4
  818.56  142.19 821.751  141.08  830.41   142.2  885.23  143.59 1050.73  143.87
  1149.7  147.61 1167.05  146.09 1196.44  146.73 1272.38  150.17 1326.59  150.89
 1380.35  153.98 1397.87   152.2  1439.1  151.57 1458.23  153.26 1510.24  153.54
#Mann= 9 ,-1 , 0
       0     .04       0  370.16    .035       0  565.89     .08       0
  677.34    .035       0  717.97     .08       0  818.56     .05       0
  830.41     .09       0 1397.87    .045       0  1439.1     .09       0
#XS Ineff= 2 , 0
       0   809.5  148.77   834.5       0  148.77
Permanent Ineff=
       F       F
Bank Sta=818.56,830.41
XS Rating Curve= 0 ,0
Exp/Cntr=0.5,0.3

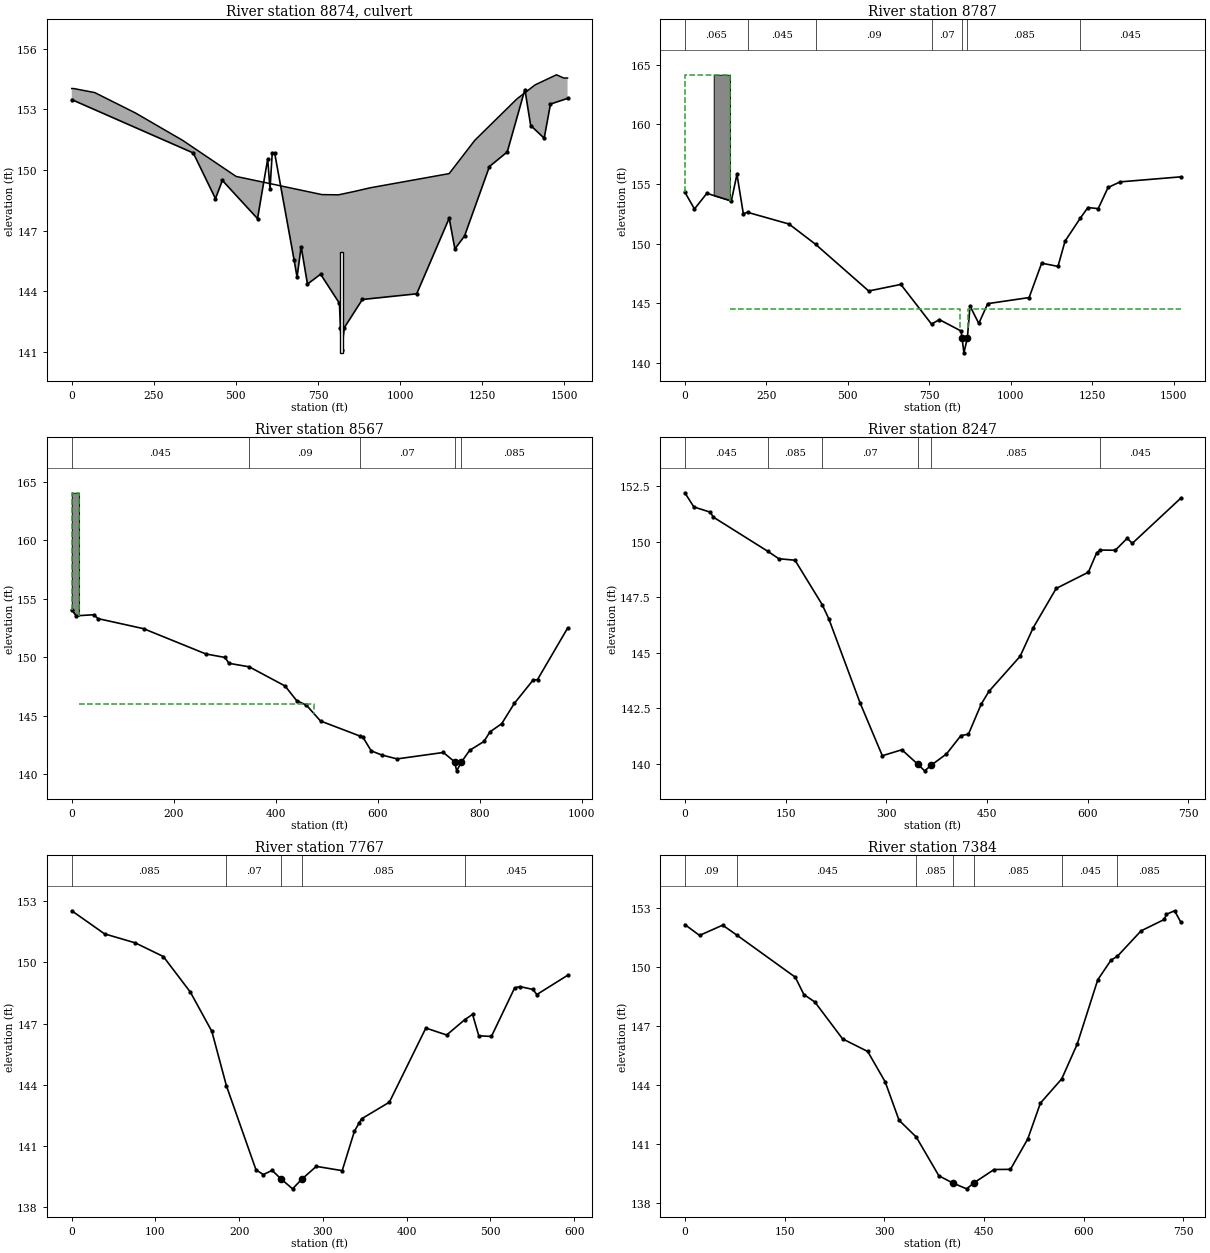
Type RM Length L Ch R = 2 ,8874    ,,,
BEGIN DESCRIPTION:
Packhouse Road
END DESCRIPTION:
Bridge Culvert--1,0,-1,-1, 0
Deck Dist Width WeirC Skew NumUp NumDn MinLoCord MaxHiCord MaxSubmerge Is_Ogee
87.25,21.5,2.6,0, 17, 17, , , 0.98, 0, 1,1,,
       0    5.49   69.86  194.02  338.25  500.62 762.397 812.876 861.787 909.739
 1149.63 1227.82 1356.25 1411.38 1476.51 1498.48 1510.24
  154.03  154.03  153.83  152.82  151.46  149.68  148.78  148.77  148.94  149.12
  149.82  151.47  153.52  154.21  154.71  154.55  154.55
                                                                                
                                                        
       0    5.49   69.86  194.02  338.25  500.62 762.397 812.876 861.787 909.739
 1149.63 1227.82 1356.25 1411.38 1476.51 1498.48 1510.24
  154.03  154.03  153.83  152.82  151.46  149.68  148.78  148.77  148.94  149.12
  149.82  151.47  153.52  154.21  154.71  154.55  154.55
                                                                                
                                                        
BR Coef=-1 , 0 , 0 ,, 0 ,,,0.8,-1,,0,
WSPro=,,,, 1 ,,,, 0 ,,,, 0 ,,,,-1 ,-1 ,-1 , 0 , 0 , 0 , 0 , 0
Culvert=2,5,8,37.5,0.013,0.4,1,8,1,140.95,822,140.85,857,Culvert #1  , 0 ,79.18
Culvert Bottom n=0.013
BC Design=,, 0 ,, 0 ,,,,,,
BC Use User HTab Curves=0
BC User HTab FreeFlow(D)= 0

Type RM Length L Ch R = 1 ,8787    ,208.03,220.2,227.07
BEGIN DESCRIPTION:
Surveyed Section
END DESCRIPTION:
XS GIS Cut Line= 6
 2302659.9517836  740084.3370871     2301931.569     739725.5434
    2301879.5301     739742.3794    2301871.4575     739742.9916
    2301850.1117     739759.4585 2301296.7372637  739481.7567558
#Sta/Elev= 30
       0  154.32   29.52  152.91   67.53  154.22  142.69  153.58  159.86  155.82
  179.39  152.52  192.29  152.63  319.55  151.65  401.16  149.95  564.16  146.04
  662.71  146.59  756.84  143.27  781.19  143.64 847.525  142.69  850.59   142.1
  856.28  140.86 866.921  142.11 875.015  144.78 901.969  143.32  929.29  144.98
 1056.36  145.49 1094.85  148.37 1144.95   148.1  1166.5  150.21 1212.92  152.12
 1236.77  153.03 1268.44  152.94  1298.6  154.71 1335.68  155.18 1521.28   155.6
#Mann= 7 ,-1 , 0
       0    .065       0  192.29    .045       0  401.16     .09       0
  756.84     .07       0  850.59     .05       0 866.921    .085       0
 1212.92    .045       0
#XS Ineff= 3 ,-1
       0   138.8  164.15   138.8   844.5   144.5   869.5    1600   144.5
Permanent Ineff=
       F       F       F
#Block Obstruct= 1 ,-1
   88.48   138.8 164.149
Bank Sta=850.59,866.921
XS Rating Curve= 0 ,0
Exp/Cntr=0.5,0.3

Type RM Length L Ch R = 1 ,8567    ,281.5,320.35,239.64
XS GIS Cut Line= 2
 2302617.0548249  739730.6212094 2301683.2806424  739459.6512483
#Sta/Elev= 30
       0  154.04    8.43  153.53   43.13  153.62   51.46  153.29  140.77  152.43
  262.93  150.27  300.55  149.97  308.25  149.47  347.98  149.17  418.35  147.53
  440.89  146.29  460.21  145.89  487.83  144.54  564.71  143.26  571.23  143.14
  587.18  141.99  608.13  141.63  637.99   141.3  728.82  141.85  750.61  141.06
   754.9  140.28  764.13  141.03  780.28  142.03  808.36  142.79  820.17  143.61
  843.19  144.31  867.89  146.04  904.56  148.03  913.41  148.08   972.3  152.47
#Mann= 5 ,-1 , 0
       0    .045       0  347.98     .09       0  564.71     .07       0
  750.61     .05       0  764.13    .085       0
#XS Ineff= 2 ,-1
       0   14.34  164.04   14.34     476     146
Permanent Ineff=
       F       F
#Block Obstruct= 1 ,-1
       0   14.34 164.044
Bank Sta=750.61,764.13
XS Rating Curve= 0 ,0
Exp/Cntr=0.3,0.1

Type RM Length L Ch R = 1 ,8247    ,422.63,480.14,384.01
XS GIS Cut Line= 3
 2302388.2967163  739311.3549408 2301884.5000459   739274.311068
 2301652.3584428  739252.0847443
#Sta/Elev= 30
       0   152.2   13.48  151.56   37.53  151.33    42.6   151.1  123.16  149.57
  139.85  149.23  164.06  149.16  204.53  147.16  214.26  146.53  260.99  142.73
  294.11  140.35  323.18  140.62  347.18  139.96  357.15  139.67  367.19  139.93
  389.62  140.43  411.19  141.26  422.34  141.32  441.28  142.67  452.84  143.25
   499.3  144.83  518.85  146.12  553.05  147.89  600.95  148.62  613.29  149.49
  618.52  149.62  641.08  149.61  658.84  150.15  666.38  149.92  738.36  151.95
#Mann= 6 ,-1 , 0
       0    .045       0  123.16    .085       0  204.53     .07       0
  347.18     .05       0  367.19    .085       0  618.52    .045       0
Bank Sta=347.18,367.19
XS Rating Curve= 0 ,0
Exp/Cntr=0.3,0.1

Type RM Length L Ch R = 1 ,7767    ,345.58,382.48,358.86
XS GIS Cut Line= 2
 2302215.4734437  738849.4814798 2301628.6967654  738929.4078712
#Sta/Elev= 30
       0  152.52   39.18  151.39   75.78  150.95  109.41  150.28  141.63  148.54
  167.31  146.62  184.76  143.95  220.06  139.84  228.75  139.61  239.33  139.81
  250.43  139.38  263.72  138.91  274.72  139.38  292.09  140.01  323.03   139.8
  337.63  141.73  343.01  142.12  346.24  142.34  379.35  143.15  422.96  146.78
   447.8  146.44  469.43  147.19  478.74  147.45  486.18   146.4  501.28  146.37
  529.07  148.75  535.45  148.81  550.82  148.67  555.51  148.42   592.2  149.36
#Mann= 5 ,-1 , 0
       0    .085       0  184.76     .07       0  250.43     .05       0
  274.72    .085       0  469.43    .045       0
Bank Sta=250.43,274.72
XS Rating Curve= 0 ,0
Exp/Cntr=0.3,0.1

Type RM Length L Ch R = 1 ,7384    ,382.74,504.48,324.86
XS GIS Cut Line= 2
 2302338.9048858  738528.4944285 2301593.0882463  738545.7815692
#Sta/Elev= 30
       0  152.15   22.12   151.6   56.86  152.12   78.48  151.61  166.15  149.48
  179.11   148.6  195.65  148.22  237.36  146.35  275.14  145.71  301.43  144.17
  322.32  142.22  348.17  141.37  382.29   139.4   403.6  139.03  424.03  138.74
   435.3  139.05  465.28  139.72  489.94  139.73  515.98  141.27  535.02  143.09
  567.12  144.32  590.34  146.08  621.35  149.35   641.4  150.35  650.68150.5354
  686.45  151.83  721.51  152.41  724.52  152.67  736.91  152.85  746.02  152.29
#Mann= 7 ,-1 , 0
       0     .09       0   78.48    .045       0  348.17    .085       0
   403.6     .05       0   435.3    .085       0  567.12    .045       0
  650.68    .085       0
#XS Ineff= 2 , 0
       0     345                       0
Permanent Ineff=
       F       F
Bank Sta=403.6,435.3
XS Rating Curve= 0 ,0
Exp/Cntr=0.3,0.1

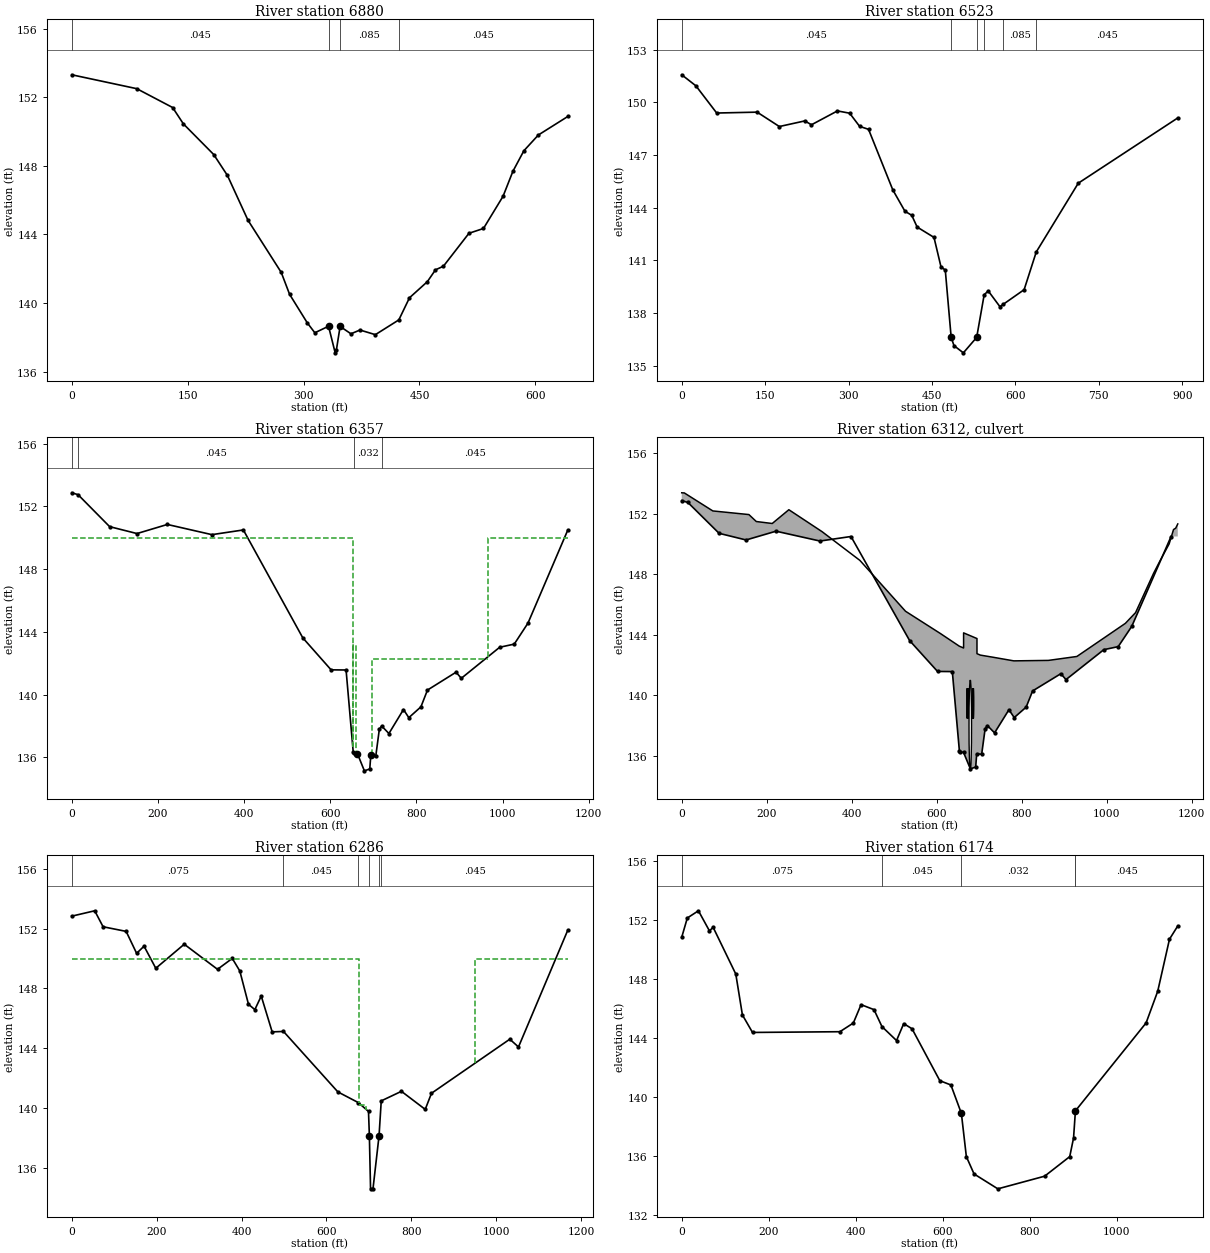
Type RM Length L Ch R = 1 ,6880    ,315.42,357.16,291.03
XS GIS Cut Line= 2
 2302143.8071556  738049.3936734 2301560.9835566  738318.5791492
#Sta/Elev= 30
       0  153.31   84.09   152.5  130.55   151.4  144.39  150.45   183.7  148.66
  201.45  147.44  228.04  144.83  271.06  141.79   281.9  140.51  304.75  138.85
  314.55  138.27  332.29  138.65  340.89   137.1   342.5  137.28  347.27  138.64
  361.27  138.21  372.93  138.43  392.91  138.16  423.26  139.02  437.05  140.31
  460.21  141.25   470.7  141.94  480.97  142.15  514.02  144.07  532.81  144.35
  558.18  146.23  570.86  147.68  585.08  148.88  603.84   149.8  641.98  150.88
#Mann= 4 ,-1 , 0
       0    .045       0  332.29     .05       0  347.27    .085       0
  423.26    .045       0
Bank Sta=332.29,347.27
XS Rating Curve= 0 ,0
Exp/Cntr=0.3,0.1

Type RM Length L Ch R = 1 ,6523    ,119.08,165.18,239.46
XS GIS Cut Line= 4
 2302141.3375641  737841.9479855 2301805.4731172  737846.8871686
 2301499.2437685  738039.5153073 2301370.8250094  738185.2212071
#Sta/Elev= 30
       0  151.58    25.5  150.95   62.88   149.4  135.58  149.45  175.51  148.63
  221.25  148.95  233.28  148.73  279.98  149.52  301.93  149.39  319.82  148.64
   335.9  148.47  379.49  145.02  401.37   143.8  413.58  143.57  423.27   142.9
  453.58  142.31  466.16  140.63  473.87  140.45  484.43  136.62  489.51  136.14
  506.38  135.73  530.32  136.61  543.79  139.04  551.12  139.26  572.15  138.36
  578.22   138.5  615.63  139.33  637.44  141.48  712.99   145.4   891.9  149.12
#Mann= 6 ,-1 , 0
       0    .045       0  484.43     .05       0  530.32    .032       0
  543.79    .045       0  578.22    .085       0  637.44    .045       0
Bank Sta=484.43,530.32
XS Rating Curve= 0 ,0
Exp/Cntr=0.5,0.3

Type RM Length L Ch R = 1 ,6357    ,71.85,70.99,56.51
XS GIS Cut Line= 4
 2302230.2428588  737814.7824788 2301538.5265846  737815.5366768
  2301171.269864  737818.2749112 2301082.3371856  737843.7308663
#Sta/Elev= 30
       0  152.87   14.51  152.75    87.9  150.71  151.39  150.27  221.85  150.85
  325.25   150.2  398.29   150.5  536.24  143.62  601.93  141.58  636.73  141.57
  653.28  136.35  655.31  136.26  663.14  136.23  679.22  135.14  691.72  135.26
  694.12  136.13  705.82  136.11  713.93  137.79  719.33     138  736.16  137.52
  769.98  139.05  782.35  138.53  810.46  139.22  825.65  140.29  892.07  141.43
  904.19  141.04  993.29  143.02 1027.09  143.22 1058.98  144.56 1151.49   150.5
#Mann= 4 ,-1 , 0
       0     .09       0   14.51    .045       0  655.31    .032       0
  719.33    .045       0
#XS Ineff= 4 ,-1
       0  652.25     150  652.25  660.75  143.15  697.25  965.98  142.28
  965.98    1200     150
Permanent Ineff=
       F       F       F       F
Bank Sta=663.14,694.12
XS Rating Curve= 0 ,0
Exp/Cntr=0.5,0.3

Type RM Length L Ch R = 2 ,6312    ,,,
BEGIN DESCRIPTION:
Private Drive
END DESCRIPTION:
Bridge Culvert--1,0,-1,-1, 0
Deck Dist Width WeirC Skew NumUp NumDn MinLoCord MaxHiCord MaxSubmerge Is_Ogee
40.25,9.5,2.6,0, 30, 30, , , 0.98, 0, 0.63,0.63,,
       0    6.12   73.15  158.06  175.49  212.95  252.06  330.23  419.24  526.56
  609.07 653.201  663.25  663.25  694.75  694.75 702.698 732.412  781.31  862.76
  929.79 1043.96 1067.96 1110.36 1125.24 1146.74 1147.04 1157.24 1162.34 1167.25
  153.39  153.38  152.19  151.95  151.49  151.36  152.27  150.82  148.92  145.56
  144.08  143.25  143.13  144.13 143.755 142.755  142.66  142.52  142.28  142.31
  142.57  144.76  145.47  148.07  148.88     150  150.02  150.96  151.05  151.33
                                                                                
                                                                                
                                                                                
       0    6.12   73.15  158.06  175.49  212.95  252.06  330.23  419.24  526.56
  609.07 653.201  696.25  696.25 702.698  727.75  727.75 732.412  781.31  862.76
  929.79 1043.96 1067.96 1110.36 1125.24 1146.74 1147.04 1157.24 1162.34 1167.25
  153.39  153.38  152.19  151.95  151.49  151.36  152.27  150.82  148.92  145.56
  144.08  143.25142.7369143.7369  143.66 143.542 142.542  142.52  142.28  142.31
  142.57  144.76  145.47  148.07  148.88     150  150.02  150.96  151.05  151.33
                                                                                
                                                                                
                                                                                
BR Coef=-1 , 0 , 0 ,, 0 ,,,0.8,-1,,0,
WSPro=,,,, 1 ,,,, 0 ,,,, 0 ,,,,-1 ,-1 ,-1 , 0 , 0 , 0 , 0 , 0
Multiple Barrel Culv=1,2,,19,0.024,0.5,1,2,1,138.47,138.18, 4,Culvert #2  , 0 ,35.67
  671.75  704.75     674     707     684     717  686.25  719.25
Culvert Bottom n=0.024
Culvert=1,6,,19,0.012,0.2,1,55,1,135.01,679,134.2,712,Culvert #1  , 0 ,35.67
Culvert Bottom n=0.012
BC Design=,, 0 ,, 0 ,,,,,,
BC Use User HTab Curves=0
BC User HTab FreeFlow(D)= 0

Type RM Length L Ch R = 1 ,6286    ,102.62,112.84,155.42
BEGIN DESCRIPTION:
Surveyed Section
END DESCRIPTION:
XS GIS Cut Line= 6
 2302220.3644927  737760.4514653    2301584.2603     737754.5375
    2301519.8596     737759.1432    2301448.2003     737774.1803
 2301168.6712237   737772.821546 2301060.4291877  737804.4253406
#Sta/Elev= 30
       0  152.84   54.03   153.2   73.71  152.13  128.08  151.82  152.76  150.35
  170.25  150.83  197.91  149.35  264.92  150.96  343.33  149.28  378.06  150.01
  395.83  149.17  416.25  146.94  431.24  146.58  446.33  147.49  472.06  145.09
  498.75  145.12  626.89  141.07 675.327  140.35 699.008  139.76 701.044  138.15
 703.833  134.58 709.608  134.59 723.842  138.13 729.023  140.47 776.567  141.11
  832.62   139.9   847.4  140.98 1031.85   144.6 1052.35  144.08 1168.58  151.91
#Mann= 6 ,-1 , 0
       0    .075       0  498.75    .045       0 675.327    .032       0
 701.044     .05       0 723.842    .032       0 729.023    .045       0
#XS Ineff= 4 ,-1
       0  677.34     150  677.34  693.75  140.18  730.25  950.23  140.18
  950.23    1200     150
Permanent Ineff=
       F       F       F       F
Bank Sta=701.044,723.842
XS Rating Curve= 0 ,0
Exp/Cntr=0.5,0.3

Type RM Length L Ch R = 1 ,6174    ,415.01,375.4,312.03
XS GIS Cut Line= 4
 2302212.9557182  737644.3806638 2301451.1540129  737653.9533218
 2301180.7424221  737657.5308899 2301074.4740268  737674.0157621
#Sta/Elev= 30
       0  150.85   12.85  152.16   38.36  152.65   63.77  151.28   72.12  151.53
  124.24  148.35  139.44  145.57  162.65  144.38  363.44  144.43  394.31  145.02
  412.07  146.27  441.82  145.93  460.04  144.78  493.57  143.83  510.09  144.98
  529.22  144.63  593.09   141.1  618.49  140.81  642.57  138.88  654.02  135.94
  671.77  134.76  726.38  133.75  833.91  134.61  891.56  135.94  900.36  137.21
  904.63  139.05 1067.08  145.03 1093.74  147.18 1120.79  150.72 1139.84  151.62
#Mann= 5 ,-1 , 0
       0    .075       0  460.04    .045       0  642.57    .032       0
  904.63    .032       0  904.63    .045       0
#XS Ineff= 2 , 0
       0     642             905       0
Permanent Ineff=
       F       F
Bank Sta=642.57,904.63
XS Rating Curve= 0 ,0
Exp/Cntr=0.3,0.1

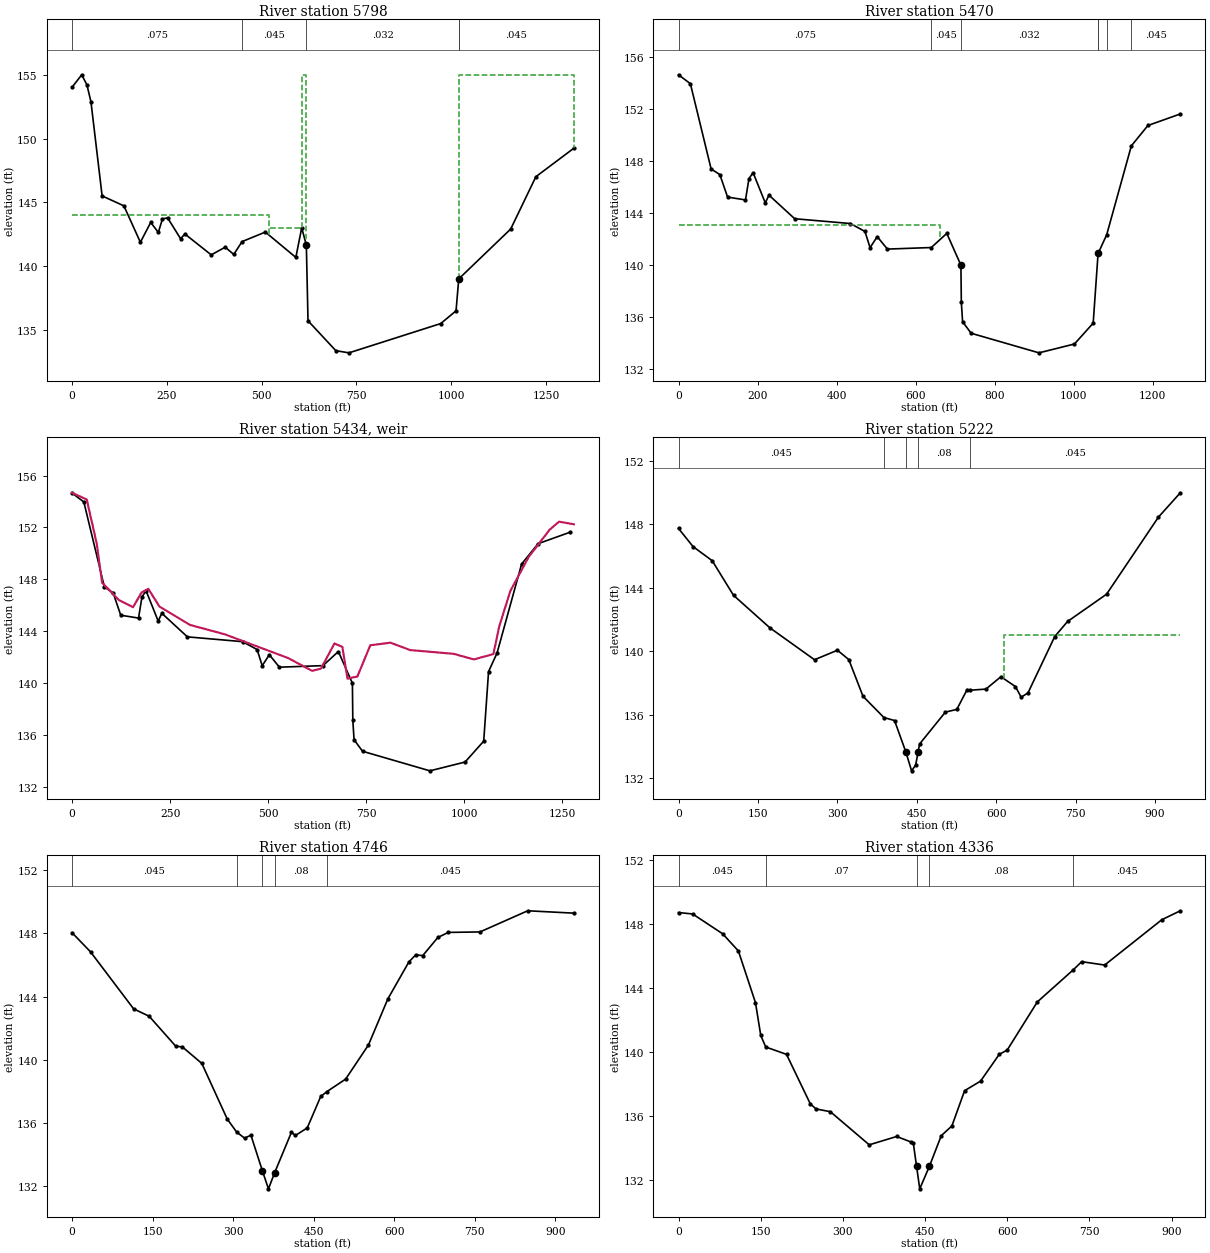
Type RM Length L Ch R = 1 ,5798    ,239.53,328.4,293.19
XS GIS Cut Line= 4
 2302162.8389908  737161.2801395 2301590.6186548  737236.8980628
 2301072.0044353  737399.8911032 2300933.7073101  737548.0665945
#Sta/Elev= 30
       0  154.05   25.48  155.03   39.16  154.24    49.8  152.91   79.27  145.51
   136.7  144.73  180.16  141.87  207.48  143.43  227.46  142.64  238.37   143.7
  251.89  143.79  286.19  142.15  297.53  142.52  366.99  140.88  403.94  141.48
   426.5  140.91  448.27  141.92  509.78  142.67   590.2  140.68  605.67     143
   617.9  141.65  622.31   135.7  695.69  133.35  730.36  133.18  972.26  135.48
 1012.77  136.48 1019.92  138.99 1156.92  142.91 1223.34  147.02 1323.51  149.26
#Mann= 5 ,-1 , 0
       0    .075       0  448.27    .045       0   617.9    .032       0
 1019.92    .032       0 1019.92    .045       0
#XS Ineff= 4 ,-1
       0     519     144     519  605.67     143  605.67   617.5     155
    1020    1400     155
Permanent Ineff=
       F       F       F       F
Bank Sta=617.9,1019.92
XS Rating Curve= 0 ,0
Exp/Cntr=0.5,0.3

Type RM Length L Ch R = 1 ,5470    ,251.27,247.67,240.83
XS GIS Cut Line= 3
 2302146.8608206  737017.8085184   2301486.99526   737029.304434
 2300884.3154797  737123.2968528
#Sta/Elev= 30
       0  154.65   30.01  153.96   82.44  147.39  104.65  146.95  124.08  145.22
  169.47     145  178.26  146.65  188.76   147.1  219.54  144.77  228.81  145.37
  293.99  143.55  434.85  143.18  471.77  142.57  484.73  141.32  502.84  142.17
  528.61  141.21  639.66  141.33  678.92  142.42  714.64  139.97   715.7  137.11
  718.89  135.61  740.51  134.72  912.19  133.21 1001.89  133.89  1049.4   135.5
 1061.77  140.87 1083.51  142.31 1145.99  149.17 1187.95  150.74 1269.93  151.63
#Mann= 7 ,-1 , 0
       0    .075       0  639.66    .045       0  714.64    .032       0
 1061.77    .032       0 1061.77    .045       0 1083.51     .08       0
 1145.99    .045       0
#XS Ineff= 2 , 0
       0  662.78  143.04    1070       0
Permanent Ineff=
       F       F
Bank Sta=714.64,1061.77
XS Rating Curve= 0 ,0
Exp/Cntr=0.5,0.3

Type RM Length L Ch R = 5 ,5434    ,,,
BEGIN DESCRIPTION:
Private Dam w/spillway
END DESCRIPTION:
IW Pilot Flow=0
#Inline Weir SE= 30
       0  154.67   37.44  154.15   62.77  150.76   76.49  147.74  119.04   146.4
  155.54  145.84   176.8  146.96  194.24  147.26  222.73  145.89   300.7  144.47
  389.11  143.75  550.36  141.92  611.84  140.93  634.47   141.1 668.903  143.04
 688.982  142.78 702.138  140.32 727.281  140.49 760.301   142.9  811.54   143.1
 862.131  142.53 972.861  142.241024.236  141.811074.019  142.22 1089.11  144.37
 1117.39   147.1 1163.93  149.71 1217.36  151.82 1241.42  152.44 1279.22  152.24
IW Dist,WD,Coef,Skew,MaxSub,Min_El,Is_Ogee,SpillHt,DesHd
31.7,8,2.6,0,0.98,, 0 ,,,2,5,

Type RM Length L Ch R = 1 ,5222    ,400.13,476.37,422.46
XS GIS Cut Line= 3
 2301662.8313402  736752.1778436 2301101.8224662  736847.2914171
 2300750.9575375  736989.9389106
#Sta/Elev= 30
       0  147.73   27.39  146.59    63.6   145.7  103.83  143.52  172.56  141.47
  256.84  139.46  300.14  140.06  321.58  139.47  348.39  137.16  387.83  135.82
  407.98  135.63  429.24  133.66  440.15  132.46  447.83  132.82  452.59  133.66
  455.28  134.15  503.99  136.16  525.61  136.33  545.06  137.58  550.75  137.54
  580.44  137.61  608.93  138.39  636.27  137.77  647.21   137.1  660.04  137.37
  710.54  140.92  734.75  141.87  808.45  143.59   906.5  148.45  947.77  149.98
#Mann= 5 ,-1 , 0
       0    .045       0  387.83     .07       0  429.24     .05       0
  452.59     .08       0  550.75    .045       0
#XS Ineff= 2 , 0
       0                     615       0     141
Permanent Ineff=
       F       F
Bank Sta=429.24,452.59
XS Rating Curve= 0 ,0
Exp/Cntr=0.5,0.3

Type RM Length L Ch R = 1 ,4746    ,413.7,409.89,333.78
XS GIS Cut Line= 2
  2301610.375387  736375.0106218 2300681.8089749  736478.7334657
#Sta/Elev= 30
       0  148.04   34.34  146.83  114.59  143.22  143.55  142.75   193.1  140.85
   205.4  140.81  241.65  139.76  288.93  136.24  306.56  135.41  321.29  135.03
  333.02  135.22  354.58  132.94  365.67  131.82  377.19  132.84  408.43   135.4
  415.91   135.2  437.91  135.68     463  137.67  474.65  137.98   509.4  138.77
  551.86  140.93     588  143.85  627.17  146.19  639.88  146.64  652.95  146.59
  681.09  147.74   700.5  148.06  759.54  148.09  848.39  149.43  934.34  149.28
#Mann= 5 ,-1 , 0
       0    .045       0  306.56     .07       0  354.58     .05       0
  377.19     .08       0  474.65    .045       0
Bank Sta=354.58,377.19
XS Rating Curve= 0 ,0
Exp/Cntr=0.3,0.1

Type RM Length L Ch R = 1 ,4336    ,447.44,439.65,365.32
XS GIS Cut Line= 3
 2301526.4092753  735868.7443599 2300999.3718549  736123.6513475
  2300810.227734   736394.767354
#Sta/Elev= 30
       0  148.69   25.83   148.6   80.64  147.36  109.24  146.29  140.46  143.06
  150.11  141.01   159.2  140.29  197.12  139.83  240.66  136.73  251.14  136.42
  277.11  136.25  348.14  134.18  398.19   134.7  424.15  134.36  428.63  134.27
  434.51  132.84  440.33  131.43   458.1  132.85  479.59  134.75  499.04  135.36
   522.2  137.56  551.37  138.16  585.45  139.83  600.01   140.1  655.04  143.11
   719.9  145.09  735.95  145.62  777.93  145.41  882.18  148.24  916.02   148.8
#Mann= 5 ,-1 , 0
       0    .045       0   159.2     .07       0  434.51     .05       0
   458.1     .08       0   719.9    .045       0
Bank Sta=434.51,458.1
XS Rating Curve= 0 ,0
Exp/Cntr=0.3,0.1