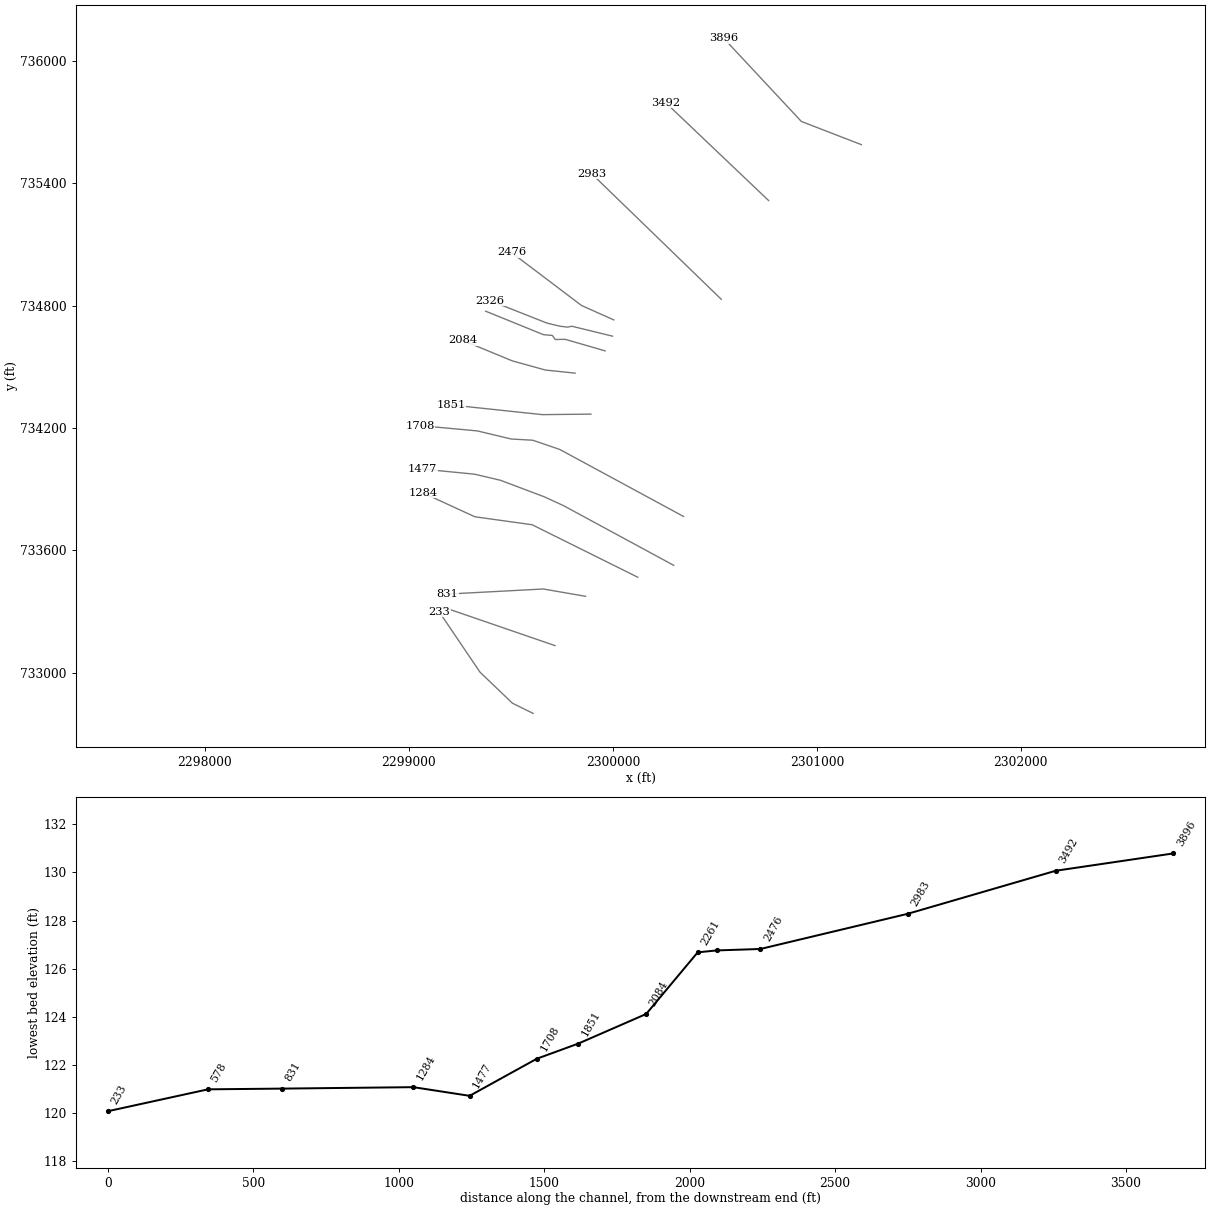
HEC-RAS study DTL_Bloomery_Swp_T3.prj: DTL_Bloomery_Swp_T3

--- DTL_Bloomery_Swp_T3.g01 (geometry) --- (continued)

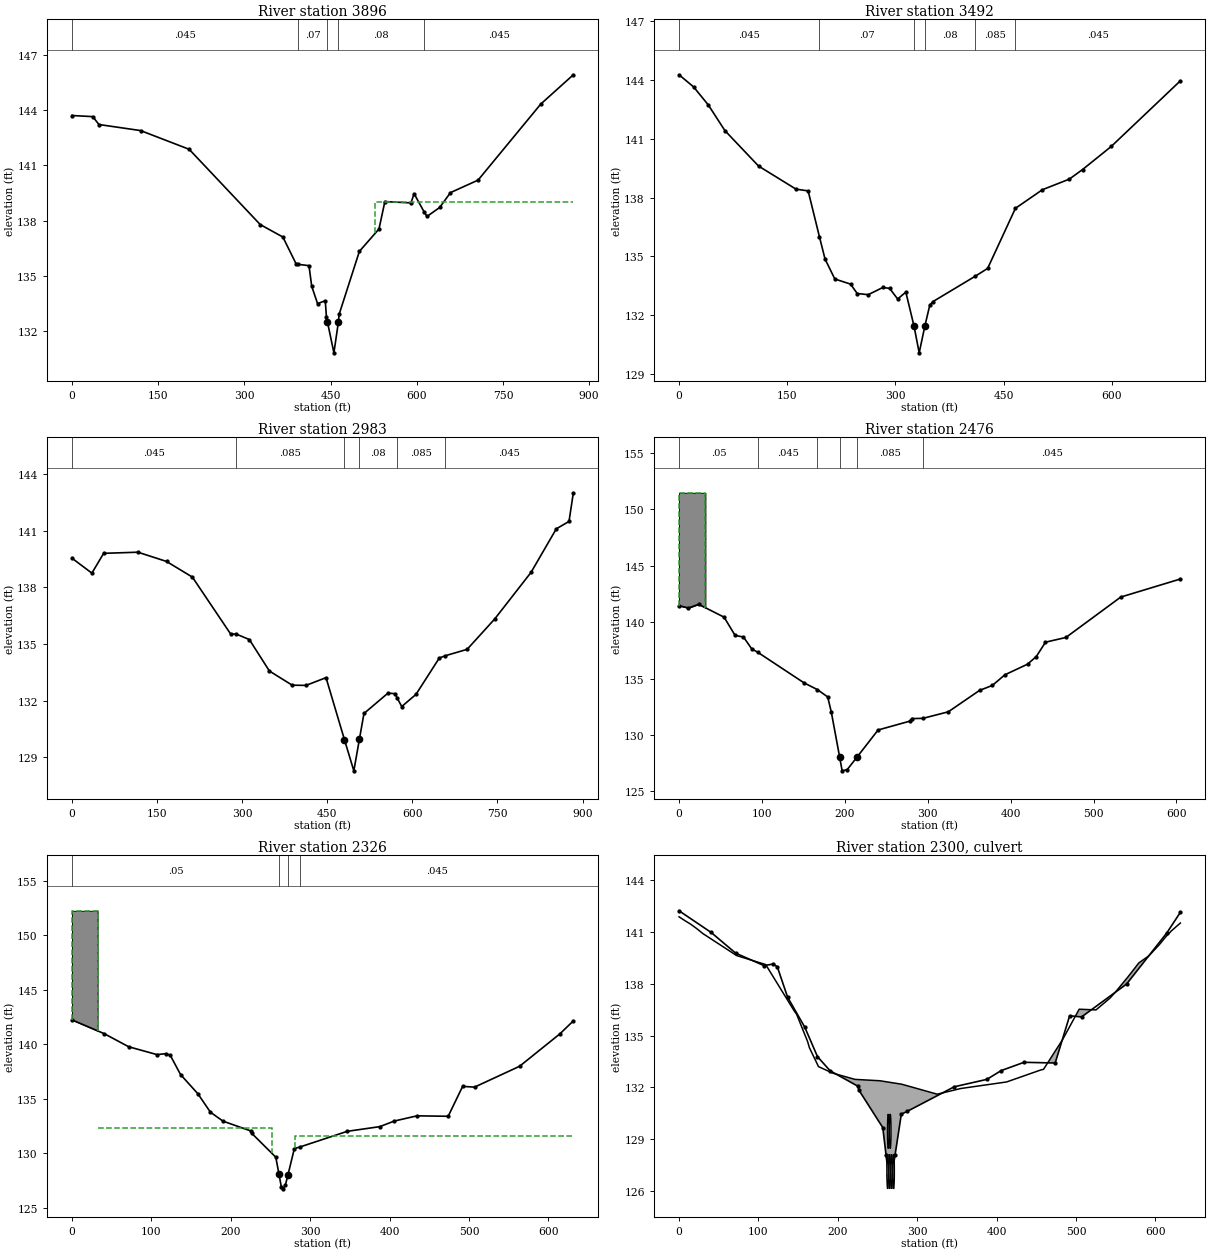
Type RM Length L Ch R = 1 ,3896    ,399.59,404.36,413.44
XS GIS Cut Line= 3
  2301217.710335   735589.680518  2300923.828944   735703.281728
 2300543.5118497   736110.764329
#Sta/Elev= 30
       0  143.72   36.12  143.66   46.75  143.23  119.26   142.9  203.84  141.88
  327.48  137.78  366.93   137.1  390.09  135.63  393.92  135.61  412.39  135.54
   417.1  134.42  427.31  133.47  440.69  133.63  442.82  132.72  444.52  132.47
  455.75  130.79  463.48  132.45  464.77  132.88  500.11  136.32  534.22  137.54
  544.43  139.03  589.86  138.96  595.34  139.46  612.38  138.49  617.74  138.22
  639.85  138.71  658.65  139.52  706.63   140.2  815.94  144.35  872.46  145.94
#Mann= 5 ,-1 , 0
       0    .045       0  393.92     .07       0  444.52     .05       0
  463.48     .08       0  612.38    .045       0
#XS Ineff= 2 , 0
       0                     528       0     139
Permanent Ineff=
       F       F
Bank Sta=444.52,463.48
XS Rating Curve= 0 ,0
Exp/Cntr=0.3,0.1

Type RM Length L Ch R = 1 ,3492    ,510.28,509.35,505.53
XS GIS Cut Line= 2
 2300763.3054951  735315.5558591 2300259.5088247  735794.6566143
#Sta/Elev= 30
       0  144.27   20.19  143.65   40.56  142.73   63.58  141.42  110.23  139.61
  162.14  138.43  179.03  138.34  194.67     136  202.45  134.86  216.04  133.84
  237.86  133.58  247.06   133.1  262.36  133.04  282.74  133.41  292.07  133.36
  303.16  132.82  314.52  133.17  325.84  131.44  333.03  130.07  340.91  131.44
  347.76  132.51  352.28  132.69  411.09  133.99  427.94  134.38   466.5137.4501
  503.89   138.4  541.17  138.94  559.58  139.43  599.39  140.61  695.23  143.96
#Mann= 6 ,-1 , 0
       0    .045       0  194.67     .07       0  325.84     .05       0
  340.91     .08       0  411.09    .085       0   466.5    .045       0
Bank Sta=325.84,340.91
XS Rating Curve= 0 ,0
Exp/Cntr=0.3,0.1

Type RM Length L Ch R = 1 ,2983    ,506.74,506.11,515.51
XS GIS Cut Line= 2
 2300531.1638921  734831.5159209 2299896.4788711  735446.4442098
#Sta/Elev= 30
       0  139.55   34.97  138.76   55.71  139.81  116.09  139.87  166.52  139.38
  212.13  138.55  279.68  135.53  289.42  135.53  312.54  135.24  347.96  133.57
   388.1  132.82  412.53  132.81  447.73  133.22  480.25  129.93  496.75  128.28
  506.55  129.95  514.61  131.32  556.94   132.4  569.86  132.37  573.09  132.14
  581.21  131.69  606.25  132.33  647.42  134.26  657.84  134.38  696.46  134.72
  745.09  136.33  809.13   138.8   853.7  141.11  876.09   141.5  883.72  143.02
#Mann= 6 ,-1 , 0
       0    .045       0  289.42    .085       0  480.25     .05       0
  506.55     .08       0  573.09    .085       0  657.84    .045       0
Bank Sta=480.25,506.55
XS Rating Curve= 0 ,0
Exp/Cntr=0.3,0.1

Type RM Length L Ch R = 1 ,2476    ,125.56,150.05,196.92
XS GIS Cut Line= 4
 2300004.3053852  734730.3492017 2299846.3047714  734800.8802058
 2299800.0939023  734835.8376508 2299502.0088758  735061.3320231
#Sta/Elev= 30
       0  141.46   11.25  141.25   23.55  141.58   54.31  140.44   67.62  138.82
   77.74  138.68   87.65  137.63   95.07  137.32   150.9  134.61  166.85  134.02
  179.33  133.37  183.69  132.02  193.78  128.02  196.74  126.82  202.86  126.93
  214.39  128.01   240.1  130.44  278.66  131.23  280.65  131.45  294.09  131.47
  324.79  132.05  362.53  133.95  377.97  134.39  393.04  135.33  420.37  136.27
  430.98  136.95  442.06  138.22  466.68  138.64  532.85  142.22  604.74  143.82
#Mann= 6 ,-1 , 0
       0     .05       0   95.07    .045       0  166.85    .085       0
  193.78     .05       0  214.39    .085       0  294.09    .045       0
#XS Ineff= 2 , 0
       0   31.83  151.46               0
Permanent Ineff=
       F       F
#Block Obstruct= 1 ,-1
       0   31.83 151.462
Bank Sta=193.78,214.39
XS Rating Curve= 0 ,0
Exp/Cntr=0.5,0.3

Type RM Length L Ch R = 1 ,2326    ,70.46,65.43,58.23
BEGIN DESCRIPTION:
Surveyed Section
END DESCRIPTION:
XS GIS Cut Line= 6
 2299998.1692327  734650.6391228  2299798.574519  734699.3976698
    2299778.0333      734694.917    2299741.0911     734699.2527
    2299677.1594     734714.5897 2299397.4378096  734825.0690048
#Sta/Elev= 30
       0  142.24   40.49  140.98   71.34  139.78  107.02  139.06  118.58  139.15
  123.77  138.99  136.69  137.23  158.43  135.48  174.34  133.78  190.22  132.96
  225.39  132.06 226.329  131.85 256.645  129.66  260.69  128.09 263.612  126.94
 265.698  126.76 268.803  127.13  272.09  128.07 279.968  130.44  287.65  130.61
  346.62  132.03  387.74  132.46  405.78  132.97  434.55  133.45  473.79  133.41
     492  136.15  506.97  136.08  563.71  137.99  614.47  140.96  631.44  142.15
#Mann= 4 ,-1 , 0
       0     .05       0  260.69     .05       0  272.09    .085       0
  287.65    .045       0
#XS Ineff= 3 ,-1
       0   32.17  152.24   32.17  251.75  132.38  281.25     700   131.6
Permanent Ineff=
       F       F       F
#Block Obstruct= 1 ,-1
       0   32.17 152.236
Bank Sta=260.69,272.09
XS Rating Curve= 0 ,0
Exp/Cntr=0.5,0.3

Type RM Length L Ch R = 2 ,2300    ,,,
Node Photo=..\..\..\..\SURVEY\DTL\Surveys\Wilson\Bloomery Swamp Tributary 3\STR_34\STR_34 Photos\STR_34PHT2.JPG
Bridge Culvert--1,0,-1,-1, 0
Deck Dist Width WeirC Skew NumUp NumDn MinLoCord MaxHiCord MaxSubmerge Is_Ogee
21.2,10.1,2.6,0, 36, 36, , , 0.98, 0, 0,0,,
       0    7.61   14.37   22.42   29.93    72.6  109.13  144.52  148.05  161.96
  164.25  175.65 193.675 221.629 252.975 280.403 325.247  354.83  412.56  455.89
  459.05  483.01     504  525.19  542.72  549.77  564.11  567.76  579.23  590.69
  592.71  594.72  605.04  612.85  620.07  631.44
  141.89  141.66  141.47   141.2  140.92  139.64  139.12  136.47  136.24  134.65
  134.29   133.2  132.82  132.46  132.38  132.18   131.6  131.93  132.31  133.01
  133.04  134.76  136.53  136.49  137.17  137.53  138.33  138.54  139.22  139.59
  139.67  139.77  140.28  140.72  141.07  141.53
                                                                                
                                                                                
                                                                                
                                                
       0    7.61   14.37   22.42   29.93    72.6  109.13  144.52  148.05  161.96
  164.25  175.65 193.675 221.629 252.975 280.403 325.247  354.83  412.56  455.89
  459.05  483.01     504  525.19  542.72  549.77  564.11  567.76  579.23  590.69
  592.71  594.72  605.04  612.85  620.07  631.44
  141.89  141.66  141.47   141.2  140.92  139.64  139.12  136.47  136.24  134.65
  134.29   133.2  132.82  132.46  132.38  132.18   131.6  131.93  132.31  133.01
  133.04  134.76  136.53  136.49  137.17  137.53  138.33  138.54  139.22  139.59
  139.67  139.77  140.28  140.72  141.07  141.53
                                                                                
                                                                                
                                                                                
                                                
BR Coef=-1 , 0 , 0 ,, 0 ,,,0.8,-1,,0,
WSPro=,,,, 1 ,,,, 0 ,,,, 0 ,,,,-1 ,-1 ,-1 , 0 , 0 , 0 , 0 , 0
Multiple Barrel Culv=1,2,,21,0.012,0.5,1,1,1,126.11,126.4, 4,Culvert #3  , 0 ,14.9
  262.75  260.75  265.25  263.25  267.75  265.75  270.25  268.25
Culvert Bottom n=0.012
Culvert Bottom Depth=2
Culvert Depth Blocked=1.99
Culvert=1,2,,21,0.012,0.5,1,1,1,128.45,263.5,128.74,261.5,Culvert #1  , 0 ,14.9
Culvert Bottom n=0.012
Culvert Bottom Depth=2
Culvert Depth Blocked=1.5
Culvert=1,2,,21,0.012,0.5,1,1,1,128.45,266,128.74,264,Culvert #2  , 0 ,14.9
Culvert Bottom n=0.012
BC Design=,, 0 ,, 0 ,,,,,,
BC Use User HTab Curves=0
BC User HTab FreeFlow(D)= 0

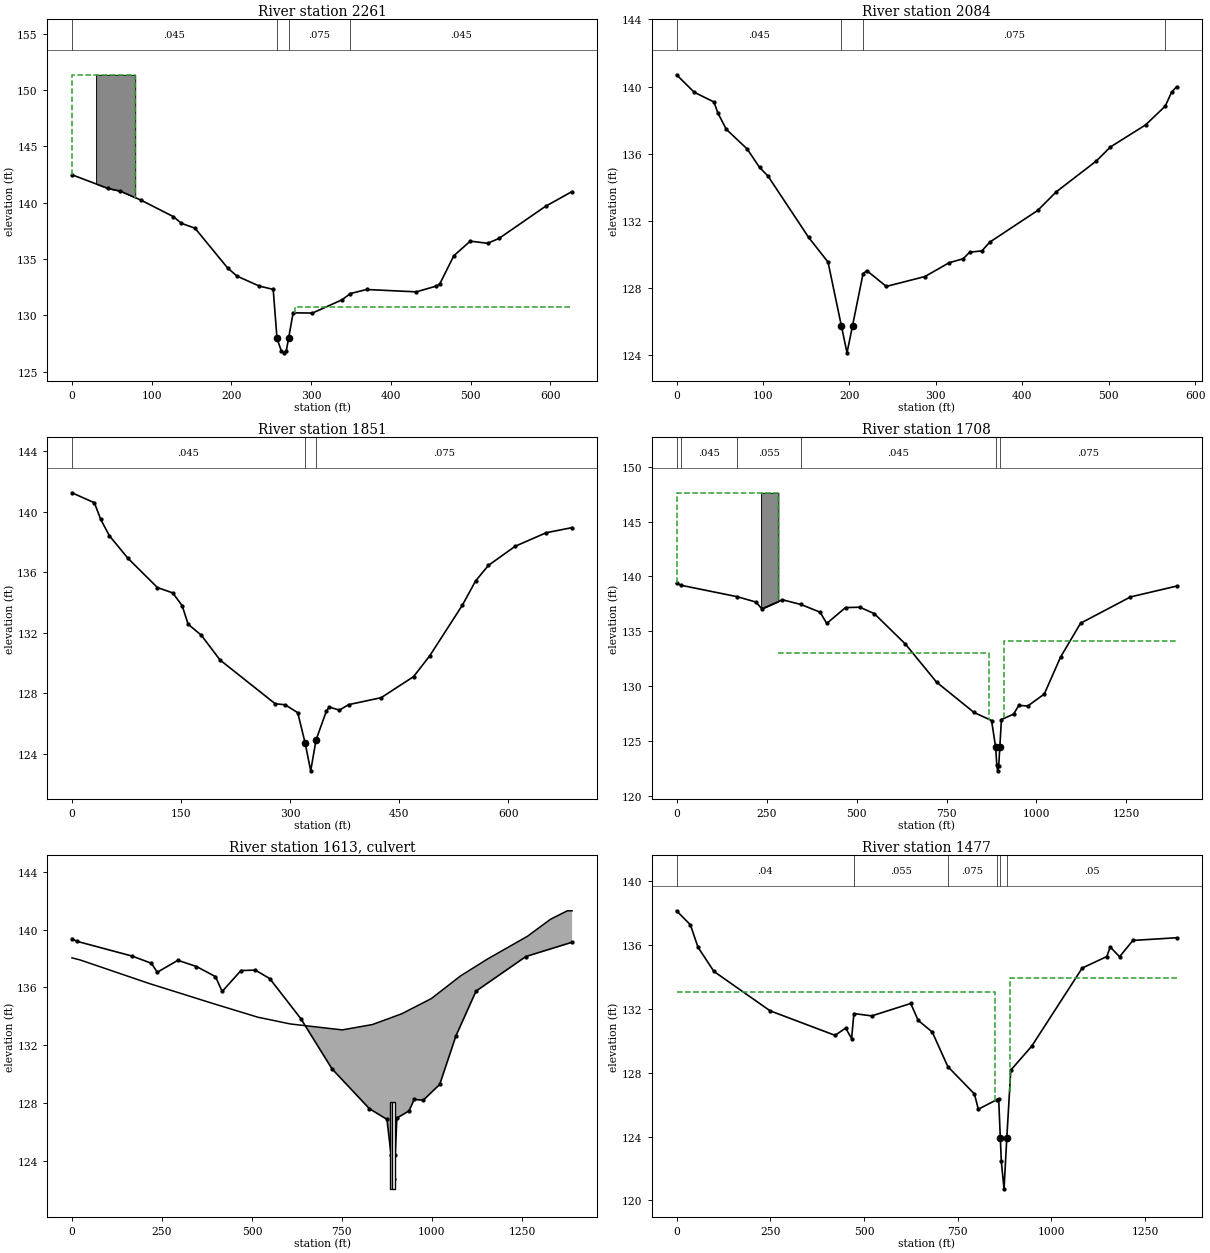
Type RM Length L Ch R = 1 ,2261    ,170.6,177.05,176.14
BEGIN DESCRIPTION:
Surveyed Section
END DESCRIPTION:
XS GIS Cut Line= 6
 2299961.8445074   734578.538426 2299765.4450589  734635.3174136
    2299717.4365     734634.0792    2299703.1458     734654.1132
 2299659.4765283  734658.0442131 2299376.0173797  734773.0820108
#Sta/Elev= 30
       0  142.48   45.01  141.27    60.5  141.03   86.23  140.24   127.3  138.76
  137.28  138.17  154.27  137.74  195.09  134.22  206.92  133.49  235.07   132.6
 252.373  132.31 257.165  127.96 262.405  126.88 265.447  126.68  268.65   126.8
  271.67  127.97 277.371  130.23  301.63  130.21  338.56  131.38  349.24  131.94
  369.64   132.3  431.83  132.09  456.85   132.6   461.3  132.79  478.89  135.29
   499.5  136.59   521.3   136.4  535.59  136.83  593.95  139.68  627.23  140.99
#Mann= 4 ,-1 , 0
       0    .045       0 257.165     .05       0  271.67    .075       0
  349.24    .045       0
#XS Ineff= 3 ,-1
       0   79.33  151.35   79.33  249.75  130.74  279.25     700  130.74
Permanent Ineff=
       F       F       F
#Block Obstruct= 1 ,-1
   30.22   79.33 151.346
Bank Sta=257.165,271.67
XS Rating Curve= 0 ,0
Exp/Cntr=0.5,0.3

Type RM Length L Ch R = 1 ,2084    ,219.37,233.35,248.1
XS GIS Cut Line= 4
  2299814.865779  734469.3190467 2299668.4789635  734484.6927535
 2299506.7596575  734529.5544849 2299263.0678564  734630.1224333
#Sta/Elev= 30
       0   140.7   20.38  139.66   43.24  139.08   47.74  138.43   57.51  137.45
   81.62  136.28      96  135.18  105.78  134.66  152.71  131.01  175.27  129.53
  190.74  125.72  197.23  124.12  203.58  125.73   215.8  128.84  220.19  129.02
  242.69  128.08  287.43  128.67  315.29  129.49  331.59  129.73  339.13  130.12
  353.28   130.2  362.66  130.73  417.86  132.61  439.34  133.72  485.74  135.56
   501.9  136.39  542.67  137.71  565.45  138.83  572.79  139.66  578.65  139.99
#Mann= 4 ,-1 , 0
       0    .045       0  190.74     .05       0   215.8    .075       0
  565.45    .045       0
#XS Ineff= 2 , 0
       0                     340       0
Permanent Ineff=
       F       F
Bank Sta=190.74,203.58
XS Rating Curve= 0 ,0
Exp/Cntr=0.3,0.1

Type RM Length L Ch R = 1 ,1851    ,137.65,142.7,129.08
XS GIS Cut Line= 3
 2299892.2276823  734268.4516211 2299653.9300705  734265.9563582
 2299207.2780023  734313.3663543
#Sta/Elev= 30
       0  141.25   30.82  140.59   39.43   139.5   51.33  138.42   76.81  136.93
  117.52  134.99  138.47  134.64  151.44   133.8  159.67  132.57  177.73  131.85
  203.52  130.21  279.34  127.32  293.12  127.25  310.35  126.73  320.35  124.76
  328.18  122.89  335.52  124.93  349.69  126.83  353.56   127.1  367.66   126.9
   380.2  127.26  425.05  127.72  469.56  129.11  491.89  130.49  536.67  133.83
  554.99  135.44  572.59  136.46  609.34  137.72  651.87  138.61  687.47  138.95
#Mann= 3 , 0 , 0
       0    .045       0  320.35     .05       0  335.52    .075       0
#XS Ineff= 2 , 0
       0     200             450       0
Permanent Ineff=
       F       F
Bank Sta=320.35,335.52
XS Rating Curve= 0 ,0
Exp/Cntr=0.5,0.3

Type RM Length L Ch R = 1 ,1708    ,245.72,230.83,210.96
BEGIN DESCRIPTION:
Surveyed Section
END DESCRIPTION:
XS GIS Cut Line= 6
 2300346.1992795  733766.7514361 2299740.0166423   734095.030846
    2299607.2487     734140.4808     2299500.758     734146.5554
 2299335.7840443  734186.1079438 2299053.8193308  734212.3082047
#Sta/Elev= 30
       0  139.37   13.06  139.19  168.12138.1551  220.73  137.66  236.91  137.04
  294.17  137.87  345.82  137.44  398.64  136.74  417.28  135.71  469.43  137.16
  509.43  137.19  549.56   136.6  635.76  133.83  722.45  130.35  826.34  127.59
 875.146  126.85 886.597  124.39 889.728  122.75  892.16  122.26 895.065  122.73
  898.06   124.4 902.562  126.94 936.466  127.44  950.83  128.23  976.03  128.18
 1021.67  129.27 1066.88  132.64 1122.46  135.73  1261.1  138.13 1389.38  139.12
#Mann= 6 ,-1 , 0
       0     .03       0   13.06    .045       0  168.12    .055       0
  345.82    .045       0 886.597     .05       0  898.06    .075       0
#XS Ineff= 3 ,-1
       0  282.89  147.63  282.89     869  133.05     911    1400  134.07
Permanent Ineff=
       F       F       F
#Block Obstruct= 1 ,-1
  234.81  282.89 147.635
Bank Sta=886.597,898.06
XS Rating Curve= 0 ,0
Exp/Cntr=0.5,0.3

Type RM Length L Ch R = 2 ,1613    ,,,
BEGIN DESCRIPTION:
Raleigh Road (264 Bus.)
END DESCRIPTION:
Bridge Culvert--1,0,-1,-1, 0
Deck Dist Width WeirC Skew NumUp NumDn MinLoCord MaxHiCord MaxSubmerge Is_Ogee
75.8,101.5,2.6,0, 18, 17, , , 0.98, 0, 1,1,,
       0    23.1  214.89  393.83  516.02  606.71 750.955 834.479 875.301 916.401
 998.446 1079.57 1154.54 1265.78 1329.29 1376.31 1387.36 1389.38
  138.04  137.89  136.26  134.86  133.93  133.46  133.05  133.42  133.79  134.17
  135.22  136.79  137.96  139.54  140.71   141.3   141.3   141.3
                                                                                
                                                                
       0    23.1  214.89  393.83  516.02  606.71 750.955 834.479 875.301 916.401
 998.446 1079.57 1154.54 1265.78 1329.29 1376.31 1387.36
  138.04  137.89  136.26  134.86  133.93  133.46  133.05  133.42  133.79  134.17
  135.22  136.79  137.96  139.54  140.71   141.3   141.3
                                                                                
                                                        
BR Coef=-1 , 0 , 0 ,, 0 ,,,0.8,-1,,0,
WSPro=,,,, 1 ,,,, 0 ,,,, 0 ,,,,-1 ,-1 ,-1 , 0 , 0 , 0 , 0 , 0
Multiple Barrel Culv=2,6,6,142.7,0.011,0.4,1,8,1,122.04,120.63, 2,Culvert #1  , 0 ,47
  886.75  868.75  893.25  875.25
Culvert Bottom n=0.011
BC Design=,, 0 ,, 0 ,,,,,,
BC Use User HTab Curves=0
BC User HTab FreeFlow(D)= 0

Type RM Length L Ch R = 1 ,1477    ,161.1,193.44,201.43
BEGIN DESCRIPTION:
Surveyed Section
END DESCRIPTION:
XS GIS Cut Line= 6
 2300297.7079119  733527.3585247 2299758.7311145    733819.30429
 2299663.9111223  733862.9713916    2299449.2396     733943.9731
 2299322.0600981  733974.0105929 2299067.5432771  733998.9632224
#Sta/Elev= 30
       0  138.15   36.93  137.27   57.24  135.86   99.59  134.35  249.46  131.88
  423.06  130.34  451.05   130.8  467.01  130.14   473.1  131.71   520.6  131.56
  624.68  132.34  644.66  131.28  682.16  130.55  723.79  128.38  794.63  126.67
  805.09  125.71  853.61 126.301 859.316  126.37  863.78  123.91 866.361  122.44
 873.671  120.72 881.029   123.9 891.672  128.16 947.434  129.66 1082.22  134.56
 1147.78  135.28 1156.92  135.88 1181.92  135.27 1217.44  136.29 1334.18  136.46
#Mann= 6 ,-1 , 0
       0     .04       0   473.1    .055       0  723.79    .075       0
  853.61    .085       0  863.78     .05       0 881.029     .05       0
#XS Ineff= 2 ,-1
       0     850  133.05  888.25    1400  133.91
Permanent Ineff=
       F       F
Bank Sta=863.78,881.029
XS Rating Curve= 0 ,0
Exp/Cntr=0.5,0.3

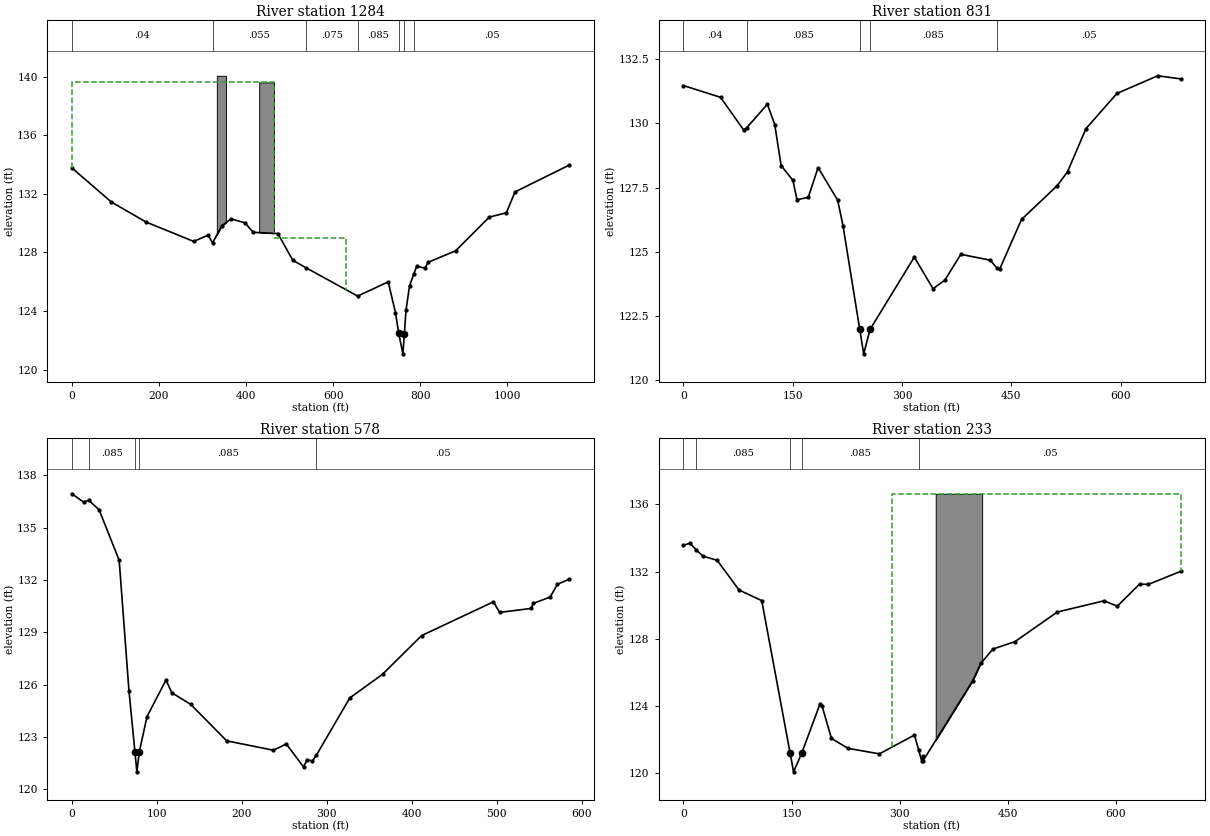
Type RM Length L Ch R = 1 ,1284    ,323.12,452.16,364.1
XS GIS Cut Line= 4
 2300121.7918739  733468.8757993 2299604.0248115  733726.1997911
 2299323.3077295  733765.1882747 2299069.1028164  733882.1537256
#Sta/Elev= 30
       0  133.77   90.68  131.44  170.58  130.07  279.75  128.75  312.93  129.18
  323.02  128.65  344.23  129.81  365.66  130.29  397.12  130.02  416.67  129.37
  472.87  129.29  507.35  127.46  537.72  126.95   656.2  125.02  726.25  125.99
  742.93   123.9  750.37  122.49  760.02  121.08   763.4  122.46  767.16  124.05
  775.22  125.72  785.18  126.54  791.73  127.05  811.26  126.93  817.63  127.32
  881.03  128.11  958.36  130.41   997.4   130.7 1017.48  132.13 1141.42  133.95
#Mann= 7 ,-1 , 0
       0     .04       0  323.02    .055       0  537.72    .075       0
   656.2    .085       0  750.37     .05       0   763.4    .085       0
  785.18     .05       0
#XS Ineff= 2 ,-1
       0  464.04   139.6  464.04     630     129
Permanent Ineff=
       F       F
#Block Obstruct= 2 ,-1
  332.86  353.77 140.052  430.04  464.04 139.599
Bank Sta=750.37,763.4
XS Rating Curve= 0 ,0
Exp/Cntr=0.3,0.1

Type RM Length L Ch R = 1 ,831     ,259.2,253.54,183.08
XS GIS Cut Line= 3
 2299866.0274213  733375.3034386 2299658.6086886  733411.1728435
 2299187.6278065   733386.220214
#Sta/Elev= 30
       0  131.48   51.03  131.02   82.88  129.74   87.11  129.84  115.28  130.75
  125.35  129.96  134.14  128.36  150.32  127.78  155.86  127.03  171.33  127.12
  184.85  128.28   211.7  127.01  218.99  126.02  241.99  121.97  247.41  121.02
  256.11  121.97   316.8  124.79  342.54  123.56  358.66  123.89  380.67   124.9
  421.14  124.67  430.02  124.37  433.92  124.32  463.96  126.26  513.06  127.58
  527.08  128.12  552.37   129.8  594.85  131.17  650.75  131.86  682.14  131.74
#Mann= 5 ,-1 , 0
       0     .04       0   87.11    .085       0  241.99     .05       0
  256.11    .085       0  430.02     .05       0
#XS Ineff= 2 , 0
       0  184.85  128.28     342       0
Permanent Ineff=
       F       F
Bank Sta=241.99,256.11
XS Rating Curve= 0 ,0
Exp/Cntr=0.3,0.1

Type RM Length L Ch R = 1 ,578     ,339.27,344.68,257.07
XS GIS Cut Line= 2
 2299716.3116443  733133.5748403 2299162.6751771  733323.8386403
#Sta/Elev= 30
       0  136.95   13.84  136.47   19.79  136.58   32.12  136.03   55.73  133.13
   67.25  125.63   74.26  122.14   76.52  120.99   79.41  122.14   88.46  124.16
  110.83  126.26  117.66  125.53  139.94  124.86  182.23  122.77  237.29  122.23
  252.39  122.59  272.75  121.27  276.82  121.69  283.01  121.61  287.62  121.93
   327.1  125.23  365.65  126.59  411.66  128.81  496.24  130.75  503.38  130.14
  540.62  130.37  543.06  130.66  562.89  131.02  571.56  131.76  585.16  132.04
#Mann= 5 ,-1 , 0
       0     .04       0   19.79    .085       0   74.26     .05       0
   79.41    .085       0  287.62     .05       0
#XS Ineff= 2 , 0
       0                     220       0
Permanent Ineff=
       F       F
Bank Sta=74.26,79.41
XS Rating Curve= 0 ,0
Exp/Cntr=0.3,0.1

Type RM Length L Ch R = 1 ,233     ,158.26,175.14,106.72
XS GIS Cut Line= 4
 2299608.7034296  732801.3929599 2299507.3333722  732851.2982189
 2299348.4070689  733003.4683942  2299148.639323  733298.8860108
#Sta/Elev= 30
       0  133.56    8.96  133.69   17.93  133.29      27  132.92   46.84  132.67
   77.32   130.9  108.69  130.27     148  121.21   152.8  120.08  164.13  121.19
  189.38  124.11  192.47  123.98  205.38  122.07  228.19  121.48  271.85  121.15
  320.51  122.27  326.34  121.38  330.42  120.75   331.9  121.02  332.56  120.75
   401.4  125.51  412.42  126.53  429.35  127.39  459.89  127.83  518.54  129.59
  583.45  130.26  601.79  129.94  632.63  131.25  645.03  131.24  689.54  132.01
#Mann= 5 ,-1 , 0
       0     .04       0   17.93    .085       0     148     .05       0
  164.13    .085       0  326.34     .05       0
#XS Ineff= 1 ,-1
     290     700  136.63
Permanent Ineff=
       F
#Block Obstruct= 1 ,-1
  349.97  414.37 136.628
Bank Sta=148,164.13
XS Rating Curve= 0 ,0
Exp/Cntr=0.3,0.1