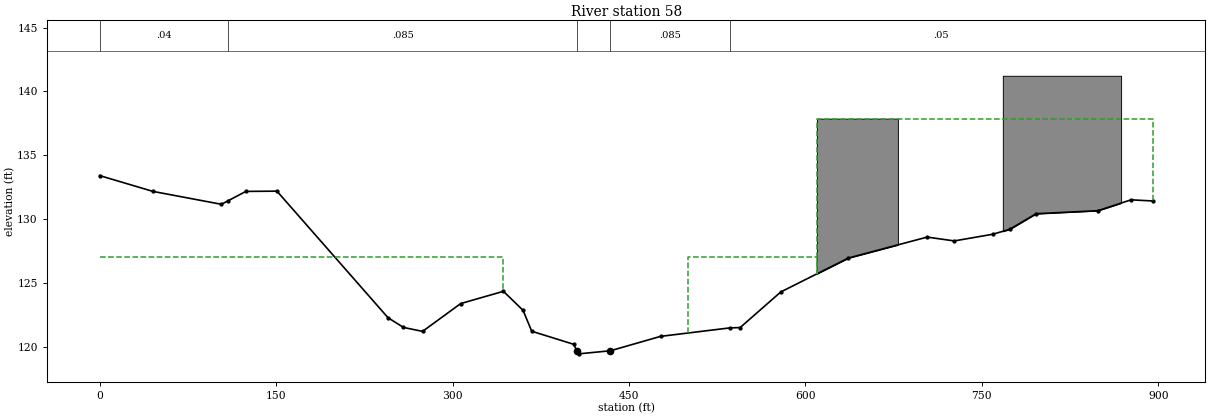
HEC-RAS study DTL_Bloomery_Swp_T3.prj: DTL_Bloomery_Swp_T3

--- DTL_Bloomery_Swp_T3.g01 (geometry) --- (continued)

Type RM Length L Ch R = 1 ,58      ,88.64,58.03,101.93
XS GIS Cut Line= 4
 2299652.3705312  732628.2840927 2299356.0580558  732787.3571058
 2299225.0567509  733002.5735353 2299082.4612815  733274.3961487
#Sta/Elev= 30
       0   133.4   45.33  132.16  103.51  131.15  109.49  131.44  124.32  132.16
  150.73  132.18  245.15  122.26  258.28   121.5   274.5  121.19  306.93  123.37
  343.25  124.33  359.93  122.84  367.32   121.2  402.89  120.18  405.65  119.68
  407.28  119.43  434.15  119.67  476.88   120.8  535.43  121.46  544.48  121.49
  579.02  124.28  636.53  126.94  703.44  128.58  726.45  128.28  759.12   128.8
  773.64  129.19  795.96  130.41  848.64  130.65  876.75   131.5  895.22  131.41
#Mann= 5 ,-1 , 0
       0     .04       0  109.49    .085       0  405.65     .05       0
  434.15    .085       0  535.43     .05       0
#XS Ineff= 3 ,-1
       0  343.26     127     500  609.74     127  609.74    1000  137.86
Permanent Ineff=
       F       F       F
#Block Obstruct= 2 ,-1
  609.74  678.56 137.862  767.77  868.31 141.222
Bank Sta=405.65,434.15
XS Rating Curve= 0 ,0
Exp/Cntr=0.3,0.1

Chan Stop Cuts=-1
Use User Specified Reach Order=0
User Specified Reach Order=Bloomery Swamp  ,Trib 3