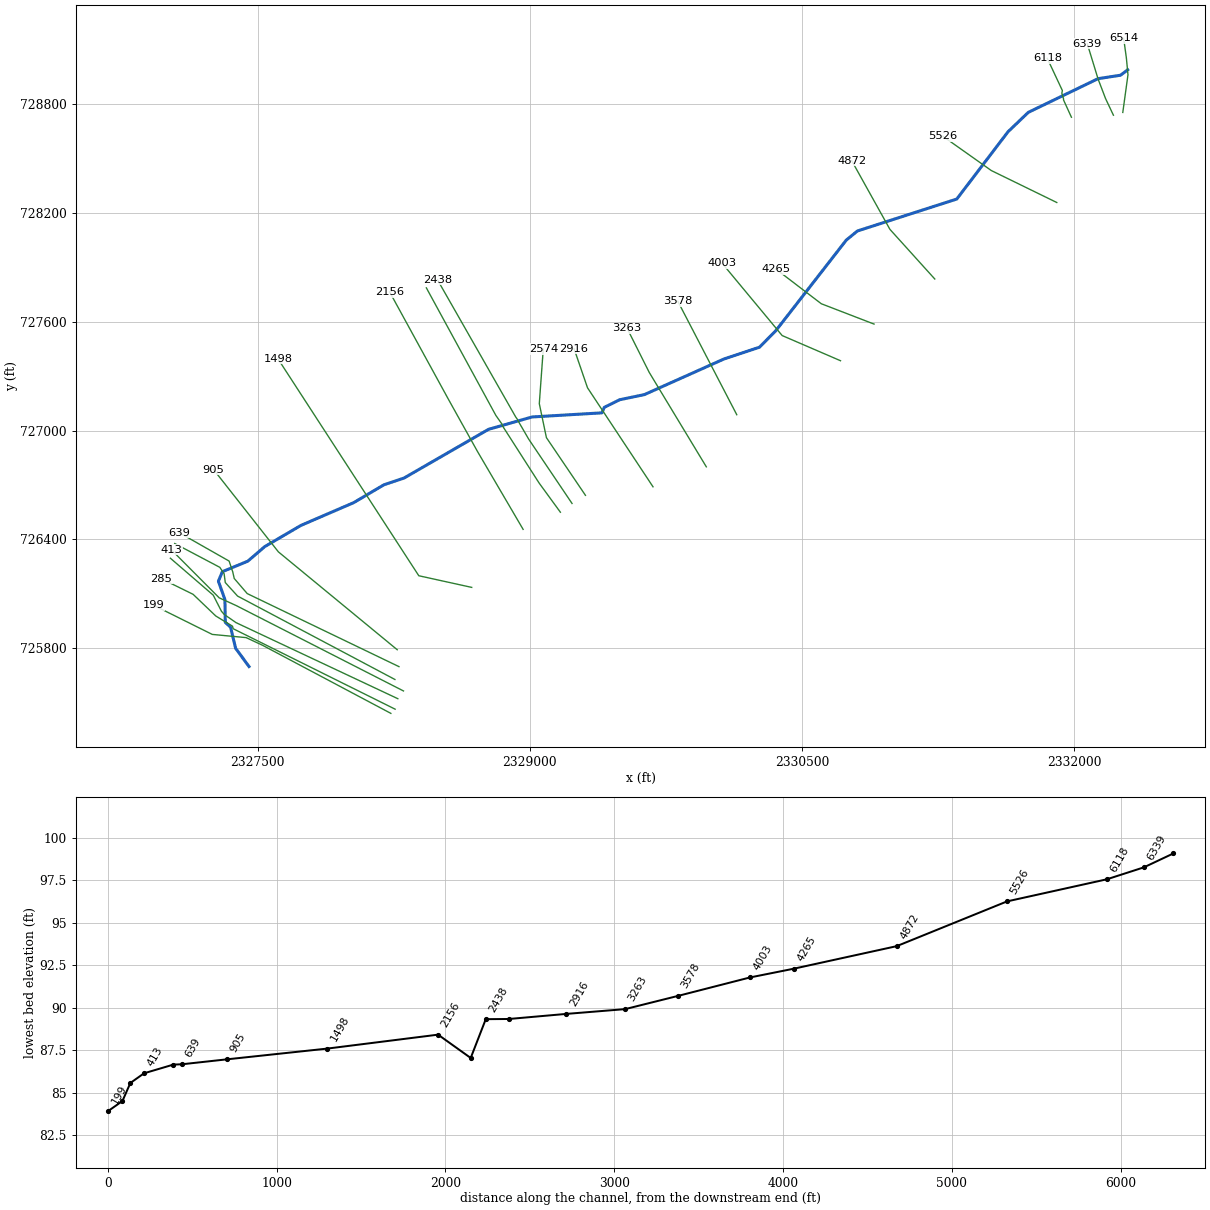
--- DTL_Hog_Island_Trib.prj (project) ---

Proj Title=DTL_Hog_Island_Trib
Current Plan=p02
Default Exp/Contr=0.3,0.1
English Units
Geom File=g01
Flow File=f01
Flow File=f02
Plan File=p01
Plan File=p02
Y Axis Title=Elevation
X Axis Title(PF)=Main Channel Distance
X Axis Title(XS)=Station
BEGIN DESCRIPTION:
END DESCRIPTION:
DSS File=dss
DSS Export Rating Curves= 0
DSS Export Rating Curve Sorted= 0
DSS Export Volume Flow Curves= 0
DXF Filename=DTL_Hod_Island_Trib.
DXF OffsetX= 0
DXF OffsetY= 0
DXF ScaleX= 1
DXF ScaleY= 10

--- DTL_Hog_Island_Trib.p02 (plan) ---

Plan Title=DTL_Hog_Island_Trib_Future
Program Version=4.00
Short Identifier=Future
Geom File=g01
Flow File=f02
Subcritical Flow
K Sum by GR= 0
Std Step Tol= 0.01
Critical Tol= 0.01
Num of Std Step Trials= 20
Max Error Tol= 0.3
Flow Tol Ratio= 0.001
Split Flow NTrial= 30
Split Flow Tol= 0.02
Split Flow Ratio= 0.02
Log Output Level= 0
Friction Slope Method= 1
Unsteady Friction Slope Method= 2
Unsteady Bridges Friction Slope Method= 1
Parabolic Critical Depth
Global Vel Dist= 0 , 0 , 0
Global Log Level= 0
CheckData=True
Encroach Param=-1 ,10,10, 6
Encroach River=Hogs Island
Encroach Reach=Trib
Encroach Node=6118
       0                       0       0       0       0       0       0
       0       0       0       4       1
Encroach Node=4872
       0                       0       0       0       0       0       0
       0       0       0       4       1
Encroach Node=4265
       0                       0       0       0       0       0       0
       0       0       0       4       1
Encroach Node=2438
       0                       0       0       0       0       0       0
       0       0       0       4       1
Encroach Node=2349
       0                       0       0       0       0       0       0
       0       0       0       4       1
Encroach Node=2156
       0                       0       0       0       0       0       0
       0       0       0       4       1
Encroach Node=639
       0                       0       0       0       0       0       0
       0       0       0       4       1
Encroach Node=587
       0                       0       0       0       0       0       0
       0       0       0       4       1
Encroach Node=332
       0                       0       0       0       0       0       0
       0       0       0       4       1
Encroach Node=285
       0                       0       0       0       0       0       0
       0       0       0       4       1
Computation Interval=1HOUR
Output Interval=1HOUR
Run HTab= 0
Run UNet= 0
Run PostProcess= 0
Run WQNet= 0
UNET Theta= 1
UNET Theta Warmup= 1
UNET ZTol= 0.02
UNET ZSATol= 0.05
UNET MxIter= 20
UNET MaxInSteps= 0
UNET DtIC= 0
UNET DtMin= 0
UNET MaxCRTS= 20
UNET WFStab= 2
UNET SFStab= 1
UNET WFX= 1
UNET SFX= 1
UNET DSS MLevel= 4
UNET DZMax Abort= 100
UNET Convert EG Bridges= 0
UNET Use Existing IB Tables=-1
UNET Froude Reduction=False
UNET Froude Limit= 1
UNET Froude Power= 10
UNET Time Slicing=0,0, 5
Instantaneous Interval=1HOUR
Write IC File= 0
Echo Input=False
Echo Output=False
Write Detailed= 0
Detailed Automatic Start=False, 10
WQ ULTIMATE=-1
WQ Max Comp Step=1HOUR
WQ Output Interval=15MIN
WQ Output Selected Increments= 0
WQ Output face flow=0
WQ Output face velocity=0
WQ Output face area=0
WQ Output face dispersion=0
WQ Output cell volume=0
WQ Output cell surface area=0
WQ Output cell continuity=0
WQ Output face conc=0
WQ Output face dconc_dx=0
WQ Output face courant=0
WQ Output face peclet=0
WQ Output face adv mass=0
WQ Output face disp mass=0
WQ Output cell mass=0
WQ Output cell source sink temp=0
WQ Output cell source sink nsm=0
WQ Output MaxMinRange=-1
WQ Daily Max Min Mean=-1
WQ Daily Range=0
WQ Daily Time=0
WQ Create Restart=0
WQ Fixed Restart=0
WQ System Summary=False
Sorting and Armoring Iterations= 10
XS Update Threshold= 0.02
Hydraulics Update Threshold= 0.02
Energy Slope Method= 1
Volume Change Method= 0
XS Weighting Method= 0
Number of US Weighted Cross Sections= 1
Number of DS Weighted Cross Sections= 1
Upstream XS Weight=0.25
Main XS Weight=0.5
Downstream XS Weight=0.25
Number of DS XS's Weighted with US Boundary= 1
Upstream Boundary Weight= 1
Weight of XSs Associated with US Boundary= 0
Number of US XS's Weighted with DS Boundary= 1
Downstream Boundary Weight= 0.5
Weight of XSs Associated with DS Boundary= 0.5
Sediment Output Level= 4
Mass or Volume Output= 0
Output Increment Type= 1
Profile and TS Output Increment= 10
XS Output Flag= 0
XS Output Increment= 10
Disregard all LS=0
Disregard all Conn=0
Disregard all Breaches=0
Disregard all Pumps=0

--- DTL_Hog_Island_Trib.p01 (plan) ---

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Plan Title=DTL_Hog_Island_Trib
Short Identifier=DTL_Hog_Isla
Geom File=g01
Flow File=f01
Encroach Param=-1 ,10,10, 2
Encroach Node=6514
       1     217     265
Encroach Node=6339
       1     165     245
       1      90     175
Encroach Node=5526
       1     413     500
       1     390     477
       1     380     470
Encroach Node=4003
       1     350     470
Encroach Node=3578
       1     270     390
Encroach Node=3263
       1     460     580
Encroach Node=2916
       1     455     575
Encroach Node=2574
       1     475     620
       1     535     730
       1     554     730
       1     500     640
Encroach Node=1498
       1     700     910
Encroach Node=905
       1     820    1050
       1    1017    1200
       1    1060    1190
Encroach Node=413
       1    1050    1165
       1     986    1088
       1    1000    1103
Encroach Node=199
       1     955    1050
DSS File=dss

--- DTL_Hog_Island_Trib.f02 (steady flow) ---

Flow Title=DTL_Hog_Island_Trib_Future
Program Version=4.00
Number of Profiles= 3
Profile Names=100-yr-10%,100-yr-20%,100-yr-35%
River Rch & RM=Hogs Island,Trib            ,6514
    1380    1770    2170
River Rch & RM=Hogs Island,Trib            ,1498
    1400    1800    2200
Boundary for River Rch & Prof#=Hogs Island,Trib            , 1
Up Type= 0
Dn Type= 3
Dn Slope=0.0016
Boundary for River Rch & Prof#=Hogs Island,Trib            , 2
Up Type= 0
Dn Type= 3
Dn Slope=0.0016
Boundary for River Rch & Prof#=Hogs Island,Trib            , 3
Up Type= 0
Dn Type= 3
Dn Slope=0.0016
DSS Import GetInterval= 0
DSS Import GetPeak= 0
DSS Import FillOption= 0

--- DTL_Hog_Island_Trib.f01 (steady flow) ---

Flow Title=DTL_Hog_Island_Trib
Program Version=4.00
Number of Profiles= 6
Profile Names=100-yr,FW,10-yr,25-yr,50-yr,500-yr
River Rch & RM=Hogs Island,Trib            ,6514
    1480    1480     710    1060    1270    2110
River Rch & RM=Hogs Island,Trib            ,1498
    1500    1500     720    1070    1280    2140
Boundary for River Rch & Prof#=Hogs Island,Trib            , 1
Up Type= 0
Dn Type= 3
Dn Slope=0.0016
Boundary for River Rch & Prof#=Hogs Island,Trib            , 2
Up Type= 0
Dn Type= 3
Dn Slope=0.0016
Boundary for River Rch & Prof#=Hogs Island,Trib            , 3
Up Type= 0
Dn Type= 3
Dn Slope=0.0016
Boundary for River Rch & Prof#=Hogs Island,Trib            , 4
Up Type= 0
Dn Type= 3
Dn Slope=0.0016
Boundary for River Rch & Prof#=Hogs Island,Trib            , 5
Up Type= 0
Dn Type= 3
Dn Slope=0.0016
Boundary for River Rch & Prof#=Hogs Island,Trib            , 6
Up Type= 0
Dn Type= 3
Dn Slope=0.0016
DSS Import GetInterval= 0
DSS Import GetPeak= 0
DSS Import FillOption= 0

--- DTL_Hog_Island_Trib.g01 (geometry) ---

Geom Title=DTL_Hog_Island_Trib
Program Version=4.00

River Reach=Hogs Island     ,Trib
Reach XY= 30
2332296.44256401728988.8652753832332256.79296494728959.056418419
2332133.25818443728940.1392583852331748.42904186728754.313127518
2331636.46780491728647.2197704322331354.13077354728276.449588776
2330806.49429035728100.3946008682330744.83448029728050.093175888
2330356.21540356727550.3241777422330266.15962696727459.457087517
2330070.63311958727394.5520229342329631.71261978727198.214201927
 2329495.4119854727169.8182353972329410.22408676727127.629944801
2329398.05438614727097.6113510132329012.68056583727074.894577026
2328772.53182316727006.744260788 2328306.8379879726738.199556351
2328195.68806267726700.8791437152328029.36883354726602.710232735
2327738.10735703726476.9566707612327538.52428341726360.127552986
2327445.22325325726279.8075370792327304.85976887726221.805599213
2327283.13044357726169.3586835862327319.12765503726067.911996841
2327321.04113007725942.4666261672327350.21615601725915.741962433
 2327378.0321846725799.5691442492327451.85539913725698.864878654

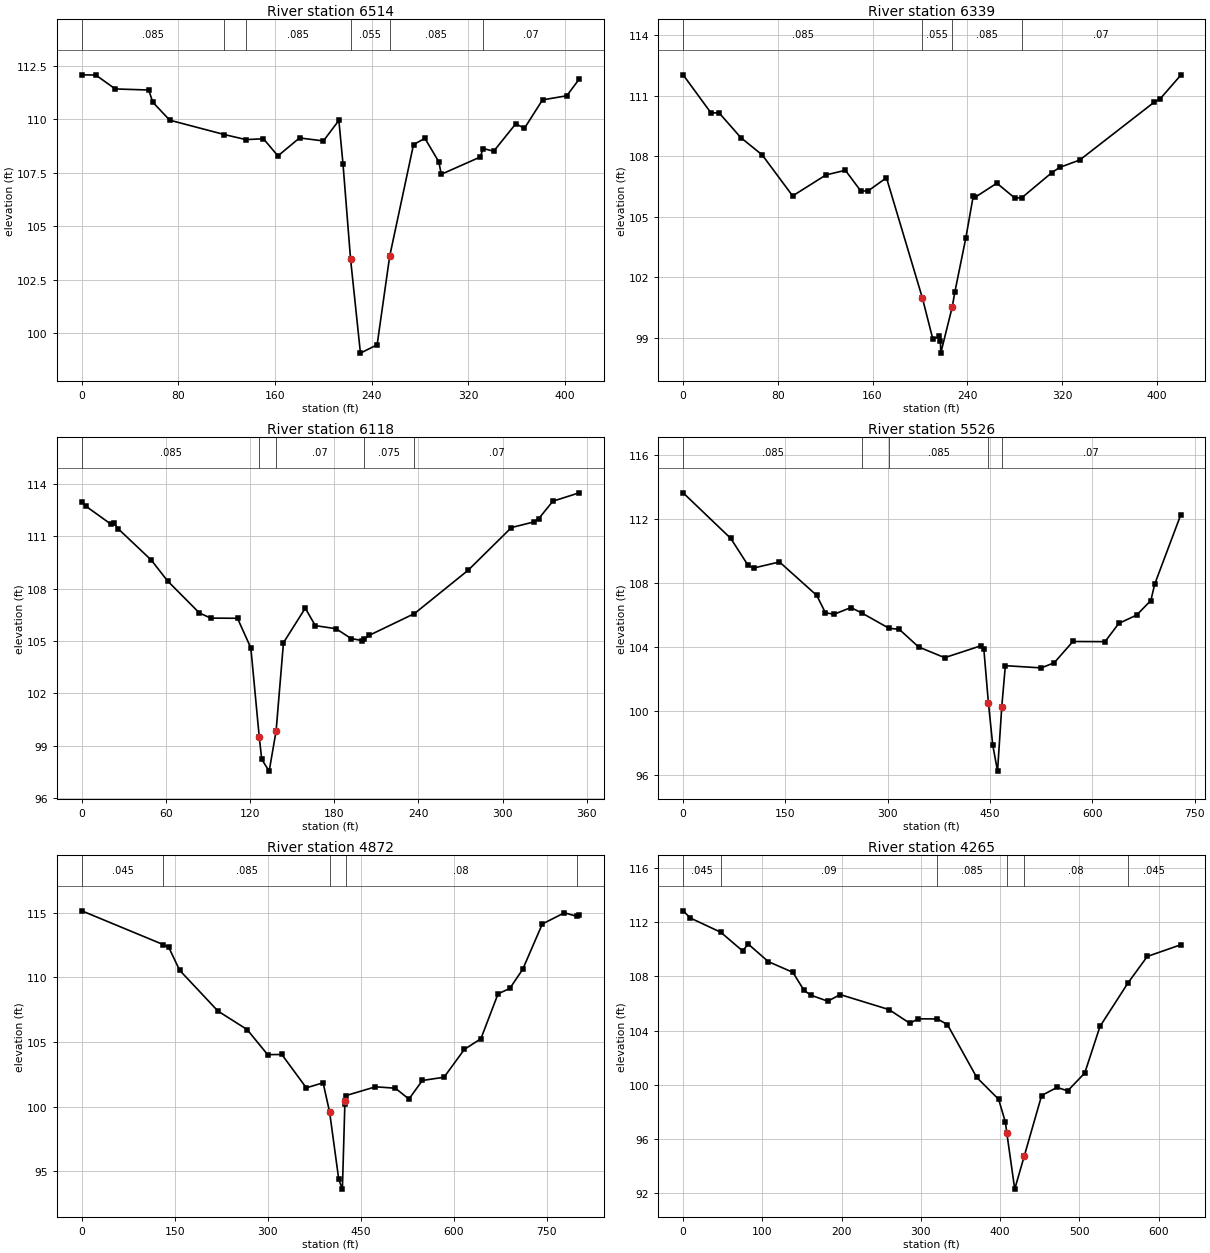
Type RM Length L Ch R = 1 ,6514    ,153.26,175.43,182.12
XS GIS Cut Line= 4
2332269.43662071728753.8716249472332297.94334793728961.337254524
2332289.23295975729053.9841194152332274.18774128729162.468054771
#Sta/Elev= 30
       0  112.08   11.57  112.07   27.75  111.42   55.45  111.37    58.8   110.8
   72.82  109.96  117.95  109.29  135.91109.0522  150.45  109.09  162.47  108.29
  180.35  109.13  200.14  108.99  212.92  109.95  216.34  107.92  222.64  103.45
  230.79   99.07  244.62   99.46  255.02   103.6  274.76  108.82  284.19  109.11
  295.75  108.01  297.72  107.43  330.13  108.24  332.31108.6359   341.2  108.51
  359.43  109.79  366.64  109.58  381.61  110.91  401.69   111.1  411.99  111.88
#Mann= 6 ,-1 , 0
       0    .085       0  117.95    .045       0  135.91    .085       0
  222.64    .055       0  255.02    .085       0  332.31     .07       0
#XS Ineff= 2 , 0
       0     205             265       0
Permanent Ineff=
       F       F
Bank Sta=222.64,255.02
XS Rating Curve= 0 ,0
Exp/Cntr=0.3,0.1

Type RM Length L Ch R = 1 ,6339    ,218.8,218.8,215.5
XS GIS Cut Line= 6
2332217.74446583728738.6592817312332174.45139885728830.213475227
2332137.35645008728927.3866081242332136.14126205728930.463655472
2332134.01009083728935.6568984992332073.67081356729132.555230141
#Sta/Elev= 30
       0  112.04   23.32  110.17   30.61  110.14   48.71  108.93   66.81  108.07
    92.5  106.04  120.66  107.08  137.02  107.31  149.98  106.29  156.07  106.28
  171.75  106.94   202.1  100.98  210.98   98.93  216.23   99.08  217.34   98.86
  217.62   98.25  227.31  100.54  229.52  101.28  238.76  103.95  245.03  106.03
  246.85  105.98  264.98  106.67  280.29  105.93  286.08  105.95  311.57   107.2
  317.99  107.45  335.03  107.82  398.01  110.69  402.62  110.83  420.15  112.01
#Mann= 4 ,-1 , 0
       0    .085       0   202.1    .055       0  227.31    .085       0
  286.08     .07       0
#XS Ineff= 2 , 0
       0     150                       0
Permanent Ineff=
       F       F
Bank Sta=202.1,227.31
XS Rating Curve= 0 ,0
Exp/Cntr=0.3,0.1

Type RM Length L Ch R = 1 ,6118    ,561.45,591.79,642.98
BEGIN DESCRIPTION:
Survyed Section
END DESCRIPTION:
XS GIS Cut Line= 6
 2331986.1897049728727.4424514772331942.58400059728822.988800049
 2331942.8593998728828.8024005892331933.48880005728859.620401382
2331936.15709972728874.8952007292331853.19841576729051.887890816
#Sta/Elev= 30
       0  112.99    2.81  112.74   21.03  111.69   22.73  111.77   26.06  111.43
   49.48  109.65   61.16  108.45   83.89  106.61  91.939  106.32 110.991  106.31
   120.5  104.61  126.52   99.48  128.28   98.22  133.57   97.55   138.5   99.85
 143.758  104.91 159.284  106.89  166.45  105.89  181.29  105.71  191.93  105.15
  199.95  105.03  201.28  105.11  205.07  105.34  237.13  106.58  275.34  109.06
  306.25  111.51  322.14  111.83  325.69  112.02  335.78  113.02  354.55   113.5
#Mann= 5 ,-1 , 0
       0    .085       0  126.52    .055       0   138.5     .07       0
  201.28    .075       0  237.13     .07       0
Bank Sta=126.52,138.5
XS Rating Curve= 0 ,0
Exp/Cntr=0.3,0.1

Type RM Length L Ch R = 1 ,5526    ,675.25,653.82,619.53
XS GIS Cut Line= 3
2331905.39664745728257.3595895772331544.49388313728433.557495117
2331277.00738525728622.816809654
#Sta/Elev= 30
       0  113.64   69.87  110.79   95.21  109.11  103.25  108.94  141.27  109.32
  195.92  107.23  208.52  106.15   221.2  106.05  245.98  106.47  262.54  106.12
  302.07  105.17  316.63  105.12  345.23  104.01  383.44  103.34  437.12  104.09
  440.92  103.86  447.58  100.52  453.92   97.89  460.97   96.25  467.18  100.27
  472.42  102.84     525   102.7  544.06  103.02  571.44  104.35  618.55  104.34
  638.77  105.48  664.86     106  685.75  106.91  691.38  107.93  729.29  112.23
#Mann= 5 ,-1 , 0
       0    .085       0  262.54    .045       0  302.07    .085       0
  447.58    .055       0  467.18     .07       0
Bank Sta=447.58,467.18
XS Rating Curve= 0 ,0
Exp/Cntr=0.3,0.1

Type RM Length L Ch R = 1 ,4872    ,586.19,607.57,643.67
XS GIS Cut Line= 3
2331232.84687901727835.4980602262330985.54804325728109.293201447
2330774.83933735728487.811831474
#Sta/Elev= 30
       0  115.16  131.71  112.54  140.09  112.35   157.8  110.56  219.63   107.4
  266.65  105.97  299.69  104.03   322.6  104.04   362.1  101.46  389.16  101.85
  399.63   99.59   414.4   94.37  420.26   93.62  424.24   100.2  424.66  100.44
  425.39  100.85  473.61  101.54  505.74  101.43  527.53  100.59  549.23  102.03
  584.19  102.28  617.06  104.44  643.62  105.26  671.33  108.74  690.19  109.15
  711.03  110.63  742.64  114.14  778.41  115.01  798.55  114.73  802.16  114.83
#Mann= 5 ,-1 , 0
       0    .045       0  131.71    .085       0  399.63    .055       0
  425.39     .08       0  798.55    .045       0
Bank Sta=399.63,424.66
XS Rating Curve= 0 ,0
Exp/Cntr=0.3,0.1

Type RM Length L Ch R = 1 ,4265    ,265.81,262.04,248.91
XS GIS Cut Line= 3
 2330897.9754343 727587.057194712330607.02941227727699.231354713
2330355.94538975727891.014126778
#Sta/Elev= 30
       0  112.84    9.06  112.31   47.46  111.26    75.1  109.88    82.1  110.39
  107.55  109.09  138.48   108.3  152.68  106.96  161.44  106.61  182.62  106.17
  198.16  106.66  259.87  105.55  286.13  104.54  296.66  104.87  320.92  104.86
   333.5  104.45  370.61  100.54  398.19   98.93  406.72   97.24  408.55   96.43
  418.49    92.3  430.67   94.77  452.46   99.21     472   99.81  485.28   99.55
  506.89  100.87  526.11  104.31   561.6  107.53  585.76  109.47  627.77  110.33
#Mann= 6 ,-1 , 0
       0    .045       0   47.46     .09       0  320.92    .085       0
  408.55    .055       0  430.67     .08       0   561.6    .045       0
Bank Sta=408.55,430.67
XS Rating Curve= 0 ,0
Exp/Cntr=0.3,0.1

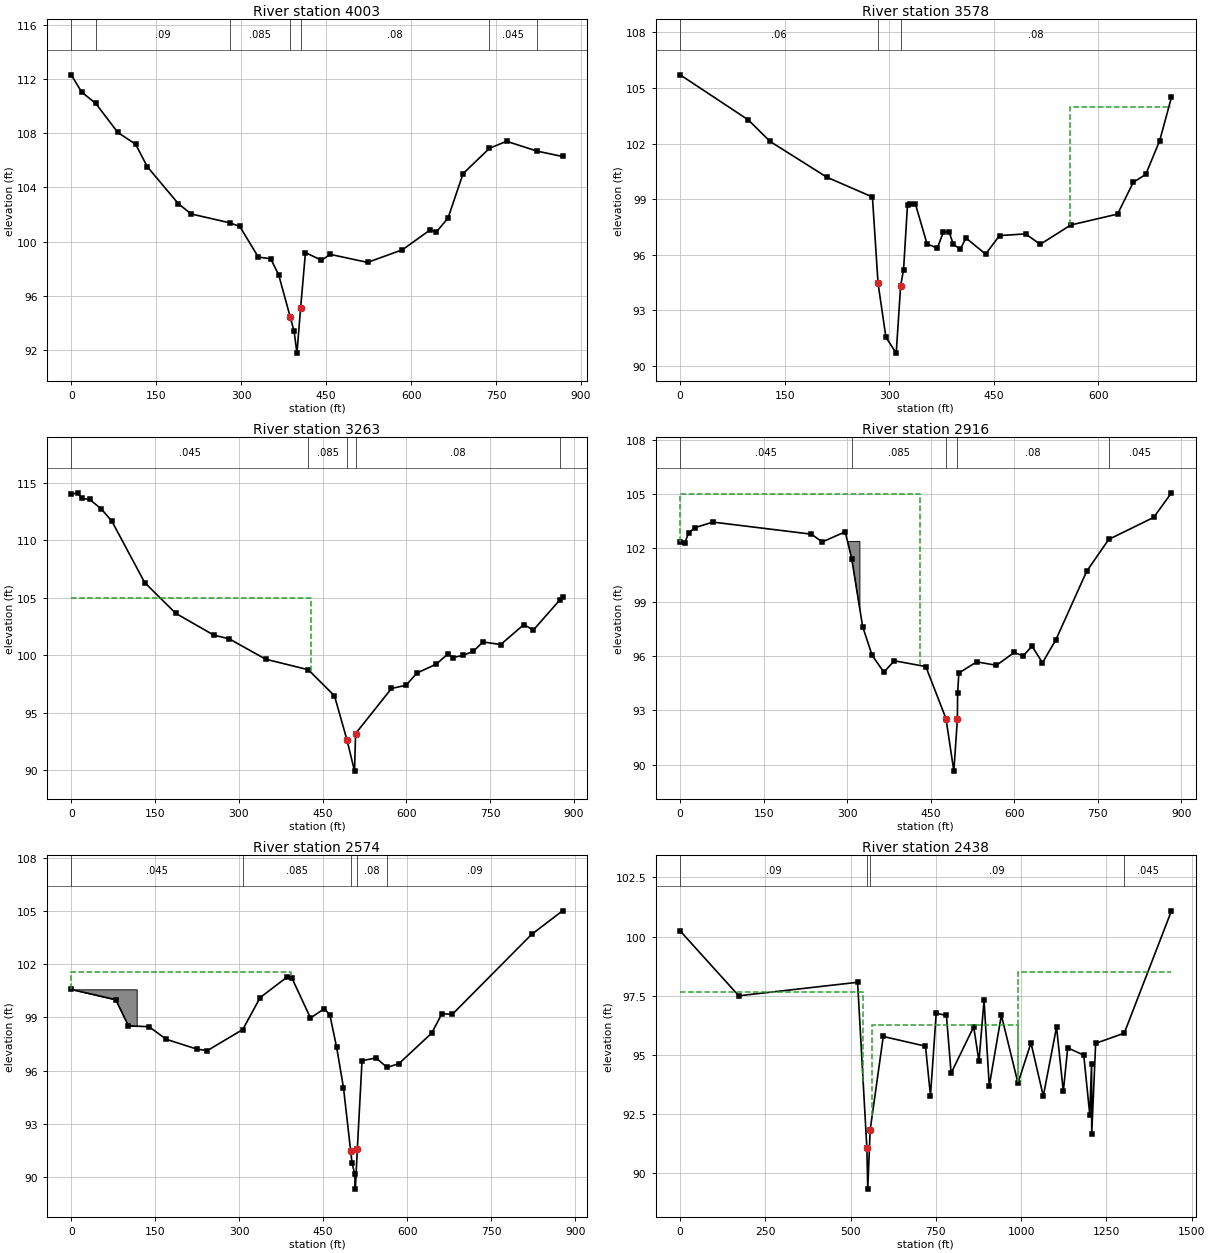
Type RM Length L Ch R = 1 ,4003    ,443.88,424.81,408.46
XS GIS Cut Line= 3
2330713.01919746727385.0482540132330391.45162964727523.744153023
2330061.08125019727921.552516937
#Sta/Elev= 30
       0   112.3   18.38  111.03   43.28  110.19   82.27  108.05  113.72  107.18
  134.19  105.53  189.27  102.79  211.86  102.04  279.71  101.39  297.61  101.12
  330.28   98.86  352.11   98.74  366.25   97.55  386.82   94.41   393.5   93.38
  398.47   91.78  404.95   95.11  413.48   99.19   441.8   98.63  457.41   99.06
  523.08   98.47  584.63    99.4  633.45  100.86  644.58  100.71  665.21  101.74
  691.67  105.01  738.25  106.88  768.49   107.4   822.9  106.67  867.31  106.28
#Mann= 7 ,-1 , 0
       0    .045       0   43.28     .09       0  279.71    .085       0
  386.82    .055       0  404.95     .08       0  738.25    .045       0
   822.9     .08       0
Bank Sta=386.82,404.95
XS Rating Curve= 0 ,0
Exp/Cntr=0.3,0.1

Type RM Length L Ch R = 1 ,3578    ,308.98,314.67,320.06
XS GIS Cut Line= 2
2330141.09778023727087.2818269732329815.92547798727713.110369682
#Sta/Elev= 30
       0  105.71   97.77  103.28  129.01  102.12  210.47  100.19  275.98   99.12
  284.05   94.47  295.33   91.56  310.13    90.7  316.48   94.33   320.7   95.21
  326.34    98.7   330.4   98.77  337.79   98.73  354.31    96.6  369.05   96.36
  377.75   97.22  385.84   97.25     392   96.59     402   96.29  410.23   96.91
  438.49   96.04  458.47   97.04  495.77   97.13  516.94   96.57  560.71   97.61
  627.92    98.2  650.38   99.91  668.36  100.34  688.37  102.16  705.26   104.5
#Mann= 3 , 0 , 0
       0     .06       0  284.05    .055       0  316.48     .08       0
#XS Ineff= 2 , 0
       0                     560       0     104
Permanent Ineff=
       F       F
Bank Sta=284.05,316.48
XS Rating Curve= 0 ,0
Exp/Cntr=0.3,0.1

Type RM Length L Ch R = 1 ,3263    ,339.25,347.44,341.08
XS GIS Cut Line= 3
2329973.19424534726800.009373665 2329658.3751173727320.772681236
2329536.87313271  727562.9646492
#Sta/Elev= 30
       0     114   11.66  114.13    18.9  113.65   33.03  113.55   53.61  112.74
   72.76  111.66  131.51  106.32  187.03  103.65  255.23  101.75  282.82  101.43
  347.88   99.66  424.44   98.74  471.25   96.47  493.85    92.6  507.17   89.92
  509.06   93.19  573.33   97.11  599.38   97.39  618.86   98.45  653.59   99.23
  674.66  100.13  683.57    99.8  701.86     100  720.12  100.35  736.99  101.16
  768.81  100.93  810.27  102.67  827.28  102.19  874.12  104.78  879.49  105.07
#Mann= 5 ,-1 , 0
       0    .045       0  424.44    .085       0  493.85    .055       0
  509.06     .08       0  874.12    .045       0
#XS Ineff= 2 , 0
       0     430     105               0
Permanent Ineff=
       F       F
Bank Sta=493.85,509.06
XS Rating Curve= 0 ,0
Exp/Cntr=0.3,0.1

Type RM Length L Ch R = 1 ,2916    ,360.7,341.7,252.8
XS GIS Cut Line= 3
2329679.36305809726689.8226785662329318.17348099727235.756321907
2329244.15206051727451.091362953
#Sta/Elev= 30
       0  102.35    7.92  102.25   15.48  102.85   27.37  103.13   58.76  103.43
  235.72  102.76  255.12  102.33  296.38  102.89   308.1   101.4  327.72   97.64
  344.76   96.05   365.8   95.12  384.61   95.75  441.14   95.43  477.35   92.55
   491.5   89.64   497.8    92.5  498.29   93.94  500.42   95.07  532.52   95.69
  567.96    95.5  600.02   96.21  616.07   96.02  631.94   96.56  650.63   95.64
  674.85   96.92  729.95   100.7  769.63  102.47  850.44  103.69   882.3  105.05
#Mann= 5 ,-1 , 0
       0    .045       0   308.1    .085       0  477.35    .055       0
   497.8     .08       0  769.63    .045       0
#XS Ineff= 2 , 0
       0     430     105               0
Permanent Ineff=
       F       F
#Block Obstruct= 1 ,-1
       0  322.79102.3505
Bank Sta=477.35,497.8
XS Rating Curve= 0 ,0
Exp/Cntr=0.3,0.1

Type RM Length L Ch R = 1 ,2574    ,125.14,136.39,203.79
XS GIS Cut Line= 4
2329306.82986259726642.8932561872329091.57501411726960.956391335
2329052.36928844727148.2764625552329074.23925304727449.409058571
#Sta/Elev= 30
       0  100.58   79.42     100  101.94   98.53  138.98   98.48  169.72   97.77
  225.24   97.21  243.31   97.14  306.29   98.32  337.41  100.12  384.92  101.26
   393.8  101.24  427.26   98.97  452.29    99.5  461.98   99.12  474.05   97.31
  486.17   95.05  498.95   91.51  501.47   90.81  506.39   90.18  507.37   89.34
  510.96   91.61  519.33   96.57  544.47   96.72  563.97   96.19  585.19    96.4
  643.79   98.12  661.89   99.21  680.65   99.18  822.03  103.67  877.36     105
#Mann= 5 ,-1 , 0
       0    .045       0  306.29    .085       0  498.95    .055       0
  510.96     .08       0  563.97     .09       0
#XS Ineff= 2 , 0
           392.2  101.53
Permanent Ineff=
       F       F
#Block Obstruct= 1 ,-1
       0  116.89100.5832
Bank Sta=498.95,510.96
XS Rating Curve= 0 ,0
Exp/Cntr=0.5,0.3

Type RM Length L Ch R = 1 ,2438    ,88.93,89.28,92.5
BEGIN DESCRIPTION:
Survyed Section
END DESCRIPTION:
XS GIS Cut Line= 6
2329232.93640614726597.9146327972328993.47874737726953.328426361
 2328933.9029007727056.137399673 2328931.7466011727061.736401558
2328922.47889996727074.6000013352328490.78909683727831.614059448
#Sta/Elev= 30
       0  100.24  171.85    97.5   520.3   98.07 547.467   91.08 550.104   89.33
 557.282   91.84  595.57   95.78  719.42   95.37  734.03   93.28   750.9   96.76
   780.8   96.67  794.56   94.23   860.8   96.19  876.26   94.73  891.14   97.31
  906.46   93.69  941.94   96.68  990.66   93.81 1028.77   95.51  1064.9   93.26
 1103.78   96.18 1123.59   93.46 1136.55    95.3 1183.59   94.99 1201.16   92.48
  1206.5   94.63 1206.94   91.65 1218.46   95.49 1302.31   95.92 1440.77  101.09
#Mann= 4 ,-1 , 0
       0     .09       0 547.467    .055       0 557.282     .09       0
 1302.31    .045       0
#XS Ineff= 3 ,-1
       0     537   97.64     563     990   96.26     990    1500    98.5
Permanent Ineff=
       F       F       F
Bank Sta=547.467,557.282
XS Rating Curve= 0 ,0
Exp/Cntr=0.5,0.3

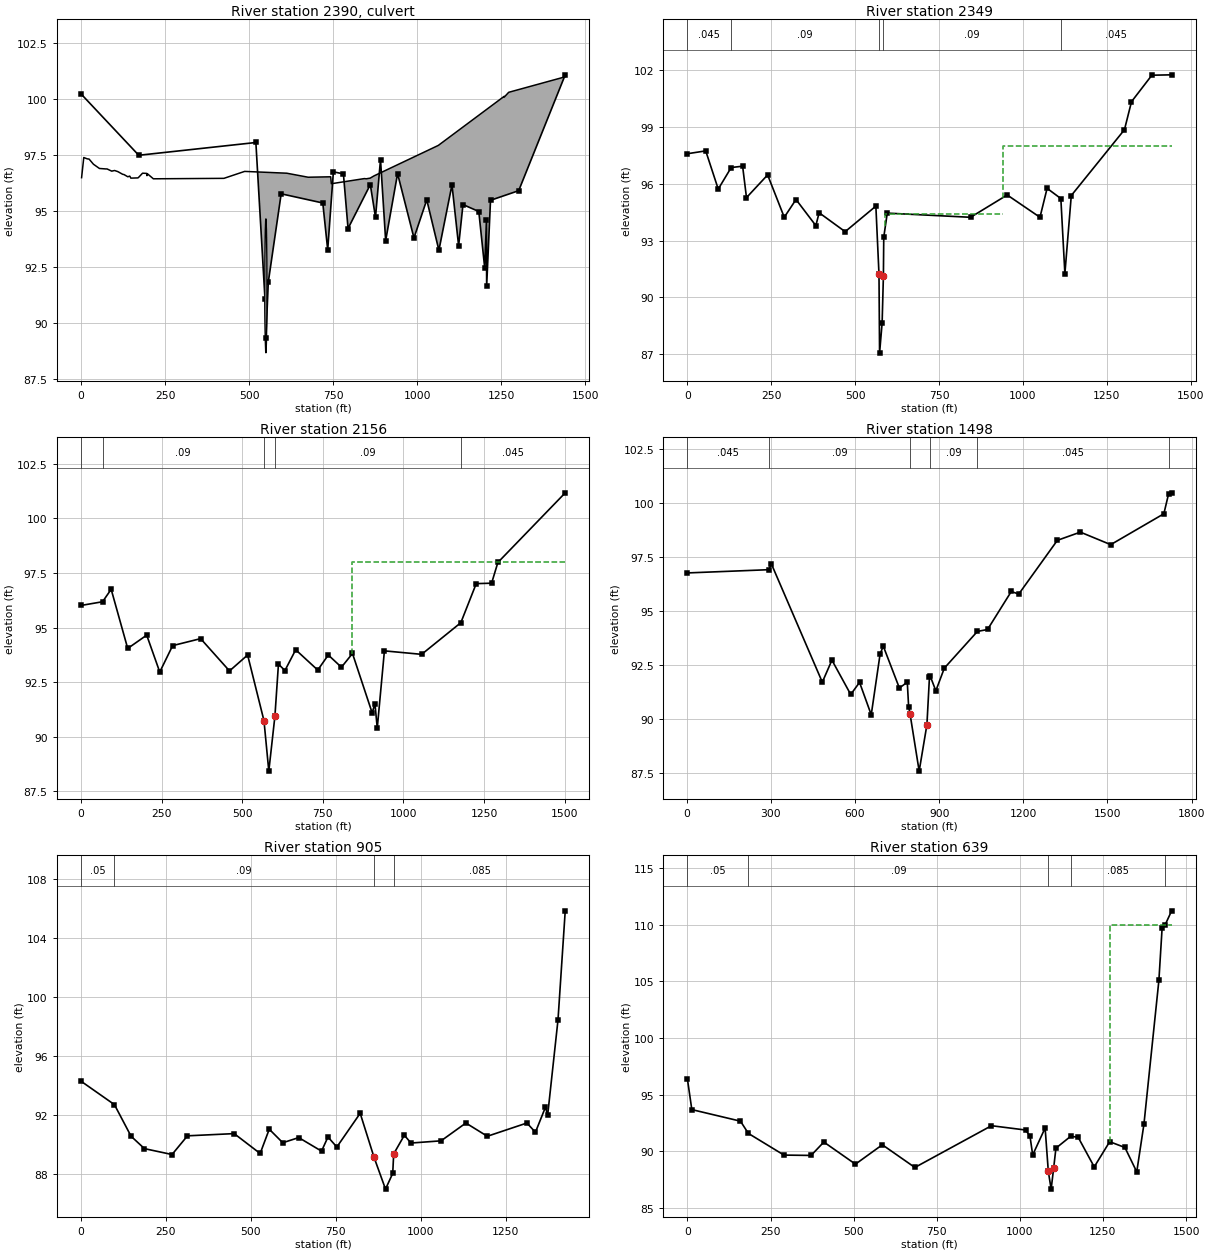
Type RM Length L Ch R = 2 ,2390    ,,,
BEGIN DESCRIPTION:
London Church Rd.
END DESCRIPTION:
Bridge Culvert--1,0,-1,-1, 0
Deck Dist Width WeirC Skew NumUp NumDn MinLoCord MaxHiCord MaxSubmerge Is_Ogee
35,20,2.6,0, 45, 45, , , 0.98, 0, 1,1,,
   1.761   8.261  18.531  24.051  37.031  54.921  55.441  55.551  73.581  77.571
  91.611  93.621  99.961 109.701 124.091 127.821 139.291 144.931 146.231 148.291
 169.511 172.401 183.121 183.981 195.681 196.281 197.181 215.271 425.241 486.887
     550  612.09 675.931 742.904 744.871 843.301 848.601 860.451 871.7911063.091
1259.0711259.2511259.5311272.531    1440
    96.5    97.4   97.34   97.33    97.1   96.91   96.91   96.91   96.89   96.89
   96.79    96.8   96.82   96.77   96.65   96.64   96.54   96.57   96.54   96.48
   96.49   96.53    96.7    96.7   96.69   96.59   96.68   96.45   96.47   96.78
   96.74    96.7   96.52   96.54   96.23   96.46   96.45   96.48   96.58   97.94
  100.13  100.11   100.1  100.31     101
                                                                                
                                                                                
                                                                                
                                                                                
                                        
   1.761   8.261  18.531  24.051  37.031  54.921  55.441  55.551  73.581  77.571
  91.611  93.621  99.961 109.701 124.091 127.821 139.291 144.931 146.231 148.291
 169.511 172.401 183.121 183.981 195.681 196.281 197.181 215.271 425.241 486.887
     550  612.09 675.931 742.904 744.871 843.301 848.601 860.451 871.7911063.091
1259.0711259.2511259.5311272.531    1440
    96.5    97.4   97.34   97.33    97.1   96.91   96.91   96.91   96.89   96.89
   96.79    96.8   96.82   96.77   96.65   96.64   96.54   96.57   96.54   96.48
   96.49   96.53    96.7    96.7   96.69   96.59   96.68   96.45   96.47   96.78
   96.74    96.7   96.52   96.54   96.23   96.46   96.45   96.48   96.58   97.94
  100.13  100.11   100.1  100.31     101
                                                                                
                                                                                
                                                                                
                                                                                
                                        
BR Coef=-1 , 0 , 0 ,, 0 ,,,0.8,-1,,0,
WSPro=,,,, 1 ,,,, 0 ,,,, 0 ,,,,-1 ,-1 ,-1 , 0 , 0 , 0 , 0 , 0
Culvert=1,6,,50,0.013,0.5,1,1,1,88.67,550.1,88.42,572.7,Culvert #1  , 0 ,22
Culvert Bottom n=0.012
BC Design=,, 0 ,, 0 ,,,,,,
BC Use User HTab Curves=0
BC User HTab FreeFlow(D)= 0

Type RM Length L Ch R = 1 ,2349    ,193.56,193.37,192.64
BEGIN DESCRIPTION:
Survyed Section
END DESCRIPTION:
XS GIS Cut Line= 6
2329168.68122864726549.7232484822329051.60994911726710.169840813
 2328850.6953001727023.7037010192328845.79530048727036.780900002
2328813.30239964727082.6736011512328429.74667645727786.635434151
#Sta/Elev= 30
       0   97.59   54.57   97.74   91.86   95.72  130.46   96.86  164.51   96.93
  176.08   95.27  239.07   96.47  288.64   94.23  323.63   95.17  382.77   93.79
  392.59   94.47  470.14   93.47 561.661   94.82 570.968   91.22 572.702   87.05
 580.327   88.65  584.11   91.12 585.181   93.18 595.645   94.45  843.95   94.23
  953.07   95.41 1050.75   94.23    1072   95.76 1112.98   95.22 1124.99   91.25
 1144.07   95.38 1302.55   98.86 1323.53  100.34 1384.22  101.74 1443.18  101.76
#Mann= 5 ,-1 , 0
       0    .045       0  130.46     .09       0 570.968    .055       0
  584.11     .09       0 1112.98    .045       0
#XS Ineff= 3 ,-1
       0     554   94.42     590     940   94.42     940    1500      98
Permanent Ineff=
       T       F       F
Bank Sta=570.968,584.11
XS Rating Curve= 0 ,0
Exp/Cntr=0.5,0.3

Type RM Length L Ch R = 1 ,2156    ,654.7,657.4,676.32
XS GIS Cut Line= 4
2328963.20712185 726455.166792872328710.86136913726885.836878777
2328554.40700245727166.7818164832328227.34286308727764.146121025
#Sta/Elev= 30
       0   96.01   66.83   96.18   93.55   96.75  144.86   94.04  203.77   94.65
  244.24   92.96  284.22   94.17     371   94.49  460.54   93.01  516.73   93.74
  567.47   90.73  582.45   88.42  601.41   90.94  612.34   93.32  632.49   93.03
  665.84   93.98  734.23   93.05  766.92   93.74  807.69   93.18  841.96   93.81
  902.98   91.09  911.58   91.51  918.79   90.39  940.99   93.93 1056.44   93.77
 1177.98   95.22 1225.72   97.01 1273.42   97.03 1292.88   97.98 1501.77  101.17
#Mann= 5 ,-1 , 0
       0    .045       0   66.83     .09       0  567.47    .055       0
  601.41     .09       0 1177.98    .045       0
#XS Ineff= 2 , 0
       0     375             840       0      98
Permanent Ineff=
       F       F
Bank Sta=567.47,601.41
XS Rating Curve= 0 ,0
Exp/Cntr=0.3,0.1

Type RM Length L Ch R = 1 ,1498    ,544.01,593.34,598.69
XS GIS Cut Line= 3
2328679.88617332726135.2724667582328387.98080921726199.532526016
2327610.92293297727396.452321173
#Sta/Elev= 30
    2.72   96.78  293.64   96.93  301.61   97.21  483.53   91.72  517.81   92.74
  584.79   91.15  616.28   91.71  657.92   90.21  689.47   93.02  700.81   93.39
   758.2   91.45  786.42   91.72  791.19   90.59  796.48   90.23  828.75    87.6
  856.39   89.75  865.55   91.98  868.4891.99075   888.2   91.32  918.42   92.37
 1036.32   94.07 1072.46   94.16 1157.09   95.92 1183.68    95.8 1321.33   98.29
 1403.26   98.67 1511.55   98.09 1700.89   99.52 1717.54  100.43 1728.65  100.49
#Mann= 6 ,-1 , 0
    2.72    .045       0  293.64     .09       0  796.48    .055       0
  868.48     .09       0 1036.32    .045       0 1717.54    .085       0
#XS Ineff= 2 , 0
       0     700                       0
Permanent Ineff=
       F       F
Bank Sta=796.48,856.39
XS Rating Curve= 0 ,0
Exp/Cntr=0.3,0.1

Type RM Length L Ch R = 1 ,905     ,261.75,266.32,285.03
XS GIS Cut Line= 3
2328269.10873032725791.5121412282327613.70590973726331.255640984
2327257.08966923726784.254650116
#Sta/Elev= 30
       0    94.3   98.36   92.71  147.44   90.56  186.78   89.72  267.98   89.32
  313.44   90.59  450.95   90.74  527.43   89.39  554.21   91.04  594.03   90.12
  641.03   90.47  708.13   89.55  727.02   90.51   753.2   89.83   821.9   92.12
  862.73   89.13  896.47   86.97  917.71   88.04  920.53   89.36  951.91   90.63
  971.49    90.1 1060.09   90.25 1133.09   91.46 1196.22   90.56 1312.81   91.46
 1337.81   90.83 1367.46   92.54 1373.77   91.98 1404.26   98.46 1425.57  105.87
#Mann= 4 ,-1 , 0
       0     .05       0   98.36     .09       0  862.73    .055       0
  920.53    .085       0
#XS Ineff= 2 , 0
       0     555            1050       0
Permanent Ineff=
       F       F
Bank Sta=862.73,920.53
XS Rating Curve= 0 ,0
Exp/Cntr=0.5,0.3

Type RM Length L Ch R = 1 ,639     ,57.7,51.36,43.7
XS GIS Cut Line= 6
2328278.74700737725698.3421335222327442.07897091726101.102781296
2327370.41960049726184.3408012392327362.19439983726220.817799568
 2327342.2123003726280.3760013582327066.00068665726437.434403419
#Sta/Elev= 30
       0   96.39   13.26   93.69  159.59   92.67  183.39   91.59  290.51   89.68
  372.02   89.65  410.39   90.83  505.48   88.88  586.34   90.59  684.19   88.59
  914.72   92.27 1017.09   91.89  1030.4   91.371038.652   89.691076.054   92.07
1085.642   88.24 1094.16   86.68 1101.84   88.561108.547   90.29 1153.08   91.34
 1175.43   91.25 1223.79   88.64 1270.24   90.86 1316.09   90.35  1351.7    88.2
 1373.28    92.4 1418.28  105.08 1427.98   109.7 1436.98  109.97 1456.64  111.21
#Mann= 5 ,-1 , 0
       0     .05       0  183.39     .09       01085.642    .055       0
 1153.08    .085       0 1436.98    .035       0
#XS Ineff= 4 ,-1
       0     915             916    1068   90.14    1124    1270   90.14
    1270    1500     110
Permanent Ineff=
       T       F       F       F
Bank Sta=1085.642,1101.84
XS Rating Curve= 0 ,0
Exp/Cntr=0.5,0.3

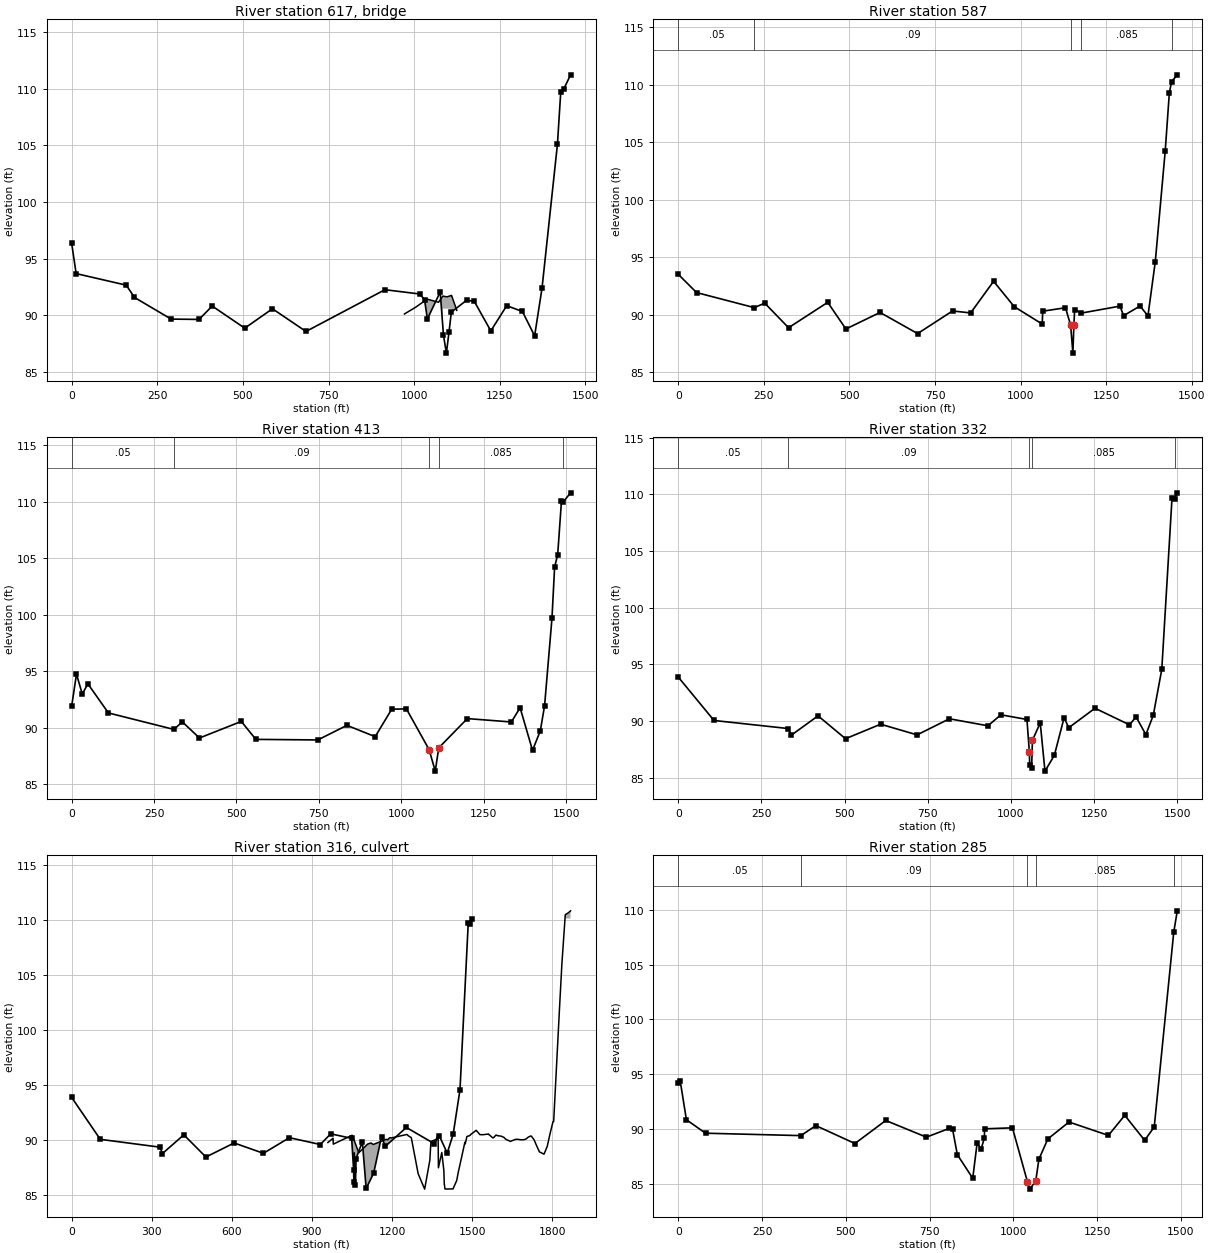
Type RM Length L Ch R = 3 ,617     ,,,
BEGIN DESCRIPTION:
Sewer Easement Near London Church Rd.
END DESCRIPTION:
Bridge Culvert--1,0,-1,-1, 0
Deck Dist Width WeirC Skew NumUp NumDn MinLoCord MaxHiCord MaxSubmerge Is_Ogee
15,12,2.6,0, 10, 13, , , 0.98, 0, 0,0,,
  971.55 1004.631038.0621071.084 1083.551083.6331095.9981109.063  1109.11124.521
   90.13   90.73   91.44   91.16    91.7   91.71   91.64   91.77   91.77   90.45
                                            90.6    90.6    90.6
  991.86 1008.92 1015.23 1022.55 1055.631089.0621122.084  1134.61134.6331146.998
1160.0631160.0631175.521
   89.68   90.02    90.1   90.13   90.73   91.44   91.16   91.71   91.71   91.64
   91.77   91.77   90.45
                                                                    90.6    90.6
    90.6
BR Coef=-1 , 0 , 0 ,, 0 ,,,0.8,0,,0,
WSPro=,,,, 1 ,,,, 0 ,,,, 0 ,,,,-1 ,-1 ,-1 , 0 , 0 , 0 , 0 , 0
BC Design=,, 0 ,, 0 ,,,,,,
BC Use User HTab Curves=0
BC User HTab FreeFlow(D)= 0

Type RM Length L Ch R = 1 ,587     ,48.35,173.54,110.39
XS GIS Cut Line= 6
2328256.25769424725627.6614360812327388.83264065726087.439407349
2327321.03840065726161.8805999762327314.67739964726210.491399765
2327290.79030037 726245.948499682327042.34711552726377.183400154
#Sta/Elev= 30
       0   93.51   53.29   91.93  221.93   90.62   252.5   91.01  322.09   88.87
  436.56   91.08  489.68   88.76  589.48    90.2  699.24   88.36  801.29   90.33
  854.27   90.16   921.3   92.91  981.74    90.7 1063.36   89.19 1064.92   90.31
1131.352   90.611146.403    89.1 1152.96   86.66 1155.92   89.071158.168   90.45
 1177.7390.14491 1290.64   90.75 1301.21   89.92 1349.28   90.76 1372.36    89.9
 1393.83   94.62 1422.87  104.26 1434.89  109.31 1441.51  110.29 1458.13  110.88
#Mann= 5 ,-1 , 0
       0     .05       0  221.93     .09       01146.403    .055       0
 1177.73    .085       0 1441.51    .035       0
#XS Ineff= 2 , 0
       0    1000            1250       0
Permanent Ineff=
       F       F
Bank Sta=1146.403,1155.92
XS Rating Curve= 0 ,0
Exp/Cntr=0.5,0.3

Type RM Length L Ch R = 1 ,413     ,83.58,81.23,21.68
XS GIS Cut Line= 4
2328303.65085316725564.224338531 2327380.3817749726035.526941299
2327287.42224407726077.7812757492327023.03085041726343.379935265
#Sta/Elev= 30
       0   91.87   14.77   94.73   32.41   92.97   49.28   93.88  111.54    91.3
  310.26   89.84  335.84   90.51  387.82   89.08   514.7   90.55  558.81   88.96
  746.79   88.91  835.07    90.2  920.81    89.2  970.96   91.63 1015.48   91.66
 1084.26   88.06 1103.05   86.15 1113.62   88.21 1200.32    90.8 1333.81    90.5
 1360.41   91.76 1398.06   87.99 1421.66   89.71 1434.62   91.93 1457.04   99.67
 1465.09  104.21  1474.4  105.31  1485.8  110.02 1490.32  109.94 1513.48  110.78
#Mann= 5 ,-1 , 0
       0     .05       0  310.26     .09       0 1084.26    .055       0
 1113.62    .085       0 1490.32    .035       0
#XS Ineff= 2 , 0
       0     850            1270       0
Permanent Ineff=
       F       F
Bank Sta=1084.26,1113.62
XS Rating Curve= 0 ,0
Exp/Cntr=0.5,0.3

Type RM Length L Ch R = 1 ,332     ,44.26,46.96,73.24
BEGIN DESCRIPTION:
Survyed Section
END DESCRIPTION:
XS GIS Cut Line= 6
2328272.32148933725521.6403932572327380.13339996725941.051401138
2327315.90370083725985.7096004492327300.20100021726003.113401413
2327254.82604408726092.2684736252327018.20178127726296.296535492
#Sta/Elev= 30
       0   93.87  107.27   90.05  330.13   89.34  340.12   88.76  420.11   90.46
  502.84   88.44  608.29   89.72   718.1   88.78  815.27    90.2  931.04   89.58
  970.04   90.551048.411   90.141055.697   87.271056.706   86.13  1062.5   85.87
1064.942    88.31088.412   89.84 1102.66   85.58 1130.82   86.97 1160.21    90.3
 1174.11   89.41 1253.15   91.13 1356.58   89.67 1376.73   90.36 1406.14    88.8
 1428.38   90.51 1453.96   94.56 1484.76  109.69  1492.5  109.62  1500.6  110.14
#Mann= 5 ,-1 , 0
       0     .05       0  330.13     .09       01055.697    .055       0
1064.942    .085       0  1492.5    .035       0
#XS Ineff= 2 , 0
       0     920            1088       0
Permanent Ineff=
       F       F
Bank Sta=1055.697,1064.942
XS Rating Curve= 0 ,0
Exp/Cntr=0.5,0.3

Type RM Length L Ch R = 2 ,316     ,,,
BEGIN DESCRIPTION:
Sanitary Sewer Easment Near London Church Rd. Pipe is Corrugated Plastic
END DESCRIPTION:
Bridge Culvert--1,0,-1,-1, 0
Deck Dist Width WeirC Skew NumUp NumDn MinLoCord MaxHiCord MaxSubmerge Is_Ogee
8,12,2.6,0, 89, 88, , , 0.98, 0, 1,1,,
  959.41  978.79 979.6191011.3361050.4911075.2031108.219 1120.72 1128.92 1177.64
 1183.46 1189.66 1193.15 1197.21 1254.67 1256.92 1260.39 1271.59 1297.37 1312.96
 1321.73 1335.32 1341.04 1345.18 1362.77 1363.46 1365.19 1372.02 1373.17 1385.84
 1393.57 1395.17 1395.19 1397.82 1427.88 1434.35 1441.63 1447.21 1459.06 1472.28
 1473.71 1479.83 1489.59 1492.08 1494.65 1514.49 1514.52 1514.58 1523.97 1528.58
 1539.67 1559.51 1560.61 1561.44 1576.76 1579.94 1588.78  1595.1 1607.89 1611.57
 1618.28 1623.54 1626.48 1635.36 1642.62 1659.42 1662.04 1663.92  1668.1 1682.48
  1693.3 1700.51 1710.09 1719.66 1722.98 1731.51  1739.7 1751.32 1759.67 1768.44
 1780.67 1790.29 1802.01 1804.68 1825.99 1835.44 1848.15 1860.11 1867.92
   89.76   90.15   89.61   89.98   90.42   88.83   89.62   89.72   89.58   90.05
   90.01   90.17    90.2   90.18   90.49   90.47   90.37   90.21   86.92   86.02
   85.52   87.37   88.14   89.86   90.02   90.04   90.05   90.45   87.46   88.85
   87.21      86      86   85.53   85.54    85.9    86.3   87.02   88.32   89.79
   89.64   90.31   90.38   90.42    90.5   90.87   90.87   90.87   90.61   90.48
   90.47   90.53    90.5   90.51   90.18   90.21   90.44   90.38   90.34    90.3
   90.23    90.1   90.04   89.95   89.86   90.03   90.04   90.05   90.06   90.01
   90.02   90.07   90.26   90.36   90.28      90   89.53   88.91   88.81    88.7
   89.41   90.48   91.65   91.67  101.73  106.02  110.49  110.67  110.84
                                                                                
                                                                                
                                                                                
                                                                                
                                                                                
                                                                                
                                                                                
                                                                                
                                                                        
  959.41  978.79 979.6191011.3361050.4911108.219 1120.72 1128.92 1177.64 1183.46
 1189.66 1193.15 1197.21 1254.67 1256.92 1260.39 1271.59 1297.37 1312.96 1321.73
 1335.32 1341.04 1345.18 1362.77 1363.46 1365.19 1372.02 1373.17 1385.84 1393.57
 1395.17 1395.19 1397.82 1427.88 1434.35 1441.63 1447.21 1459.06 1472.28 1473.71
 1479.83 1489.59 1492.08 1494.65 1514.49 1514.52 1514.58 1523.97 1528.58 1539.67
 1559.51 1560.61 1561.44 1576.76 1579.94 1588.78  1595.1 1607.89 1611.57 1618.28
 1623.54 1626.48 1635.36 1642.62 1659.42 1662.04 1663.92  1668.1 1682.48  1693.3
 1700.51 1710.09 1719.66 1722.98 1731.51  1739.7 1751.32 1759.67 1768.44 1780.67
 1790.29 1802.01 1804.68 1825.99 1835.44 1848.15 1860.11 1867.92
   89.76   90.15   89.61   89.98   90.42   89.62   89.72   89.58   90.05   90.01
   90.17    90.2   90.18   90.49   90.47   90.37   90.21   86.92   86.02   85.52
   87.37   88.14   89.86   90.02   90.04   90.05   90.45   87.46   88.85   87.21
      86      86   85.53   85.54    85.9    86.3   87.02   88.32   89.79   89.64
   90.31   90.38   90.42    90.5   90.87   90.87   90.87   90.61   90.48   90.47
   90.53    90.5   90.51   90.18   90.21   90.44   90.38   90.34    90.3   90.23
    90.1   90.04   89.95   89.86   90.03   90.04   90.05   90.06   90.01   90.02
   90.07   90.26   90.36   90.28      90   89.53   88.91   88.81    88.7   89.41
   90.48   91.65   91.67  101.73  106.02  110.49  110.67  110.84
                                                                                
                                                                                
                                                                                
                                                                                
                                                                                
                                                                                
                                                                                
                                                                                
                                                                
BR Coef=-1 , 0 , 0 ,, 0 ,,,0.8,-1,,0,
WSPro=,,,, 1 ,,,, 0 ,,,, 0 ,,,,-1 ,-1 ,-1 , 0 , 0 , 0 , 0 , 0
Culvert=1,3,,20,0.024,0.9,1,2,3,85.85,1058,84.64,1050,Culvert #1  , 0 ,6.6
Culvert Bottom n=0.024
BC Design=,, 0 ,, 0 ,,,,,,
BC Use User HTab Curves=0
BC User HTab FreeFlow(D)= 0

Type RM Length L Ch R = 1 ,285     ,21.49,86.21,172.2
BEGIN DESCRIPTION:
Survyed Section
END DESCRIPTION:
XS GIS Cut Line= 6
2328257.62432766725463.8357772832327364.68640041725907.368599892
2327360.55495358 725921.621932032327268.51200104725977.710201263
2327143.84049225726097.003693581 2326967.9918623726183.429663658
#Sta/Elev= 30
       0   94.16    5.49    94.4   24.07   90.85   81.13   89.62  365.69    89.4
  410.67   90.31  527.19   88.68  619.24   90.78  740.48   89.26  808.94   90.06
  818.72   89.98  832.93   87.66  878.87   85.51  891.89    88.7  903.97   88.18
  913.74    89.2   914.1   90.02 997.406   90.111042.359   85.17 1049.48   84.52
1067.006   85.271076.409   87.251103.211    89.1 1166.23   90.64 1283.83   89.42
 1332.74   91.25  1392.1   88.97 1420.73   90.19 1478.99  107.96 1489.56   109.9
#Mann= 5 ,-1 , 0
       0     .05       0  365.69     .09       01042.359    .055       0
1067.006    .085       0 1478.99    .035       0
#XS Ineff= 2 , 0
       0     910            1175       0
Permanent Ineff=
       F       F
Bank Sta=1042.359,1067.006
XS Rating Curve= 0 ,0
Exp/Cntr=0.5,0.3

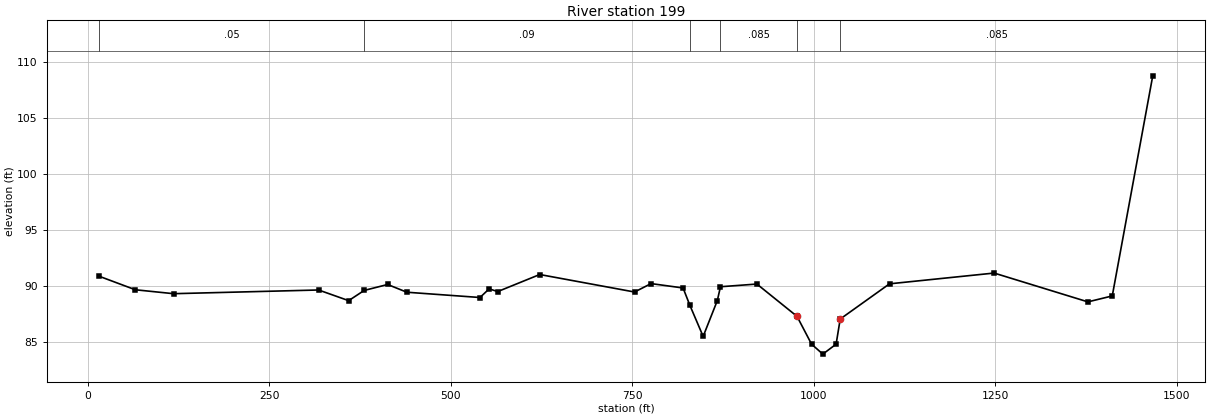
Type RM Length L Ch R = 1 ,199     ,204.56,198.99,373.34
XS GIS Cut Line= 5
2328233.96229635725440.6739782472327526.65366459725816.039676666
2327436.14316463725858.343497276 2327249.2193079725876.052072525
2326924.56208229726037.396877289
#Sta/Elev= 30
   15.65   90.86   65.25   89.66  117.93   89.31  317.66   89.64  359.04   88.69
  380.44    89.6  412.73   90.13  439.28   89.44  539.93   88.97  552.57   89.74
   564.4    89.5  622.26   91.02  752.82   89.46   775.6   90.21  819.68   89.82
  829.07   88.27  847.34    85.5  866.82   88.69  871.18   89.93  921.37   90.17
  976.61   87.29  996.65   84.81 1012.16   83.92 1030.48   84.81 1036.12   87.05
 1104.02   90.19 1248.13   91.15 1377.28   88.58 1410.84   89.11  1466.6  108.74
#Mann= 6 ,-1 , 0
   15.65     .05       0  380.44     .09       0  829.07    .035       0
  871.18    .085       0  976.61    .055       0 1036.12    .085       0
#XS Ineff= 2 , 0
       0     897                       0
Permanent Ineff=
       F       F
Bank Sta=976.61,1036.12
XS Rating Curve= 0 ,0
Exp/Cntr=0.3,0.1

Chan Stop Cuts=-1
Use User Specified Reach Order=0