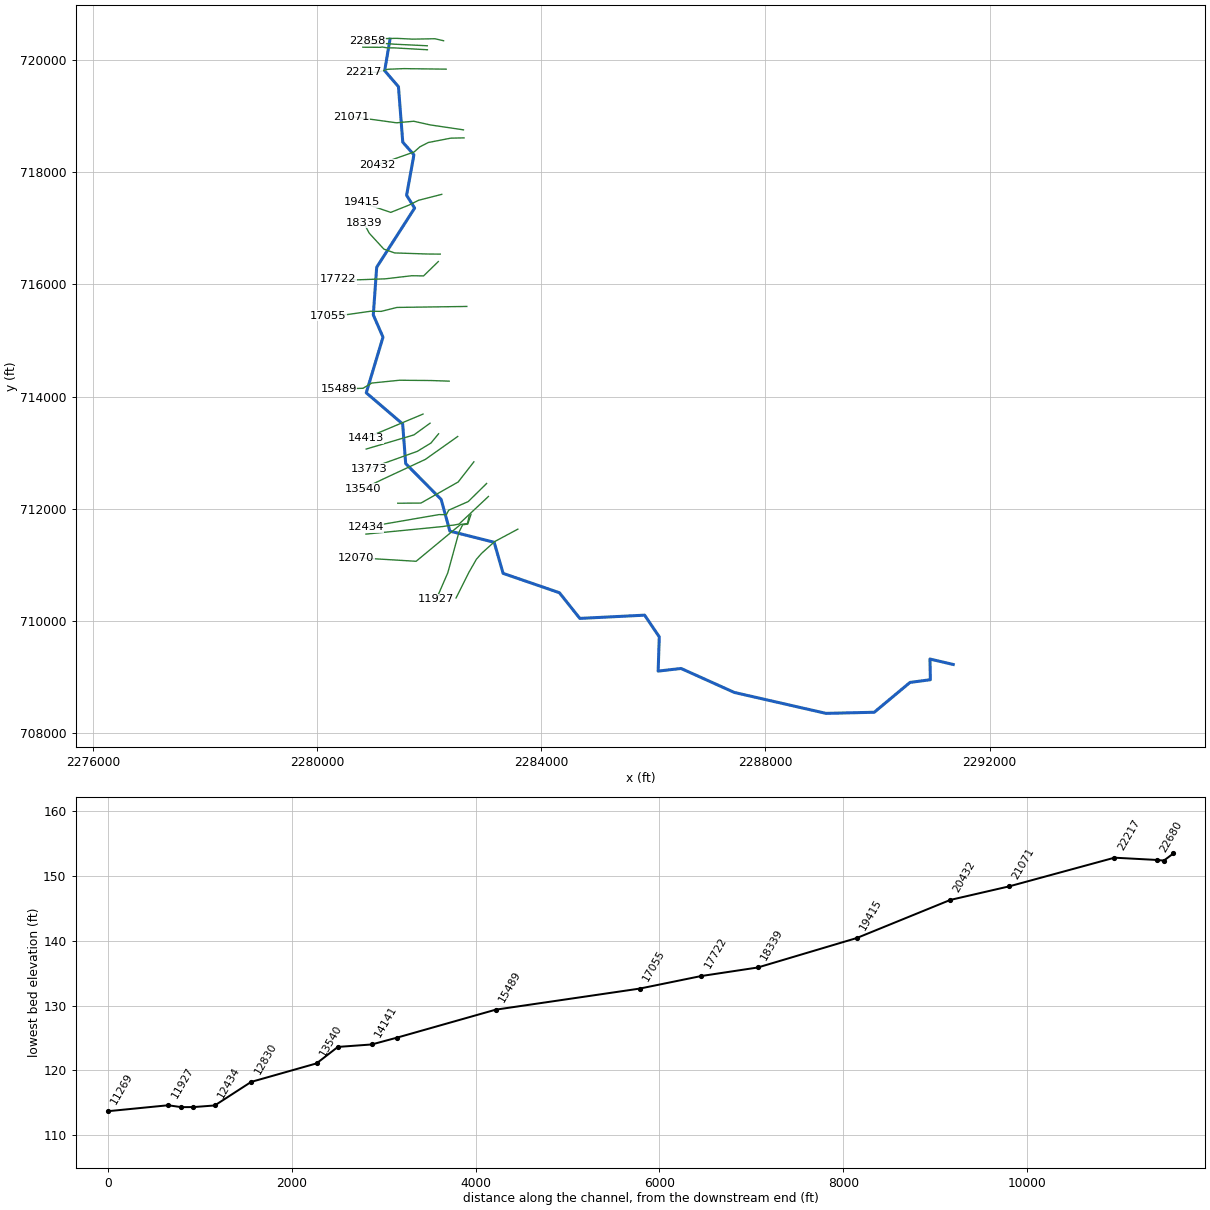
--- DTL_Little_Swamp_Main.prj (project) ---

Proj Title=DTL_Little_Swamp
Current Plan=p01
Default Exp/Contr=0.3,0.1
English Units
Geom File=g01
Flow File=f01
Flow File=f02
Plan File=p01
Plan File=p02
Y Axis Title=Elevation
X Axis Title(PF)=Main Channel Distance
X Axis Title(XS)=Station
BEGIN DESCRIPTION:
END DESCRIPTION:
DSS File=dss
DSS Export Rating Curves= 0
DSS Export Rating Curve Sorted= 0
DSS Export Volume Flow Curves= 0
DXF OffsetX= 0
DXF OffsetY= 0
DXF ScaleX= 1
DXF ScaleY= 10

--- DTL_Little_Swamp_Main.p01 (plan) ---

Plan Title=DTL_Little_Swamp
Program Version=4.00
Short Identifier=DTL_Little_S
Geom File=g01
Flow File=f01
Subcritical Flow
K Sum by GR= 0
Std Step Tol= 0.01
Critical Tol= 0.01
Num of Std Step Trials= 20
Max Error Tol= 0.3
Flow Tol Ratio= 0.001
Split Flow NTrial= 30
Split Flow Tol= 0.02
Split Flow Ratio= 0.02
Log Output Level= 0
Friction Slope Method= 1
Unsteady Friction Slope Method= 2
Unsteady Bridges Friction Slope Method= 1
Parabolic Critical Depth
Global Vel Dist= 0 , 0 , 0
Global Log Level= 0
CheckData=True
Encroach Param=-1 ,10,10, 2
Encroach River=Little Swamp
Encroach Reach=Main
Encroach Node=22858
       1     940     990
Encroach Node=22754
       1     668  727.61
Encroach Node=22680
       1     677  738.12
Encroach Node=22217
       1    1060    1120
Encroach Node=21071
       1    1035    1105
Encroach Node=20432
       1     965    1055
Encroach Node=19415
       1     505     575
Encroach Node=18339
       1     860     930
Encroach Node=17722
       1    1155    1265
Encroach Node=17055
       1    1625    1735
Encroach Node=15489
       1    1434    1509
Encroach Node=14413
       1     395     470
Encroach Node=14141
       1     480     555
Encroach Node=13773
       1     688     764
Encroach Node=13540
       1     964    1084
Encroach Node=12830
       1     845     965
Encroach Node=12434
       1  879.67  918.33
Encroach Node=12202
       1  854.67  933.33
Encroach Node=12070
       1     427     523
Encroach Node=11927
       1  443.67  526.33
Encroach Node=11269
       1  464.25     617
Encroach Node=11158
       1     440     590
Encroach Node=10888
       1     760     902
Encroach Node=9528
       1     395     660
Encroach Node=8447
       1     545  1023.8
Encroach Node=7603
       1     820    1345
Encroach Node=6423
       1    1165 1691.58
Encroach Node=5620
       1    1350    1820
Encroach Node=4649
       1    2075    2230
Encroach Node=4321
       1    2599    2669
Encroach Node=4216
       1 2584.81    2652
Encroach Node=3846
       1    3185    3405
Encroach Node=2792
       1  3477.6  3642.8
Computation Interval=1HOUR
Output Interval=1HOUR
Run HTab= 0
Run UNet= 0
Run PostProcess= 0
Run WQNet= 0
UNET Theta= 1
UNET Theta Warmup= 1
UNET ZTol= 0.02
UNET ZSATol= 0.05
UNET MxIter= 20
UNET MaxInSteps= 0
UNET DtIC= 0
UNET DtMin= 0
UNET MaxCRTS= 20
UNET WFStab= 2
UNET SFStab= 1
UNET WFX= 1
UNET SFX= 1
UNET DSS MLevel= 4
UNET DZMax Abort= 100
UNET Convert EG Bridges=-1
UNET Use Existing IB Tables=-1
UNET Froude Reduction=False
UNET Froude Limit= 1
UNET Froude Power= 10
UNET Time Slicing=0,0, 5
Instantaneous Interval=1HOUR
DSS File=dss
Write IC File= 0
Echo Input=False
Echo Output=False
Write Detailed= 0
Detailed Automatic Start=False, 10
WQ ULTIMATE=-1
WQ Max Comp Step=1HOUR
WQ Output Interval=15MIN
WQ Output Selected Increments= 0
WQ Output face flow=0
WQ Output face velocity=0
WQ Output face area=0
WQ Output face dispersion=0
WQ Output cell volume=0
WQ Output cell surface area=0
WQ Output cell continuity=0
WQ Output face conc=0
WQ Output face dconc_dx=0
WQ Output face courant=0
WQ Output face peclet=0
WQ Output face adv mass=0
WQ Output face disp mass=0
WQ Output cell mass=0
WQ Output cell source sink temp=0
WQ Output cell source sink nsm=0
WQ Output MaxMinRange=-1
WQ Daily Max Min Mean=-1
WQ Daily Range=0
WQ Daily Time=0
WQ Create Restart=0
WQ Fixed Restart=0
WQ System Summary=False
Sorting and Armoring Iterations= 10
XS Update Threshold= 0.02
Hydraulics Update Threshold= 0.02
Energy Slope Method= 1
Volume Change Method= 0
XS Weighting Method= 0
Number of US Weighted Cross Sections= 1
Number of DS Weighted Cross Sections= 1
Upstream XS Weight=0.25
Main XS Weight=0.5
Downstream XS Weight=0.25
Number of DS XS's Weighted with US Boundary= 1
Upstream Boundary Weight= 1
Weight of XSs Associated with US Boundary= 0
Number of US XS's Weighted with DS Boundary= 1
Downstream Boundary Weight= 0.5
Weight of XSs Associated with DS Boundary= 0.5
Sediment Output Level= 4
Mass or Volume Output= 0
Output Increment Type= 1
Profile and TS Output Increment= 10
XS Output Flag= 0
XS Output Increment= 10
Disregard all LS=0
Disregard all Conn=0
Disregard all Breaches=0
Disregard all Pumps=0

--- DTL_Little_Swamp_Main.p02 (plan) ---

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Plan Title=DTL_Little_Swamp_Main_Future
Short Identifier=Future
Geom File=g01
Flow File=f02
Encroach Param=-1 ,0,0, 0

--- DTL_Little_Swamp_Main.f01 (steady flow) ---

Flow Title=DTL_Little_Swamp
Program Version=4.00
Number of Profiles= 6
Profile Names=100-yr,FW,10-yr,25-yr,50-yr,500-yr
River Rch & RM=Little Swamp,Main            ,22858
     640     640     260     390     500    1040
River Rch & RM=Little Swamp,Main            ,17722
     940     940     400     580     750    1500
River Rch & RM=Little Swamp,Main            ,12070
    1030    1030     450     650     830    1650
River Rch & RM=Little Swamp,Main            ,3846
    1130    1130     490     710     900    1780
Boundary for River Rch & Prof#=Little Swamp,Main            , 1
Up Type= 0
Dn Type= 3
Dn Slope=1.195446E-03
Boundary for River Rch & Prof#=Little Swamp,Main            , 2
Up Type= 0
Dn Type= 3
Dn Slope=1.195446E-03
Boundary for River Rch & Prof#=Little Swamp,Main            , 3
Up Type= 0
Dn Type= 3
Dn Slope=1.195446E-03
Boundary for River Rch & Prof#=Little Swamp,Main            , 4
Up Type= 0
Dn Type= 3
Dn Slope=1.195446E-03
Boundary for River Rch & Prof#=Little Swamp,Main            , 5
Up Type= 0
Dn Type= 3
Dn Slope=1.195446E-03
Boundary for River Rch & Prof#=Little Swamp,Main            , 6
Up Type= 0
Dn Type= 3
Dn Slope=1.195446E-03
DSS Import GetInterval= 0
DSS Import GetPeak= 0
DSS Import FillOption= 0

--- DTL_Little_Swamp_Main.f02 (steady flow) ---

Flow Title=DTL_Little_Swamp_Main_Future
Program Version=4.00
Number of Profiles= 3
Profile Names=100-yr-10%,100-yr-20%,100-yr-35%
River Rch & RM=Little Swamp,Main            ,22858
    1110    1430    1740
River Rch & RM=Little Swamp,Main            ,17722
    1630    2090    2550
River Rch & RM=Little Swamp,Main            ,12070
    1780    2280    2790
River Rch & RM=Little Swamp,Main            ,3846
    1930    2480    3030
Boundary for River Rch & Prof#=Little Swamp,Main            , 1
Up Type= 0
Dn Type= 3
Dn Slope=1.195446E-03
Boundary for River Rch & Prof#=Little Swamp,Main            , 2
Up Type= 0
Dn Type= 3
Dn Slope=1.195446E-03
Boundary for River Rch & Prof#=Little Swamp,Main            , 3
Up Type= 0
Dn Type= 3
Dn Slope=1.195446E-03
DSS Import GetInterval= 0
DSS Import GetPeak= 0
DSS Import FillOption= 0

--- DTL_Little_Swamp_Main.g01 (geometry) ---

Geom Title=DTL_Little_Swamp
Program Version=4.00

River Reach=Little Swamp    ,Main
Reach XY= 30
 2281299.9830522  720376.4951037 2281204.8532914  719814.1457582
 2281450.5048256  719528.7564758 2281527.5719736  718538.9252938
 2281726.2607145  718312.5405466 2281595.9784752  717590.9074944
 2281739.2076419  717362.6088833 2281062.1243085  716307.0533277
 2281001.6770944  715456.7067979 2281174.5172601  715059.2845062
 2280876.1753182  714066.2792235 2281525.6659752  713510.1783277
 2281579.4854196  712803.5811055 2282212.2979196  712163.8241611
 2282367.6798641  711598.7199944 2283158.6497042  711398.8697938
 2283318.2006974  710844.3797166 2284322.5409752  710498.8936055
 2284687.1243085  710040.5602722 2285843.3743086  710098.7199944
 2286104.6590308  709711.5672166  2286084.693753  709100.4561055
 2286493.5479196  709147.3311055 2287444.0687529  708719.3797166
 2289079.4854196  708346.1158277 2289940.5965307  708366.0811055
 2290578.6173641  708898.1991611 2290942.3326419  708946.8102722
 2290934.5201419  709315.7338833  2291350.318753  709218.5116611

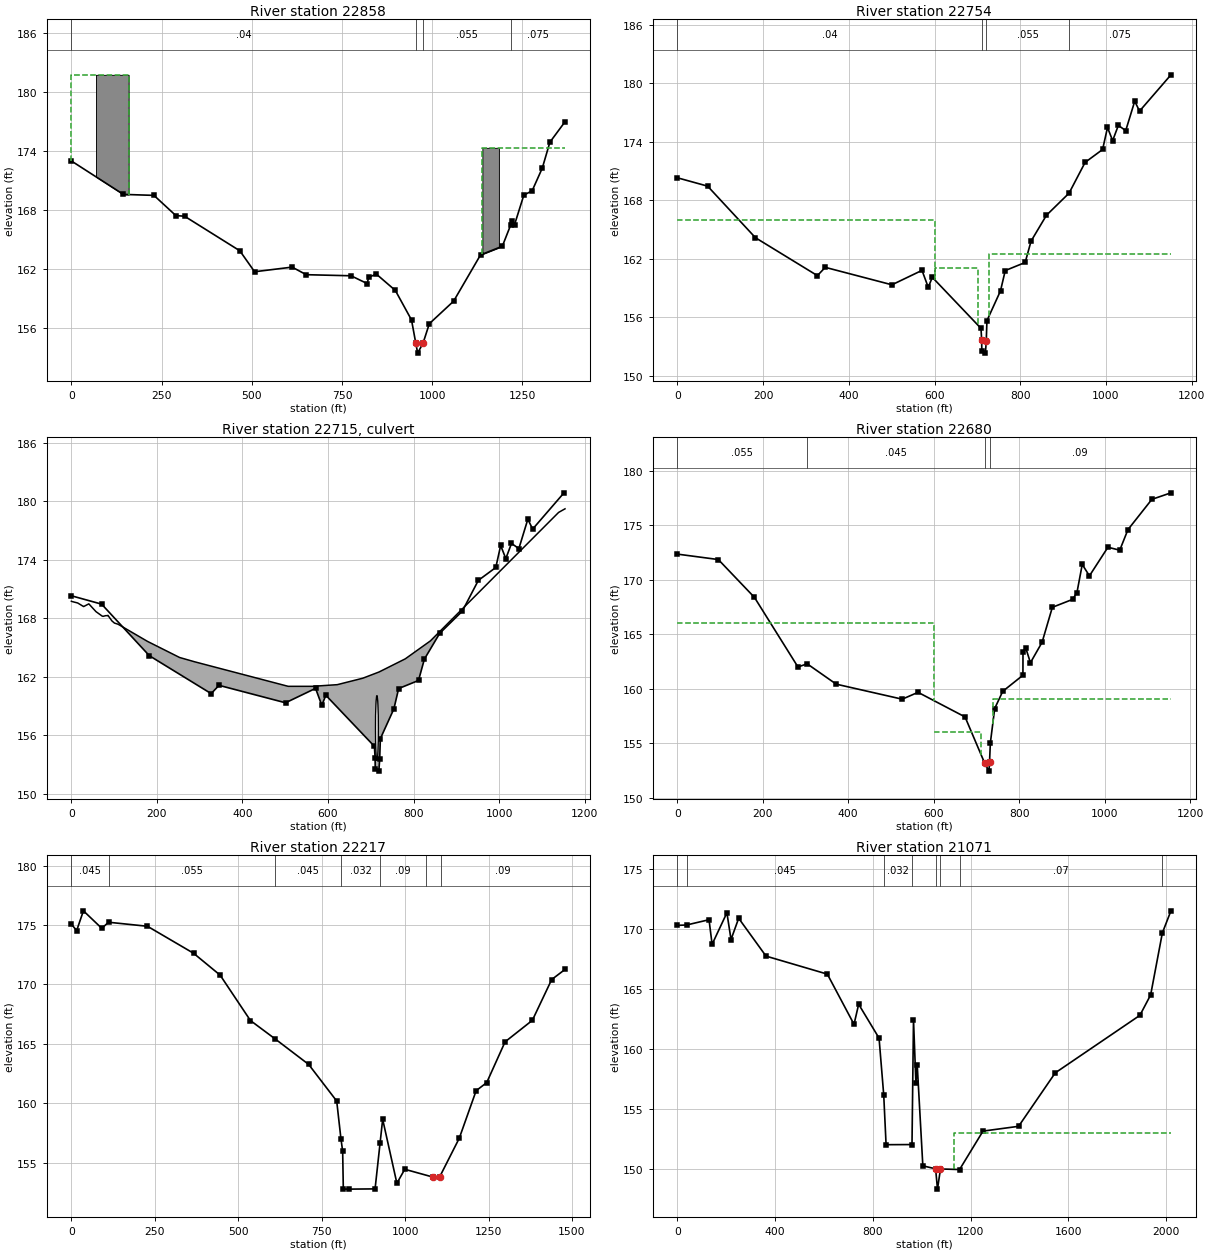
Type RM Length L Ch R = 1 ,22858   ,106.79,104.46,90.53
XS GIS Cut Line= 6
 2282256.0105428  720348.6425921 2282101.5231599  720384.2935266
 2281702.2326932  720377.1633397 2281415.8581894  720391.4957188
 2281223.2333227  720387.3581073 2280896.5215729  720351.0193211
#Sta/Elev= 30
       0  172.97  144.08  169.57  228.86  169.47   289.5  167.42  313.79  167.35
   466.8  163.84  507.77  161.71   611.8  162.18  650.89  161.41  775.04   161.3
  819.59  160.51  824.01  161.15  845.15  161.47  897.74  159.81  942.58  156.81
   954.4  154.45  959.66  153.44  974.69  154.47  991.91  156.43 1059.24  158.72
 1133.77  163.42 1194.21   164.3 1217.13  166.44 1221.32  166.89 1227.94  166.48
  1253.8   169.5 1276.72  169.93 1305.02  172.25 1325.94  174.87 1367.87  176.95
#Mann= 4 ,-1 , 0
       0     .04       0   954.4     .05       0  974.69    .055       0
 1217.13    .075       0
#XS Ineff= 2 , 0
       0  158.73  181.72 1138.96       0   174.3
Permanent Ineff=
       F       F
#Block Obstruct= 2 ,-1
   68.23  158.73 181.719 1138.96 1184.74 174.301
Bank Sta=954.4,974.69
XS Rating Curve= 0 ,0
Exp/Cntr=0.5,0.3

Type RM Length L Ch R = 1 ,22754   ,67.46,73.55,69.4
BEGIN DESCRIPTION:
Surveyed Section
END DESCRIPTION:
XS GIS Cut Line= 6
 2281965.3584905  720258.8010239    2281371.4052     720287.4371
    2281244.6726      720297.154  2281152.026288  720295.0642431
  2280965.529732  720295.0642431 2280815.2963952  720289.8837833
#Sta/Elev= 30
       0  170.32   70.79  169.46  182.33  164.17  326.83  160.28  345.17  161.13
  500.69  159.34  570.84  160.82  585.43  159.08  594.89  160.11 708.433  154.87
 709.965  153.71 710.343  152.59  718.78  152.33 720.696  153.53 722.315  155.66
 753.953  158.72 765.027   160.8  811.49  161.63  825.23  163.82  861.08  166.47
  913.85  168.74  951.36   171.9  992.12  173.22 1003.53  175.48 1015.55  174.13
 1028.84  175.69 1046.07  175.16 1067.03  178.17 1078.32  177.16 1151.52  180.88
#Mann= 4 ,-1 , 0
       0     .04       0 709.965     .05       0 720.696    .055       0
  913.85    .075       0
#XS Ineff= 3 ,-1
       0     601     166     601  700.94  161.03  727.61    1200   162.5
Permanent Ineff=
       F       F       F
Bank Sta=709.965,720.696
XS Rating Curve= 0 ,0
Exp/Cntr=0.5,0.3

Type RM Length L Ch R = 2 ,22715   ,,,
BEGIN DESCRIPTION:
Radio Tower Rd
END DESCRIPTION:
Bridge Culvert--1,0,-1,-1, 0
Deck Dist Width WeirC Skew NumUp NumDn MinLoCord MaxHiCord MaxSubmerge Is_Ogee
26.26,20.43,2.6,0, 30, 31, , , 0.95, 0, 1,1,,
       0     .56    1.44    14.8   28.31   28.67   40.85   57.18   57.61   71.83
   74.12   80.52    84.2   85.54   94.85  100.66  109.22  177.98  252.93  287.94
 506.825 563.792 621.562 681.093 719.177 780.571 839.248 1138.95 1152.28 1153.91
  169.76  169.75  169.73  169.58  169.22  169.21  169.49  168.71  168.69  168.24
  168.21  168.28  168.28  168.31  167.74  167.52   167.4  165.64  163.99  163.55
  161.03  161.03   161.2  161.86   162.5  163.85  165.69  178.87   179.2  179.24
                                                                                
                                                                                
                                                                                
       0     .56    1.44    14.8   28.31   28.67   40.85   57.18   57.61   71.83
   74.12   80.52    84.2   85.54   94.85  100.66  109.22  177.98  252.93  287.94
 506.825 563.792 621.562 681.093 719.177 780.571 839.248 1138.95 1152.28 1153.91
 1155.28
  169.76  169.75  169.73  169.58  169.22  169.21  169.49  168.71  168.69  168.24
  168.21  168.28  168.28  168.31  167.74  167.52   167.4  165.64  163.99  163.55
  161.03  161.03   161.2  161.86   162.5  163.85  165.69  178.87   179.2  179.24
  179.24
                                                                                
                                                                                
                                                                                
        
BR Coef=-1 , 0 , 0 ,, 0 ,,,0.8,-1,,0,
WSPro=,,,, 1 ,,,, 0 ,,,, 0 ,,,,-1 ,-1 ,-1 , 0 , 0 , 0 , 0 , 0
Culvert=1,6.67,,45,0.027,0.7,1,2,2,153.4142,714.27,153.4767,724.79,Culvert #1  , 0 ,16.38
Culvert Bottom n=0.027
BC Design=,, 0 ,, 0 ,,,,,,
BC Use User HTab Curves=0
BC User HTab FreeFlow(D)= 0

Type RM Length L Ch R = 1 ,22680   ,371.65,463.11,424
BEGIN DESCRIPTION:
Surveyed Section
END DESCRIPTION:
XS GIS Cut Line= 6
 2281967.1630008  720187.6103011    2281370.9693     720221.4193
    2281248.1679      720221.661    2281160.9871      720236.987
 2281127.8508085  720231.1719045 2280815.2963952  720232.8987245
#Sta/Elev= 30
       0  172.37   96.04  171.87  180.63  168.39  282.42     162  303.95  162.29
  371.97  160.42  526.34  159.04  563.45  159.67 673.447  157.41 719.166  153.18
  729.42  152.43 730.759   153.3 732.696  155.03 742.799  158.18 761.624  159.76
 808.881  161.24  809.07  163.41  815.65  163.73  826.45  162.39  853.74  164.27
  877.73  167.48  925.11  168.21  935.35  168.84  947.72  171.42  964.51  170.37
 1007.83     173  1035.5  172.73 1054.68  174.62 1110.63   177.4 1155.28     178
#Mann= 4 ,-1 , 0
       0    .055       0  303.95    .045       0 719.166     .05       0
 730.759     .09       0
#XS Ineff= 3 ,-1
       0     601     166     601  711.45     156  738.12    1200  159.08
Permanent Ineff=
       F       F       F
Bank Sta=719.166,730.759
XS Rating Curve= 0 ,0
Exp/Cntr=0.5,0.3

Type RM Length L Ch R = 1 ,22217   ,980.05,1145.76,957.17
XS GIS Cut Line= 6
 2282302.1217143  719841.6116104 2281663.3818025  719849.5085215
 2281549.3999198  719851.2355197 2281264.7951088  719839.9267193
 2281066.8911012  719783.3827171 2280831.2910921  719792.8067175
#Sta/Elev= 30
       0  175.07   15.94  174.53   36.17  176.19   91.08  174.72  111.53  175.23
  228.09  174.89  366.29  172.62  445.82  170.78  536.67  166.96  610.92  165.41
  711.09  163.27  795.13  160.19   807.8  157.02     813  155.97  814.93  152.79
  830.52  152.78   910.1   152.8  925.11  156.66  932.87  158.65  975.47  153.27
  999.03  154.45 1082.64   153.8 1103.47   153.8 1162.36  157.06 1212.95  161.06
 1244.61  161.74 1299.66  165.17  1381.4  166.98 1439.31  170.41 1479.22  171.26
#Mann= 7 ,-1 , 0
       0    .045       0  111.53    .055       0  610.92    .045       0
   807.8    .032       0  925.11     .09       0  1063.5     .05       0
 1107.85     .09       0
#XS Ineff= 2 , 0
       0  932.87  158.65               0
Permanent Ineff=
       F       F
Bank Sta=1082.64,1103.47
XS Rating Curve= 0 ,0
Exp/Cntr=0.3,0.1

Type RM Length L Ch R = 1 ,21071   ,559.46,639.68,642.37
XS GIS Cut Line= 6
 2282610.5423607  718758.6797442 2282017.4586045   718846.637081
 2281723.4297932  718911.9768168 2281414.3225813  718884.3330824
 2281086.6653271  718929.7745994 2280613.6908257  718993.9070801
#Sta/Elev= 30
       0  170.32   37.96  170.35  129.85  170.79  142.42  168.74  202.96  171.37
  219.82  169.14  251.08  170.91  362.93  167.76  613.77  166.26  722.91  162.08
  741.88  163.75  825.34  160.93  844.43   156.2  854.05  152.06  960.04  152.07
   966.2  162.47  976.08  157.17  981.52  158.67  1004.4   150.3 1056.62  150.05
 1064.31  148.36 1076.56  150.04 1154.58  149.99 1250.43  153.19 1396.08  153.59
 1546.02  158.04 1892.26  162.83 1936.23  164.53 1984.07  169.69 2019.21  171.53
#Mann= 8 ,-1 , 0
       0    .035       0   37.96    .045       0  844.43    .032       0
  960.04     .09       0 1056.62     .05       0 1076.56     .09       0
 1154.58     .07       0 1984.07    .045       0
#XS Ineff= 2 , 0
       0  981.52  158.67    1130       0     153
Permanent Ineff=
       F       F
Bank Sta=1056.62,1076.56
XS Rating Curve= 0 ,0
Exp/Cntr=0.3,0.1

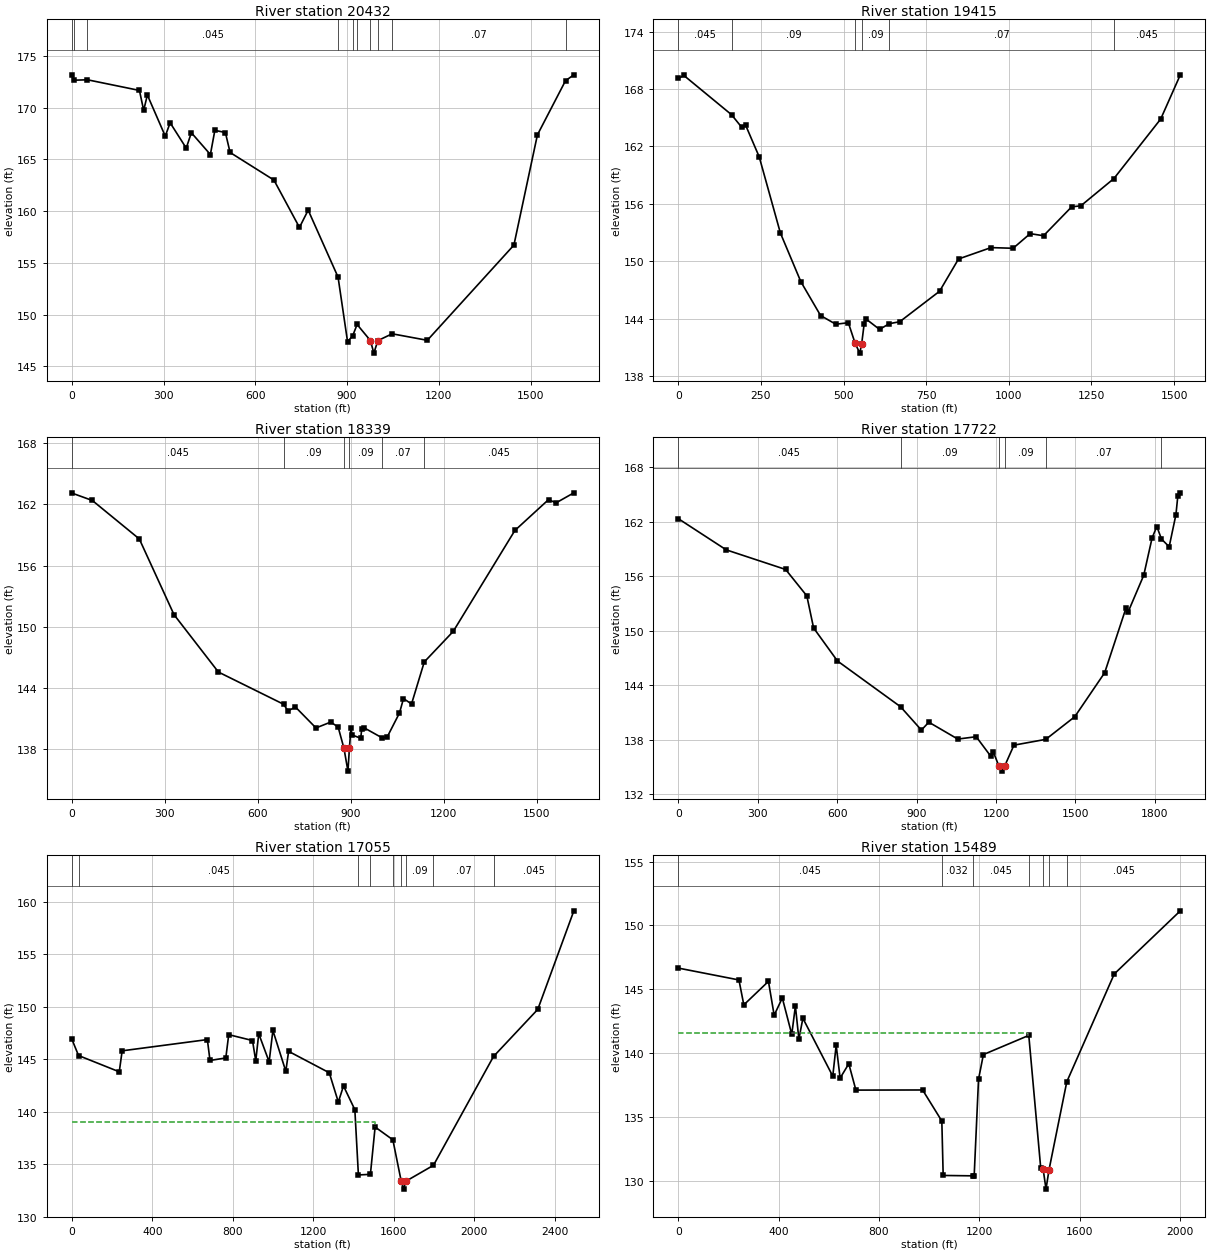
Type RM Length L Ch R = 1 ,20432   ,922.23,1016.86,938.77
XS GIS Cut Line= 6
 2282620.5946278  718615.4349387  2282384.366352  718610.4088052
 2281982.2756699  718532.5037355  2281831.491664  718454.5986659
 2281730.9689935  718364.1282624 2281080.0847017  718135.4391869
#Sta/Elev= 30
       0  173.13    6.57  172.67   51.37  172.71  221.21  171.68  235.06  169.75
   247.1  171.24  305.61  167.26  321.58  168.55   374.2   166.1  390.91  167.59
  453.15  165.48  467.76  167.82  502.21  167.61  517.52  165.68  660.89  163.01
  744.32  158.43  772.85   160.1  870.57  153.62  901.51  147.39     918  147.92
  932.78  149.04   976.2  147.49  987.58  146.27 1000.62  147.48 1047.34  148.14
 1162.32  147.51  1445.4  156.72 1522.22  167.38  1614.1  172.62 1641.35  173.19
#Mann= 10 ,-1 , 0
       0    .045       0    6.57    .035       0   51.37    .045       0
  870.57     .07       0     918    .032       0  932.78     .09       0
   976.2     .05       0 1000.62     .09       0 1047.34     .07       0
  1614.1    .045       0
Bank Sta=976.2,1000.62
XS Rating Curve= 0 ,0
Exp/Cntr=0.3,0.1

Type RM Length L Ch R = 1 ,19415   ,1018.33,1076.44,866.15
XS GIS Cut Line= 5
 2282223.5300792  717607.6951665 2281811.3871299  717502.1463625
   2281640.49859  717416.7020925 2281313.1158208  717285.7489848
 2280792.7377413  717463.2936245
#Sta/Elev= 30
       0  169.11   17.25  169.42  161.31  165.32  191.64  164.02  203.58  164.25
  245.05  160.91  308.99  152.96   370.9  147.87  430.64  144.33  476.71  143.42
  514.56  143.58  535.04  141.44  549.14   140.4  554.78  141.32  562.52  143.47
  568.08  143.97  608.99  142.88  638.59  143.48  670.04  143.68  790.65  146.87
  847.94  150.24  946.15  151.43  1013.1  151.36 1064.75  152.89 1105.17  152.67
 1190.15  155.69  1218.1   155.8 1318.13  158.65 1459.61  164.87 1518.94  169.49
#Mann= 6 ,-1 , 0
       0    .045       0  161.31     .09       0  535.04     .05       0
  554.78     .09       0  638.59     .07       0 1318.13    .045       0
Bank Sta=535.04,554.78
XS Rating Curve= 0 ,0
Exp/Cntr=0.3,0.1

Type RM Length L Ch R = 1 ,18339   ,498.73,616.55,659.65
XS GIS Cut Line= 6
 2282196.5923186  716541.1227848 2281965.6410185  716543.1484728
 2281381.6527133  716562.2593929 2281190.6596393  716630.1121955
 2280929.1061469  716914.8321874 2280827.5964328  717105.1997933
#Sta/Elev= 30
       0  163.11   66.36  162.38     218  158.61  329.98  151.19   473.2  145.57
   683.8  142.41  697.75  141.76  721.92  142.14  788.18  140.09  835.95  140.67
  859.79  140.17  878.56  138.08  891.28  135.86  896.06  138.09  901.04  140.13
   904.4  139.41  932.49  139.08  935.78  139.96  942.65  140.12  999.93  139.15
 1017.42  139.17 1057.69  141.56 1070.61  142.97 1096.53  142.44 1137.67  146.56
 1231.06  149.55 1430.04  159.44 1538.88  162.47  1562.6  162.14 1620.38  163.13
#Mann= 6 ,-1 , 0
       0    .045       0   683.8     .09       0  878.56     .05       0
  896.06     .09       0  999.93     .07       0 1137.67    .045       0
Bank Sta=878.56,896.06
XS Rating Curve= 0 ,0
Exp/Cntr=0.3,0.1

Type RM Length L Ch R = 1 ,17722   ,550.88,666.69,595.63
XS GIS Cut Line= 6
 2282161.7336271  716408.0259626 2281899.3444667  716152.6295104
 2281685.7337917  716155.1425772 2281213.2772402  716099.8551084
  2280715.690021  716082.2636411 2280374.4334429  716094.2977387
#Sta/Elev= 30
       0  162.35  181.22  158.91  405.48  156.75   485.6  153.84  511.11  150.31
  601.29  146.67  839.53  141.63  918.22  139.06  946.24  139.93 1055.72  138.07
 1125.19  138.33 1180.44  136.17  1189.9  136.65 1210.34  135.14 1222.16  134.54
 1233.27  135.14 1267.73   137.4 1388.03  138.04 1497.36  140.53 1610.37  145.38
 1690.53  152.47 1698.71  152.06 1757.86  156.11 1789.36  160.22 1807.28  161.48
 1824.86   160.1 1853.86  159.25 1879.42  162.79 1886.62  164.86 1895.96  165.19
#Mann= 6 ,-1 , 0
       0    .045       0  839.53     .09       0 1210.34     .05       0
 1233.27     .09       0 1388.03     .07       0 1824.86    .045       0
Bank Sta=1210.34,1233.27
XS Rating Curve= 0 ,0
Exp/Cntr=0.3,0.1

Type RM Length L Ch R = 1 ,17055   ,1378.63,1566.51,1380.16
XS GIS Cut Line= 6
 2282670.8559631  715607.2940228 2281424.3748484  715589.7025554
 2281142.9113708   715519.336686 2280954.4313636  715521.8497528
 2280549.8276147  715464.0492172 2280190.4590675  715441.4316164
#Sta/Elev= 30
       0  146.92   33.67  145.34  235.91  143.79  250.28  145.79  673.56  146.86
   686.6  144.87  765.19  145.11  779.58  147.33  897.76  146.77  913.96  144.83
  928.79  147.42  980.43  144.74  999.03  147.73 1063.24  143.84 1077.17  145.74
 1279.06   143.7 1324.07  140.91 1349.83  142.44 1406.17  140.18 1423.86  133.96
 1483.47  134.02 1506.83  138.53 1594.95  137.31 1636.65  133.35 1648.67  132.61
 1658.55  133.35 1796.72  134.88 2095.01  145.25 2314.93  149.74 2494.06  159.13
#Mann= 9 ,-1 , 0
       0    .035       0   33.67    .045       0 1423.86    .032       0
 1483.47    .045       0 1594.95     .09       0 1636.65     .05       0
 1658.55     .09       0 1796.72     .07       0 2095.01    .045       0
#XS Ineff= 2 , 0
       0 1506.83     139               0
Permanent Ineff=
       F       F
Bank Sta=1636.65,1658.55
XS Rating Curve= 0 ,0
Exp/Cntr=0.3,0.1

Type RM Length L Ch R = 1 ,15489   ,1005.44,1075.68,908.65
XS GIS Cut Line= 6
 2282356.3640103  714274.3795954 2282032.5370051  714285.4209051
 2281467.0969833  714290.4470387 2280974.5358977  714240.1857034
 2280818.7257583  714147.2022331 2280383.9652082  714134.6368993
#Sta/Elev= 30
       0  146.66  241.95  145.73  261.38  143.78  359.55  145.62  382.27  142.97
  414.78  144.32  452.45  141.47  466.91  143.69  480.81   141.1  496.78  142.73
  615.85   138.2  629.43  140.62  645.18  138.05  679.73  139.17  708.03  137.11
  973.95  137.12 1050.52  134.69 1055.89  130.43 1173.18   130.4 1179.43   130.4
 1196.82  137.96 1216.13  139.89 1397.09  141.39 1444.52  131.04 1454.53   130.9
 1465.67  129.36 1477.81  130.88 1548.56  137.76 1737.76   146.2 2000.98  151.14
#Mann= 7 ,-1 , 0
       0    .045       0 1050.52    .032       0 1173.18    .045       0
 1397.09     .09       0 1454.53     .05       0 1477.81     .09       0
 1548.56    .045       0
#XS Ineff= 2 , 0
       0 1395.87  141.59               0
Permanent Ineff=
       F       F
Bank Sta=1454.53,1477.81
XS Rating Curve= 0 ,0
Exp/Cntr=0.3,0.1

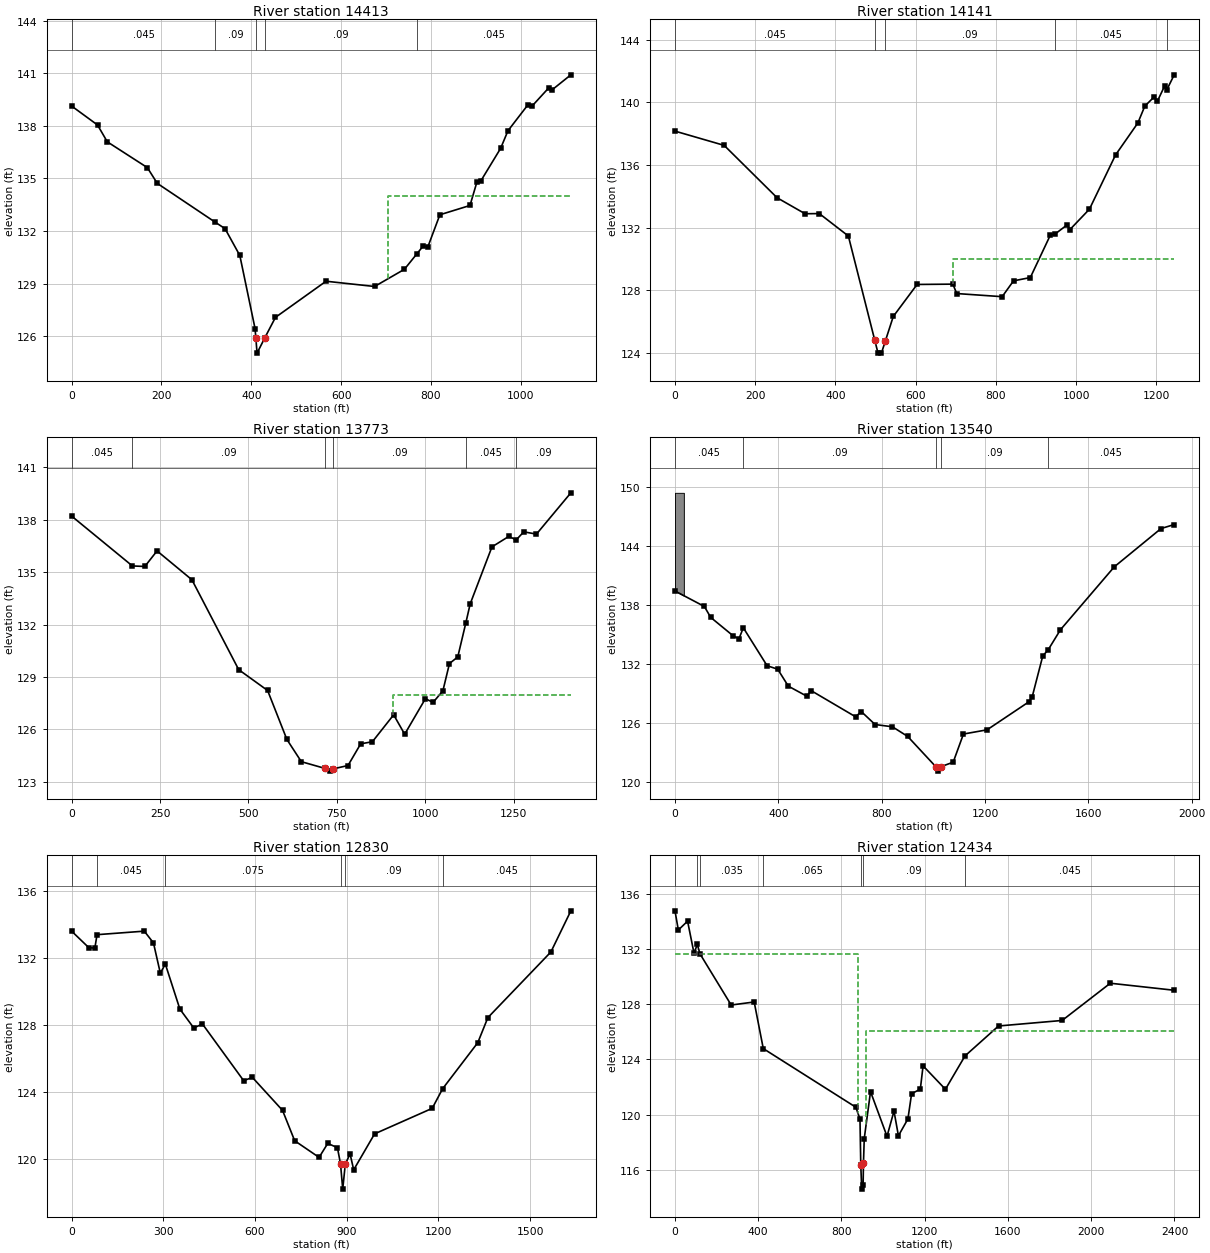
Type RM Length L Ch R = 1 ,14413   ,282.01,272.07,248.87
XS GIS Cut Line= 2
 2281888.1686577  713686.5453991 2280863.6316607  713256.3530689
#Sta/Elev= 30
       0  139.13   57.64  138.05   79.39  137.09  168.46  135.62  190.66  134.72
  319.91   132.5  341.41  132.14  374.35  130.61  408.27  126.44     410  125.91
  412.73  125.04  429.91  125.91  453.72  127.08  566.29  129.14  674.31  128.84
  740.66  129.82  768.39   130.7  782.79  131.16  792.47  131.07  819.64  132.93
  886.65  133.46  902.35  134.82  910.33  134.84  954.91  136.72  971.17  137.72
 1015.94  139.21 1024.16  139.11 1062.48  140.18 1068.79  140.04 1111.19  140.91
#Mann= 5 ,-1 , 0
       0    .045       0  319.91     .09       0     410     .05       0
  429.91     .09       0  768.39    .045       0
#XS Ineff= 2 , 0
       0                     705       0     134
Permanent Ineff=
       F       F
Bank Sta=410,429.91
XS Rating Curve= 0 ,0
Exp/Cntr=0.3,0.1

Type RM Length L Ch R = 1 ,14141   ,307.77,368.48,323.8
XS GIS Cut Line= 3
 2282014.7381104  713524.1664271 2281725.8060644  713314.7391723
 2280874.5230565  713062.6508101
#Sta/Elev= 30
       0  138.16  122.67  137.25  254.58  133.91  324.36  132.89  359.88   132.9
  432.28  131.47  498.23  124.81  506.02  124.02  514.71     124  524.59  124.78
   544.3  126.34  603.66  128.38  692.88   128.4  702.47   127.8  815.71   127.6
  844.06  128.61  885.97  128.82  935.91  131.53  947.82   131.6   977.7  132.18
  984.67  131.88 1033.27  133.18 1098.44  136.64 1154.06  138.68 1171.33  139.75
 1195.27  140.36 1202.61  140.06 1220.79  141.04 1226.13  140.79 1244.67  141.75
#Mann= 5 ,-1 , 0
       0    .045       0  498.23     .05       0  524.59     .09       0
  947.82    .045       0 1226.13     .09       0
#XS Ineff= 2 , 0
       0                  692.88       0     130
Permanent Ineff=
       F       T
Bank Sta=498.23,524.59
XS Rating Curve= 0 ,0
Exp/Cntr=0.3,0.1

Type RM Length L Ch R = 1 ,13773   ,195.55,232.09,232.21
XS GIS Cut Line= 4
 2282165.9911277  713334.1305848 2282030.4357952  713170.2343424
 2281787.8585844  713021.9288439 2280926.8798702  712713.6053854
#Sta/Elev= 30
       0   138.2  171.78  135.35  206.94  135.32  241.53  136.21  340.06  134.56
  472.42  129.42  554.12  128.23  608.63  125.43   649.5  124.16  715.49  123.78
  730.36  123.62  739.48  123.75  781.38  123.94  817.28  125.18  850.36   125.3
  910.49  126.84  941.66  125.73 1000.24  127.76 1021.95  127.55 1049.68  128.21
 1068.26  129.77 1091.79  130.15  1114.4  132.08 1126.85  133.18 1188.41  136.44
 1236.16  137.04 1256.97  136.84 1278.42   137.3 1314.24  137.17 1411.53  139.53
#Mann= 6 ,-1 , 0
       0    .045       0  171.78     .09       0  715.49     .05       0
  739.48     .09       0  1114.4    .045       0 1256.97     .09       0
#XS Ineff= 2 , 0
       0                     909       0     128
Permanent Ineff=
       F       F
Bank Sta=715.49,739.48
XS Rating Curve= 0 ,0
Exp/Cntr=0.3,0.1

Type RM Length L Ch R = 1 ,13540   ,679.32,710.39,703.02
XS GIS Cut Line= 4
 2282507.2109896  713286.4697459 2281930.7424027  712878.1343146
 2281203.6284192  712539.7079904  2280821.317908  712356.9046383
#Sta/Elev= 30
       0  139.44  113.79  137.86  138.24  136.75  225.17  134.87  247.52  134.56
  264.52  135.69  356.63  131.82  397.59  131.47  438.71  129.74  510.82  128.71
  526.65  129.29  698.96  126.62  721.14  127.15  774.47  125.83  841.49   125.6
  900.57  124.62 1010.27  121.51 1017.74  121.08 1027.72  121.52 1076.82  121.99
 1116.49  124.86 1207.97  125.29 1370.19  128.15 1382.87  128.68  1423.5  132.82
 1444.33  133.44 1492.01  135.49 1700.27   141.9 1881.12   145.8 1932.22  146.21
#Mann= 5 ,-1 , 0
       0    .045       0  264.52     .09       0 1010.27     .05       0
 1027.72     .09       0 1444.33    .045       0
#Block Obstruct= 1 ,-1
       0   34.38 149.443
Bank Sta=1010.27,1027.72
XS Rating Curve= 0 ,0
Exp/Cntr=0.3,0.1

Type RM Length L Ch R = 1 ,12830   ,371.43,396.14,321.11
XS GIS Cut Line= 4
 2282796.6669341  712834.6513767 2282516.4758769   712475.214364
 2281851.3758926   712098.796075 2281438.1648386  712095.9658623
#Sta/Elev= 30
       0  133.59   56.03  132.61   75.93  132.58   83.13  133.38  237.67  133.59
  267.72  132.89  290.14  131.09  306.55  131.63  354.09  128.95  399.42  127.83
  428.09  128.06  562.67  124.69  591.48  124.88  689.92  122.92  729.71  121.11
  809.48  120.12  837.84  120.95  869.51   120.7  879.59  119.74  886.88  118.23
  895.27  119.72  910.88  120.33  922.75  119.38  991.06  121.52 1179.59  123.04
 1213.79  124.21 1328.69  126.95 1361.62  128.44 1567.84  132.35 1633.19   134.8
#Mann= 6 ,-1 , 0
       0    .035       0   83.13    .045       0  306.55    .075       0
  879.59     .05       0  895.27     .09       0 1213.79    .045       0
#XS Ineff= 2 , 0
       0     640            1140       0
Permanent Ineff=
       F       F
Bank Sta=879.59,895.27
XS Rating Curve= 0 ,0
Exp/Cntr=0.5,0.3

Type RM Length L Ch R = 1 ,12434   ,323.73,231.28,215.82
BEGIN DESCRIPTION:
Surveyed Section
END DESCRIPTION:
XS GIS Cut Line= 6
 2283023.5107045  712448.0314537 2282696.5148288  712125.9724638
    2282347.8988     711972.4338     2282305.137     711891.2942
 2282175.0527452  711893.4397277 2280865.7785235  711667.2906893
#Sta/Elev= 30
       0  134.78   16.15  133.39   60.58  134.03   91.34  131.72  107.46  132.34
  120.17  131.66  270.06  127.95  380.63  128.17  424.33  124.79 868.902  120.54
  888.92  119.68 892.741  116.35  897.29   114.6 903.865  114.87 905.704   116.5
 909.462  118.27 939.608  121.67 1018.83  118.43 1052.35  120.26 1073.59  118.47
 1119.24  119.69  1136.9  121.52 1178.88  121.85 1192.08  123.54 1299.39  121.84
 1393.63  124.26 1554.61  126.43 1860.26  126.83 2091.67  129.53 2398.68  129.02
#Mann= 7 ,-1 , 0
       0    .085       0  107.46     .04       0  120.17    .035       0
  424.33    .065       0 892.741     .05       0 905.704     .09       0
 1393.63    .045       0
#XS Ineff= 2 , 0
       0  879.67  131.62  918.33       0  126.09
Permanent Ineff=
       F       F
Bank Sta=892.741,905.704
XS Rating Curve= 0 ,0
Exp/Cntr=0.5,0.3

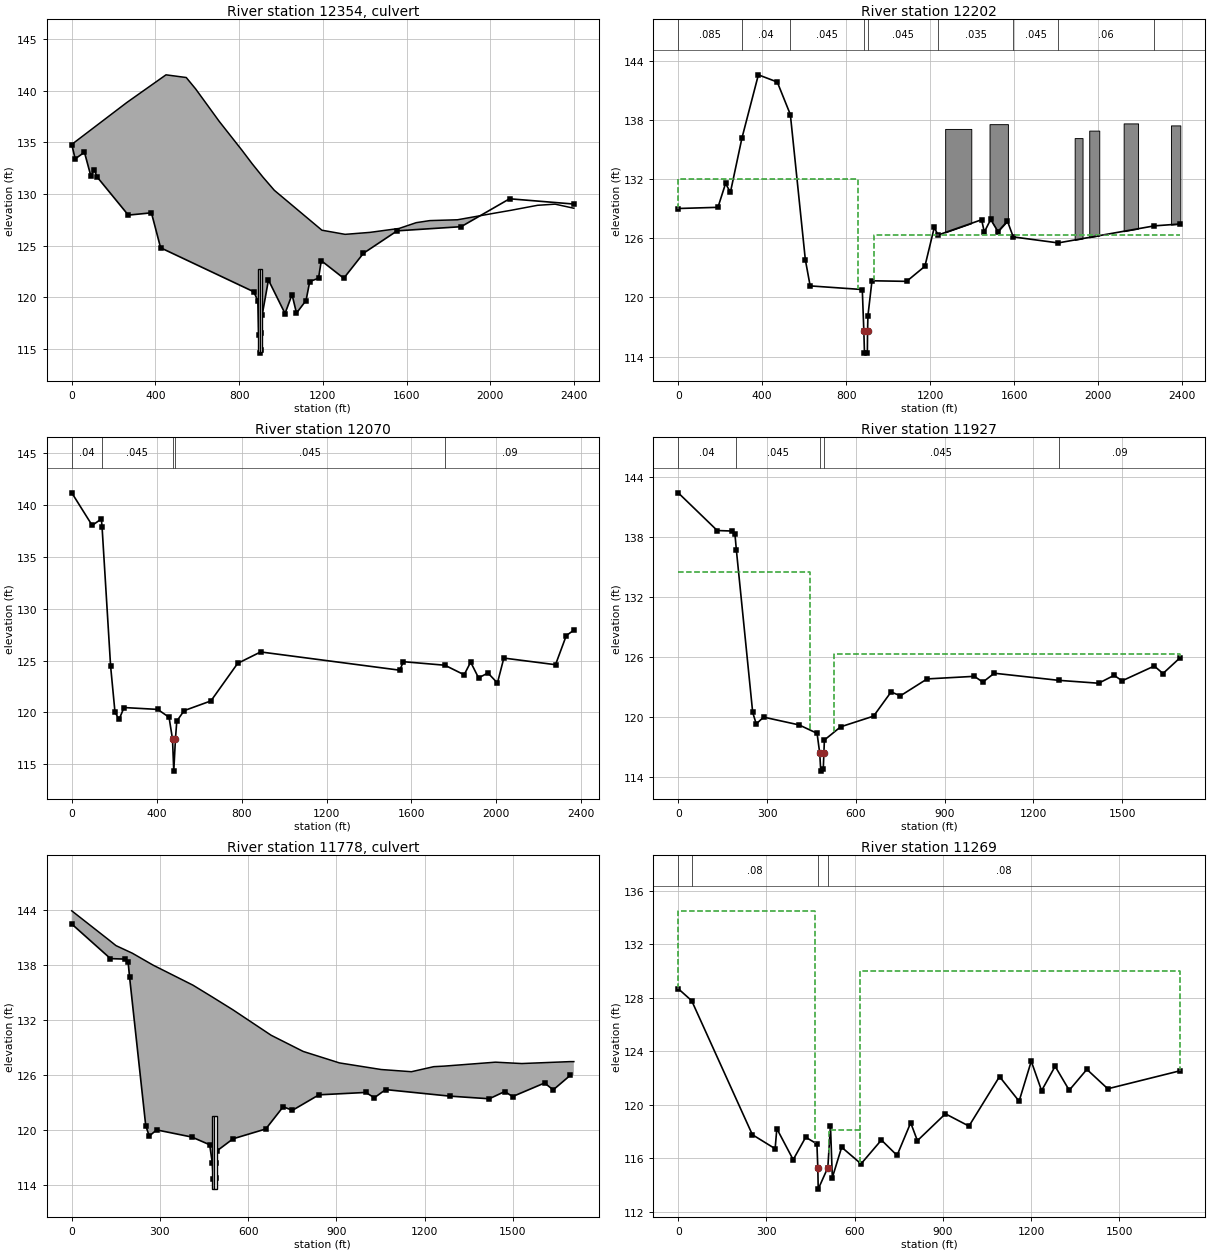
Type RM Length L Ch R = 2 ,12354   ,,,
BEGIN DESCRIPTION:
HWY 42 @ I-95 & Flowers Rd.
END DESCRIPTION:
Bridge Culvert--1,0,-1,-1, 0
Deck Dist Width WeirC Skew NumUp NumDn MinLoCord MaxHiCord MaxSubmerge Is_Ogee
52.197,46.102,2.6,0, 24, 23, , , 0.98, 0, 1,1,,
       0  262.79  450.13  546.95  591.67  652.05  704.03 812.916 862.225 913.527
 967.746 1195.07    1306 1424.26 1563.54 1645.59 1710.72 1842.85 2025.57 2096.77
 2225.53 2309.15 2397.63 2398.68
  134.79  138.84  141.52  141.26  140.16  138.48  137.03  134.23  132.91  131.62
  130.35  126.49  126.09  126.28  126.66  127.22  127.42   127.5  128.16  128.41
   128.9  129.01  128.62  128.62
                                                                                
                                                                                
                                
       0  262.79  450.13  546.95  591.67  652.05  704.03 812.916 862.225 913.527
 967.746 1195.07    1306 1424.26 1563.54 1645.59 1710.72 1842.85 2025.57 2096.77
 2225.53 2309.15 2397.63
  134.79  138.84  141.52  141.26  140.16  138.48  137.03  134.23  132.91  131.62
  130.35  126.49  126.09  126.28  126.66  127.22  127.42   127.5  128.16  128.41
   128.9  129.01  128.62
                                                                                
                                                                                
                        
BR Coef=-1 , 0 , 0 ,, 0 ,,,0.8,-1,,0,
WSPro=,,,, 1 ,,,, 0 ,,,, 0 ,,,,-1 ,-1 ,-1 , 0 , 0 , 0 , 0 , 0
Culvert=2,8,9,101,0.012,0.4,1,8,1,114.7062,894.17,114.745,889.17,Culvert #1  , 0 ,33.36
Culvert Bottom n=0.012
Culvert=2,8,9,101,0.012,0.4,1,8,1,114.7062,903.83,114.745,898.83,Culvert #2  , 0 ,33.36
Culvert Bottom n=0.012
Culvert Bottom Depth=8
Culvert Depth Blocked=3
BC Design=,, 0 ,, 0 ,,,,,,
BC Use User HTab Curves=0
BC User HTab FreeFlow(D)= 0

Type RM Length L Ch R = 1 ,12202   ,24.55,132.36,214.68
BEGIN DESCRIPTION:
Surveyed Section
END DESCRIPTION:
XS GIS Cut Line= 6
 2283056.1417582  712216.4630876 2282530.9962535  711724.0244366
     2282438.568     711705.6621    2282367.3391     711698.9273
 2282235.5887001     711679.3471 2280871.6276466  711545.0728571
#Sta/Elev= 30
       0  129.02  189.25  129.14  225.53  131.56   248.6  130.66  303.57  136.17
  381.82  142.58  471.85  141.85  534.17  138.55  605.56  123.83  628.53  121.17
 876.961   120.8  884.29   116.6 887.319  114.38 901.074  114.35 902.005   116.6
 903.868  118.15 923.081  121.69 1088.15  121.63 1175.22  123.16 1219.92   127.1
 1237.71  126.33 1445.39  127.88 1458.33  126.63 1488.55  127.91 1523.13  126.68
 1568.51  127.74 1596.06  126.14 1810.16  125.53  2268.5  127.26 2392.17  127.45
#Mann= 9 ,-1 , 0
       0    .085       0  303.57     .04       0  534.17    .045       0
  884.29     .05       0 902.005    .045       0 1237.71    .035       0
 1596.06    .045       0 1810.16     .06       0  2268.5     .09       0
#XS Ineff= 2 , 0
       0  854.67     132  933.33       0 126.335
Permanent Ineff=
       F       F
#Block Obstruct= 6 ,-1
 1271.77 1396.24 137.092 1483.13 1570.75 137.576 1888.78 1926.32 136.162
  1958.2 2005.97 136.922 2122.22 2190.84 137.652 2347.57 2392.17  137.45
Bank Sta=884.29,902.005
XS Rating Curve= 0 ,0
Exp/Cntr=0.5,0.3

Type RM Length L Ch R = 1 ,12070   ,49.26,143.14,196.91
XS GIS Cut Line= 6
 2282712.8519433  711871.6820604 2282681.9145598  711734.5732018
  2282658.612839  711731.2221491 2282559.5112826  711717.2963413
 2281765.8743584  711060.0400894 2280697.3310298  711124.5154319
#Sta/Elev= 30
       0  141.17   96.12  138.03  139.41  138.65  142.85  137.83  182.98  124.45
  203.65  120.01  222.96  119.33  246.19  120.47  405.03  120.29  458.27  119.53
  474.52  117.43  480.46  114.34  488.29  117.42  494.78  119.16  529.16  120.17
  655.51  121.11  781.55  124.73  889.74  125.83 1545.24  124.07 1561.92  124.89
 1757.52  124.55  1848.4  123.63 1878.96  124.85 1916.31  123.33 1960.35   123.8
  2005.2  122.84 2035.33  125.24 2278.74   124.6  2329.6  127.41 2365.12  127.93
#Mann= 5 ,-1 , 0
       0     .04       0  142.85    .045       0  474.52     .05       0
  488.29    .045       0 1757.52     .09       0
#XS Ineff= 2 , 0
       0     427             523       0
Permanent Ineff=
       F       F
Bank Sta=474.52,488.29
XS Rating Curve= 0 ,0
Exp/Cntr=0.5,0.3

Type RM Length L Ch R = 1 ,11927   ,733.97,657.98,531.51
BEGIN DESCRIPTION:
Surveyed Section
END DESCRIPTION:
XS GIS Cut Line= 6
 2282745.1955715  711896.2913426 2282686.8364163  711722.6201218
 2282595.8382069  711711.5783867    2282529.5694      711577.741
 2282331.0043415  710854.4646881 2282125.1240715  710381.2074439
#Sta/Elev= 30
       0  142.46  131.71  138.69  180.79  138.64   191.6  138.32  196.39  136.73
  251.51   120.5  263.46  119.35  288.49  120.03   408.3  119.25 469.015  118.41
 478.028   116.4 481.399  114.63 489.842   114.8 492.011  116.42 493.651  117.74
 548.601  119.06  659.84  120.13  719.03  122.55  750.38  122.16  840.66  123.85
 1000.22  124.11 1028.84  123.53 1067.54  124.42 1284.85  123.71 1419.96  123.42
 1472.52  124.21 1499.17  123.66 1608.03  125.14 1637.38  124.39 1695.94  125.99
#Mann= 5 ,-1 , 0
       0     .04       0  196.39    .045       0 478.028     .05       0
 492.011    .045       0 1284.85     .09       0
#XS Ineff= 2 , 0
       0  443.67  134.51  526.33       0  126.37
Permanent Ineff=
       F       F
Bank Sta=478.028,492.011
XS Rating Curve= 0 ,0
Exp/Cntr=0.5,0.3

Type RM Length L Ch R = 2 ,11778   ,,,
BEGIN DESCRIPTION:
I-95 @ HWY 42
END DESCRIPTION:
Bridge Culvert--1,0,-1,-1, 0
Deck Dist Width WeirC Skew NumUp NumDn MinLoCord MaxHiCord MaxSubmerge Is_Ogee
149.7,446.32,2.6,0, 20, 20, , , 0.98, 0, 1,1,,
       0   66.82  129.34  150.34  206.14  276.18 412.142 478.063 547.814  678.18
  787.03  910.25 1051.93 1155.04 1231.04 1266.53 1441.05 1530.26 1694.71 1707.54
   143.9  142.22  140.65  140.11  139.28  137.99   135.8  134.51  133.12  130.34
  128.58  127.33  126.61  126.37  126.92  126.98  127.41  127.26  127.47  127.47
                                                                                
                                                                                
       0   66.82  129.34  150.34  206.14  276.18 412.142 478.063 547.814  678.18
  787.03  910.25 1051.93 1155.04 1231.04 1266.53 1441.05 1530.26 1694.71 1707.54
   143.9  142.22  140.65  140.11  139.28  137.99   135.8  134.51  133.12  130.34
  128.58  127.33  126.61  126.37  126.92  126.98  127.41  127.26  127.47  127.47
                                                                                
                                                                                
BR Coef=-1 , 0 , 0 ,, 0 ,,,0.8,-1,,0,
WSPro=,,,, 1 ,,,, 0 ,,,, 0 ,,,,-1 ,-1 ,-1 , 0 , 0 , 0 , 0 , 0
Multiple Barrel Culv=2,8,9,538,0.011,0.4,1,8,1,113.5757,112.828, 2,Culvert #1  , 0 ,75.9
  480.17  487.17  489.83  496.83
Culvert Bottom n=0.011
BC Design=,, 0 ,, 0 ,,,,,,
BC Use User HTab Curves=0
BC User HTab FreeFlow(D)= 0

Type RM Length L Ch R = 1 ,11269   ,97.07,110.87,119.14
BEGIN DESCRIPTION:
Surveyed Section
END DESCRIPTION:
XS GIS Cut Line= 6
 2283580.2981656   711633.090056    2283165.8712     711410.7712
 2282933.7793671  711201.2633742 2282841.1577416    711095.15616
 2282705.8762478  710859.0604285 2282478.7546436  710405.5322817
#Sta/Elev= 30
       0  128.69   45.76  127.79  252.09  117.78  329.56  116.73   335.3  118.23
  390.94  115.91  433.48  117.59 471.616  117.09  474.75  115.28 476.015  113.71
 508.776  115.32 517.731  118.45 524.099  114.57  555.82  116.84  621.77   115.6
  690.94  117.38   744.2  116.23  790.55  118.67  813.35  117.33  908.63  119.34
  988.71  118.42 1092.63  122.12 1159.26  120.28  1200.6  123.27 1235.79  121.07
 1281.77  122.89 1329.72   121.1 1389.74  122.66 1460.82  121.21 1707.54  122.56
#Mann= 4 ,-1 , 0
       0    .045       0   45.76     .08       0  474.75     .05       0
 508.776     .08       0
#XS Ineff= 3 ,-1
       0  464.25  134.51     512     617  118.12     617    1750     130
Permanent Ineff=
       F       F       F
Bank Sta=474.75,508.776
XS Rating Curve= 0 ,0
Exp/Cntr=0.5,0.3