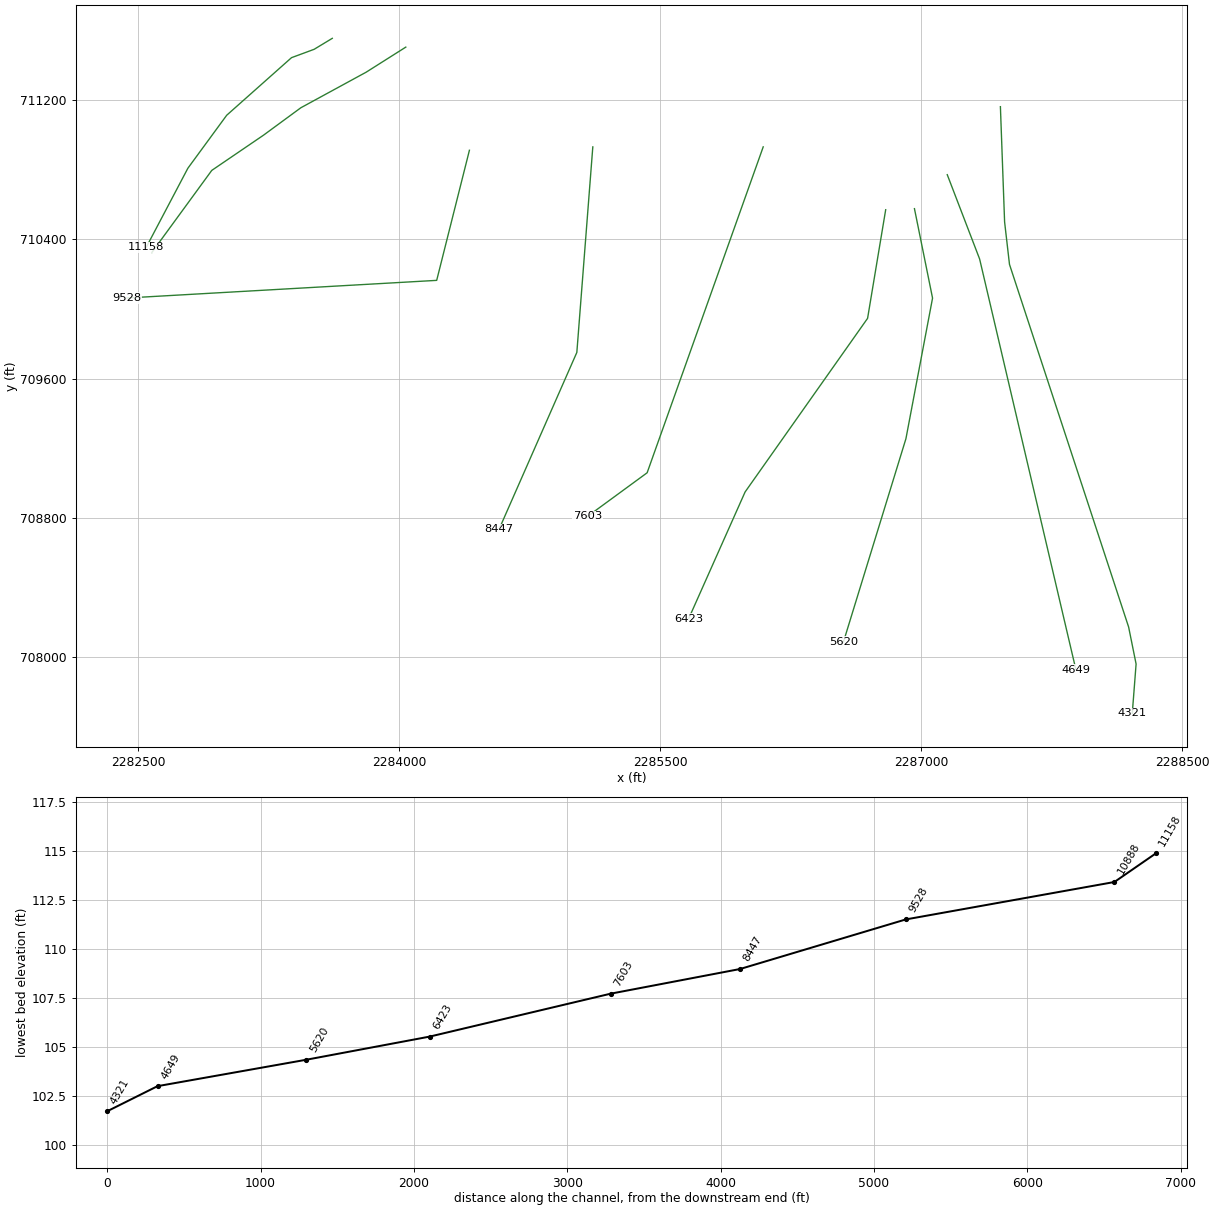
HEC-RAS study DTL_Little_Swamp_Main.prj: DTL_Little_Swamp

--- DTL_Little_Swamp_Main.g01 (geometry) --- (continued)

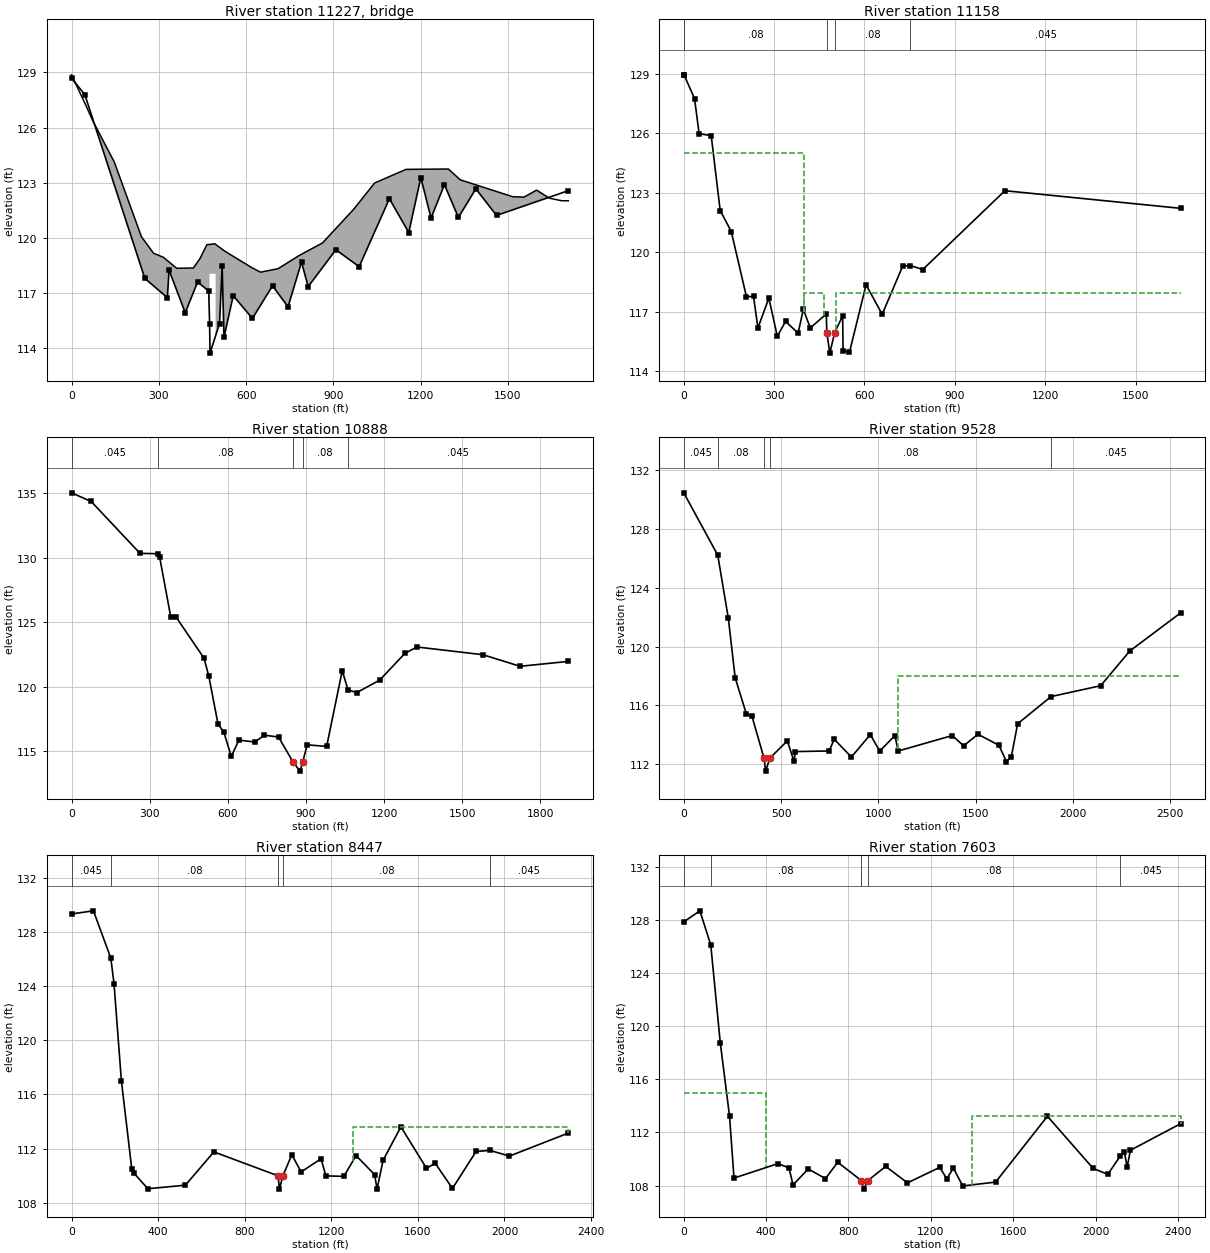
Type RM Length L Ch R = 3 ,11227   ,,,
BEGIN DESCRIPTION:
field road
END DESCRIPTION:
Bridge Culvert--1,0,-1,-1, 0
Deck Dist Width WeirC Skew NumUp NumDn MinLoCord MaxHiCord MaxSubmerge Is_Ogee
41.67,14.96,2.6,0, 34, 34, , , 0.98, 0, 1,1,,
       0   48.76    72.9   146.8  240.41   282.1  315.86  361.68  418.96 442.011
 465.236  474.25  474.25 480.867 491.958  495.25  495.25 528.217  620.49  649.73
  710.06  783.77  862.54  970.11 1041.97 1149.79 1295.17 1336.31 1516.48 1555.68
 1598.43 1642.54 1685.29 1707.54
  128.87  127.23  126.37  124.13  120.05  119.15  118.93  118.33  118.35  118.87
  119.62 119.632 119.632  119.64  119.67 119.632 119.632  119.25  118.36  118.12
  118.31  119.04  119.71  121.55  122.98  123.72  123.74  123.15  122.23  122.21
  122.59  122.15  122.01  122.01
                                                                                
               0 118.032 118.032 118.032 118.032       0
                                                                                
                                
       0   48.76    72.9   146.8  240.41   282.1  315.86  361.68  418.96 442.011
 465.236  474.25  474.25 480.867 491.958  495.25  495.25 528.217  620.49  649.73
  710.06  783.77  862.54  970.11 1041.97 1149.79 1295.17 1336.31 1516.48 1555.68
 1598.43 1642.54 1685.29 1707.54
  128.87  127.23  126.37  124.13  120.05  119.15  118.93  118.33  118.35  118.87
  119.62 119.632 119.632  119.64  119.67 119.632 119.632  119.25  118.36  118.12
  118.31  119.04  119.71  121.55  122.98  123.72  123.74  123.15  122.23  122.21
  122.59  122.15  122.01  122.01
                                                                                
               0 118.032 118.032 118.032 118.032       0
                                                                                
                                
BR Coef=-1 , 0 , 0 ,, 0 ,,,0.8,0,,0,
WSPro=,,,, 1 ,,,, 0 ,,,, 0 ,,,,-1 ,-1 ,-1 , 0 , 0 , 0 , 0 , 0
BC Design=,, 0 ,, 0 ,,,,,,
BC Use User HTab Curves=0
BC User HTab FreeFlow(D)= 0

Type RM Length L Ch R = 1 ,11158   ,270.99,270.18,234.81
BEGIN DESCRIPTION:
Surveyed Section
END DESCRIPTION:
XS GIS Cut Line= 6
 2283613.8119506  711555.6192486 2283509.3980435  711492.5164462
 2283379.4133454  711444.5110297  2283006.931541  711113.5208692
 2282783.8880726  710809.1328606 2282544.5780194  710354.7896537
#Sta/Elev= 30
       0  128.95    1.49  128.93   35.75  127.75   50.92  125.98   91.12  125.88
  120.87   122.1  157.66  121.04  208.04  117.75  231.64  117.76  246.14  116.17
  282.49  117.68  310.48  115.75  337.88   116.5  379.54  115.91  396.91  117.11
   420.1  116.17 473.277  116.88  474.83  115.94 484.967   114.9  500.81  115.93
 527.497  116.78  528.93  115.02  550.06  114.94  605.24  118.35  658.71  116.86
  727.06   119.3  752.76  119.32  793.56  119.12 1066.21   123.1 1649.46  122.21
#Mann= 5 ,-1 , 0
       0    .045       0    1.49     .08       0  474.83     .05       0
  500.81     .08       0  752.76    .045       0
#XS Ineff= 3 ,-1
       0     400     125     400  464.25  117.95  505.25    1800  117.95
Permanent Ineff=
       F       F       F
Bank Sta=474.83,500.81
XS Rating Curve= 0 ,0
Exp/Cntr=0.5,0.3

Type RM Length L Ch R = 1 ,10888   ,1122.38,1360.03,1344.5
XS GIS Cut Line= 6
 2284036.2889046  711505.1313757 2283808.4375181  711361.0488813
 2283433.1528814  711156.6527845 2283218.7045175  710999.1672673
 2282921.1888843  710796.6509687 2282576.8788978  710325.0887271
#Sta/Elev= 30
       0  135.05   75.49  134.38  262.85  130.35  331.02  130.32  338.44  130.04
  381.25  125.38  400.78  125.42  508.53  122.21  526.95  120.82  562.28   117.1
  584.71  116.46  613.32  114.59  642.56  115.85  703.48   115.7  740.13  116.23
  794.54  116.09  850.74  114.13  877.43  113.44  886.98  114.13  904.71  115.48
   979.3  115.36 1039.13  121.24 1060.93  119.77 1094.14  119.53 1182.94  120.51
 1279.94  122.59 1325.75  123.08 1578.78  122.48 1721.71  121.58 1906.77  121.96
#Mann= 5 ,-1 , 0
       0    .045       0  331.02     .08       0  850.74     .05       0
  886.98     .08       0 1060.93    .045       0
Bank Sta=850.74,886.98
XS Rating Curve= 0 ,0
Exp/Cntr=0.3,0.1

Type RM Length L Ch R = 1 ,9528    ,867.36,1080.44,959.35
XS GIS Cut Line= 3
 2284401.9677136  710912.3585897 2284213.8280587   710164.624064
 2282433.7374782  710063.3180959
#Sta/Elev= 30
       0  130.46  174.69  126.22  229.08  121.93  264.13  117.89  321.21  115.44
  349.98  115.29  412.73   112.4  420.96  111.53  442.29  112.41  532.37  113.59
  566.29  112.21  573.85  112.86  747.58   112.9  773.39   113.7  861.58  112.49
  958.99  114.01 1007.39  112.89 1085.23  113.95 1102.52   112.9  1380.3  113.95
 1438.64  113.25 1512.21  114.04 1619.92  113.29 1658.72  112.18 1684.18  112.52
 1716.33  114.75 1887.92   116.6 2143.17  117.34 2292.77   119.7 2554.01  122.29
#Mann= 5 ,-1 , 0
       0    .045       0  174.69     .08       0  412.73     .05       0
  442.29     .08       0 1887.92    .045       0
#XS Ineff= 2 , 0
       0                    1100       0     118
Permanent Ineff=
       F       F
Bank Sta=412.73,442.29
XS Rating Curve= 0 ,0
Exp/Cntr=0.3,0.1

Type RM Length L Ch R = 1 ,8447    ,830.34,844.22,732.32
XS GIS Cut Line= 3
 2285111.0964257  710931.8067528 2285019.2828001  709750.4714362
 2284572.4564886  708734.4006458
#Sta/Elev= 30
       0  129.32  101.33  129.55  181.52  126.06  196.44  124.16  230.44  116.99
  278.35   110.5  288.32  110.18  352.62  109.03  525.99  109.29  657.69  111.75
  954.46  109.98  960.29     109  976.47  109.99 1017.82  111.54 1060.58  110.27
 1152.82  111.24 1174.88  109.98 1258.14  109.94 1314.49  111.48 1399.94  110.07
 1411.58  109.01 1439.29  111.13 1521.62   113.6 1639.72  110.54 1680.19  110.91
 1759.61  109.05 1868.76  111.78 1932.75  111.86 2023.17  111.44 2294.88  113.14
#Mann= 5 ,-1 , 0
       0    .045       0  181.52     .08       0  954.46     .05       0
  976.47     .08       0 1932.75    .045       0
#XS Ineff= 2 , 0
       0                    1300       0   113.6
Permanent Ineff=
       F       F
Bank Sta=954.46,976.47
XS Rating Curve= 0 ,0
Exp/Cntr=0.3,0.1

Type RM Length L Ch R = 1 ,7603    ,1094.46,1179.69,1006.4
XS GIS Cut Line= 3
 2286090.4417659  710931.8067528 2285423.2627529  709058.8087897
 2285080.4918839  708807.8515463
#Sta/Elev= 30
       0  127.84   78.23  128.67  131.03  126.11  177.27  118.75  222.32  113.22
  243.94  108.57  457.48  109.66  511.23  109.33  530.68  108.05  604.52  109.26
  688.17  108.53  747.67  109.76  863.05  108.38  873.47  107.74  894.06  108.38
  980.83  109.45 1086.47  108.21 1243.65  109.38 1277.32  108.51 1309.46  109.32
 1355.14  107.98 1514.85  108.27  1766.3  113.22 1988.28   109.3 2059.69  108.85
 2121.11  110.25 2139.74  110.55 2154.04   109.4 2169.15  110.66  2413.1  112.66
#Mann= 5 ,-1 , 0
       0    .045       0  131.03     .08       0  863.05     .05       0
  894.06     .08       0 2121.11    .045       0
#XS Ineff= 2 , 0
       0     400     115    1400       0  113.22
Permanent Ineff=
       F       F
Bank Sta=863.05,894.06
XS Rating Curve= 0 ,0
Exp/Cntr=0.3,0.1

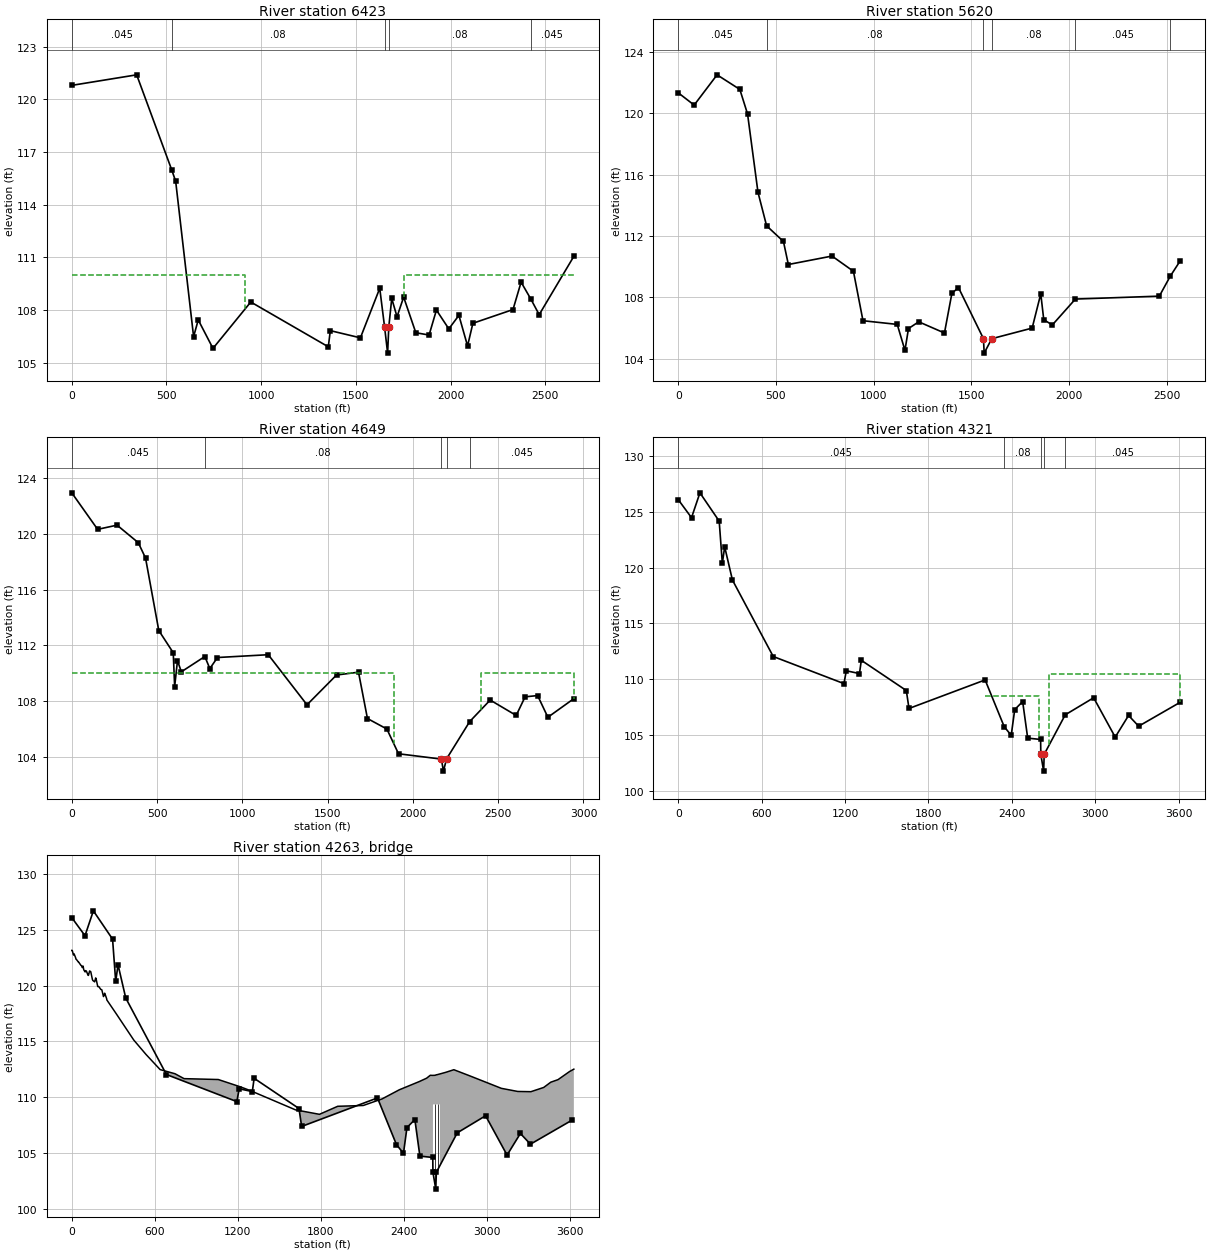
Type RM Length L Ch R = 1 ,6423    ,647.62,803.86,846.32
XS GIS Cut Line= 4
 2286794.3462292  710570.6731587 2286690.2907868  709946.3405043
 2285986.3863235   708948.632439 2285661.9781796  708220.2443422
#Sta/Elev= 30
       0  120.79  342.76  121.39  528.15  115.97  548.68  115.33  643.32  106.49
  667.87  107.44   745.7  105.82  945.29  108.46 1354.68  105.91 1365.33  106.83
 1524.21  106.42 1626.31  109.24 1651.98  107.03 1667.91  105.55 1674.02  107.03
 1689.69  108.66 1717.56  107.62 1752.56  108.74 1816.87  106.71 1886.86  106.58
 1925.63     108 1991.16  106.93 2044.31   107.7 2090.08  105.96 2118.21  107.25
 2330.03  108.03 2372.77  109.59 2424.64108.6194 2468.28  107.74 2651.33  111.06
#Mann= 5 ,-1 , 0
       0    .045       0  528.15     .08       0 1651.98     .05       0
 1674.02     .08       0 2424.64    .045       0
#XS Ineff= 2 , 0
       0     915     110    1752       0     110
Permanent Ineff=
       T       T
Bank Sta=1651.98,1674.02
XS Rating Curve= 0 ,0
Exp/Cntr=0.3,0.1

Type RM Length L Ch R = 1 ,5620    ,832.26,970.99,1008.26
XS GIS Cut Line= 4
 2286959.6107553   710576.794067 2287063.6661978  710062.6377634
 2286910.6434883  709254.6778578 2286551.6604836  708086.9077975
#Sta/Elev= 30
       0  121.32   81.45  120.52  198.67  122.49  315.15  121.54  354.63  119.94
  407.99  114.84  452.07  112.66  538.23  111.64  563.32  110.14  786.72  110.69
  896.23   109.7  945.15  106.48 1120.38  106.24 1159.86  104.55 1177.91  105.97
 1230.31  106.41 1361.92  105.68 1399.91  108.26 1433.58  108.64 1561.48  105.31
 1565.15  104.37 1604.02  105.31 1810.57     106 1854.67  108.23 1869.97  106.55
 1913.52   106.2 2031.77  107.89 2461.26  108.08 2517.23  109.38 2568.56  110.39
#Mann= 6 ,-1 , 0
       0    .045       0  452.07     .08       0 1561.48     .05       0
 1604.02     .08       0 2031.77    .045       0 2517.23    .085       0
Bank Sta=1561.48,1604.02
XS Rating Curve= 0 ,0
Exp/Cntr=0.3,0.1

Type RM Length L Ch R = 1 ,4649    ,297.31,327.85,352.46
BEGIN DESCRIPTION:
NOTE: XS is not fully extended on the right due to adjacent Contentnea Creek floodplain
END DESCRIPTION:
XS GIS Cut Line= 3
 2287148.1347334  710772.0510442 2287334.2103479  710287.2751008
 2287887.5404652  707927.0528309
#Sta/Elev= 30
       0  122.91  151.59   120.3  265.46   120.6  389.71  119.35  432.46  118.25
  510.14  113.07     595  111.48  603.13  109.06  619.76  110.91  642.57  110.12
  780.02  111.21   809.4  110.35  854.24  111.14 1152.02  111.34 1379.02  107.76
 1552.16  109.89 1681.07  110.09 1733.39  106.78 1847.33  106.03 1915.68  104.26
 2166.83  103.88 2179.11  103.02 2196.94  103.89    2333106.5626 2452.95   108.1
 2605.49     107 2657.76  108.33  2731.1  108.42 2791.26  106.87 2943.48   108.2
#Mann= 5 ,-1 , 0
       0    .045       0  780.02     .08       0 2166.83     .05       0
 2196.94     .08       0    2333    .045       0
#XS Ineff= 2 , 0
       0    1890     110    2400       0     110
Permanent Ineff=
       F       F
Bank Sta=2166.83,2196.94
XS Rating Curve= 0 ,0
Exp/Cntr=0.5,0.3

Type RM Length L Ch R = 1 ,4321    ,99.67,105.19,101.23
BEGIN DESCRIPTION:
Surveyed Section
NOTE: XS is not fully extended on the right due to adjacent Contentnea Creek floodplain
END DESCRIPTION:
XS GIS Cut Line= 6
 2287453.6106529  711162.8999836 2287477.7274958  710500.4906999
 2287505.8483559  710256.3109889 2288190.5668181  708172.2368759
 2288233.4331216  707959.8816553  2288211.516906  707676.0253586
#Sta/Elev= 30
       0  126.09   95.57  124.47  156.01   126.7  294.71  124.16  317.27  120.37
  334.14  121.86  389.88  118.88  683.59  112.02 1192.11  109.59 1209.48  110.74
 1304.14  110.49 1317.27  111.68 1641.07  108.97 1660.48  107.36 2208.19  109.92
 2345.36  105.73 2395.88  104.95 2421.18  107.26 2478.25  107.982514.542   104.7
2607.543  104.58 2608.81  103.252629.265  101.742633.338  103.25 2784.66  106.79
 2989.17  108.32 3144.23  104.79 3240.37  106.73 3313.07  105.77 3612.69  107.92
#Mann= 5 ,-1 , 0
       0    .045       0 2345.36     .08       0 2608.81     .05       0
2633.338     .08       0 2784.66    .045       0
#XS Ineff= 3 ,-1
       0 2208.19  109.92 2208.19    2599108.4542    2669    3700  110.48
Permanent Ineff=
       F       F       F
Bank Sta=2608.81,2633.338
XS Rating Curve= 0 ,0
Exp/Cntr=0.5,0.3

Type RM Length L Ch R = 3 ,4263    ,,,
BEGIN DESCRIPTION:
St. Rose Church Rd./Indian Rd. (SR 1154)
END DESCRIPTION:
Bridge Culvert--1,0,-1,-1, 0
Deck Dist Width WeirC Skew NumUp NumDn MinLoCord MaxHiCord MaxSubmerge Is_Ogee
46,24,2.6,0, 84, 84, , , 0.98, 0, 1,1,,
       0    2.85    3.87    4.29   12.09   16.73   27.38   30.28   34.25   48.74
   49.83   50.43   66.69   72.16   76.05   81.93    86.7   96.52   99.54  105.91
  117.35  119.96  121.19  128.78  137.14  148.56  149.71  152.37  165.46  172.57
  173.74   175.6  187.51  190.66  196.16  208.24     209  210.01     217  229.07
   233.9  237.51  242.47  251.91  253.16  322.24  447.89   536.2  638.26  745.58
     811  1058.2 1216.62 1287.01 1530.84 1615.86 1788.96 1920.91 2105.15 2241.03
 2365.772510.554 2563.01 2589.452606.531    2609    26092623.572    2634    2641
    2659    26592699.8382759.876 2874.84 3056.17  3102.9 3221.28 3316.46 3408.93
 3459.71 3512.24 3595.85 3626.59
  123.15  123.15  123.14  123.11  122.74  122.84  122.51  122.37  122.33  122.09
   122.1  122.09   121.8  121.77  121.61  121.74  121.41  121.22  121.34  121.29
  120.92  120.91  120.94  121.31  121.24  120.57  120.52  120.45  120.33  120.68
  120.66  120.61  119.91  119.91  119.89  119.68  119.66  119.65  119.62  119.01
  119.15  119.31  119.16  118.82  118.71  117.45  115.11  113.82  112.46  112.09
  111.65  111.57  110.92  110.59   109.3  108.85  108.45  109.17  109.24  109.83
  110.65  111.39  111.69  111.95  111.94 111.941 111.941  111.95 111.995  112.01
 112.071 112.071  112.21  112.45   111.9  111.01  110.78   110.5  110.48  110.86
  111.33  111.56  112.29   112.5
                                                                                
                                                                                
                                                                                
                                                                                
                                                                                
                                                                                
                                               0 109.341 109.341 109.341 109.341
 109.341       0
                                
       0    2.85    3.87    4.29   12.09   16.73   27.38   30.28   34.25   48.74
   49.83   50.43   66.69   72.16   76.05   81.93    86.7   96.52   99.54  105.91
  117.35  119.96  121.19  128.78  137.14  148.56  149.71  152.37  165.46  172.57
  173.74   175.6  187.51  190.66  196.16  208.24     209  210.01     217  229.07
   233.9  237.51  242.47  251.91  253.16  322.24  447.89   536.2  638.26  745.58
     811  1058.2 1216.62 1287.01 1530.84 1615.86 1788.96 1920.91 2105.15 2241.03
 2365.772510.554 2563.01 2589.45    2592    25922606.531    26172623.572    2641
    2642    26422699.8382759.876 2874.84 3056.17  3102.9 3221.28 3316.46 3408.93
 3459.71 3512.24 3595.85 3626.59
  123.15  123.15  123.14  123.11  122.74  122.84  122.51  122.37  122.33  122.09
   122.1  122.09   121.8  121.77  121.61  121.74  121.41  121.22  121.34  121.29
  120.92  120.91  120.94  121.31  121.24  120.57  120.52  120.45  120.33  120.68
  120.66  120.61  119.91  119.91  119.89  119.68  119.66  119.65  119.62  119.01
  119.15  119.31  119.16  118.82  118.71  117.45  115.11  113.82  112.46  112.09
  111.65  111.57  110.92  110.59   109.3  108.85  108.45  109.17  109.24  109.83
  110.65  111.39  111.69  111.95 111.949 111.949  111.94 111.946  111.95  112.01
 112.013 112.013  112.21  112.45   111.9  111.01  110.78   110.5  110.48  110.86
  111.33  111.56  112.29   112.5
                                                                                
                                                                                
                                                                                
                                                                                
                                                                                
                                                                                
                                       0  109.34  109.34  109.34  109.34  109.34
  109.34       0
                                
Pier Skew, UpSta & Num, DnSta & Num=  ,2625.5, 2 ,2608.5, 2 , 0 , 0 , 0 ,,
       1       1
     101 109.341
       1       1
     101  109.34
Pier Skew, UpSta & Num, DnSta & Num=  ,2642.5, 2 ,2625.5, 2 , 0 , 0 , 0 ,,
       1       1
     101 109.341
       1       1
     101  109.34
BR Coef=-1 , 0 , 0 ,, 0 ,,,0.8,0,,0,
WSPro=,,,, 1 ,,,, 0 ,,,, 0 ,,,,-1 ,-1 ,-1 , 0 , 0 , 0 , 0 , 0
BC Design=,, 0 ,, 0 ,,,,,,
BC Use User HTab Curves=0
BC User HTab FreeFlow(D)= 0