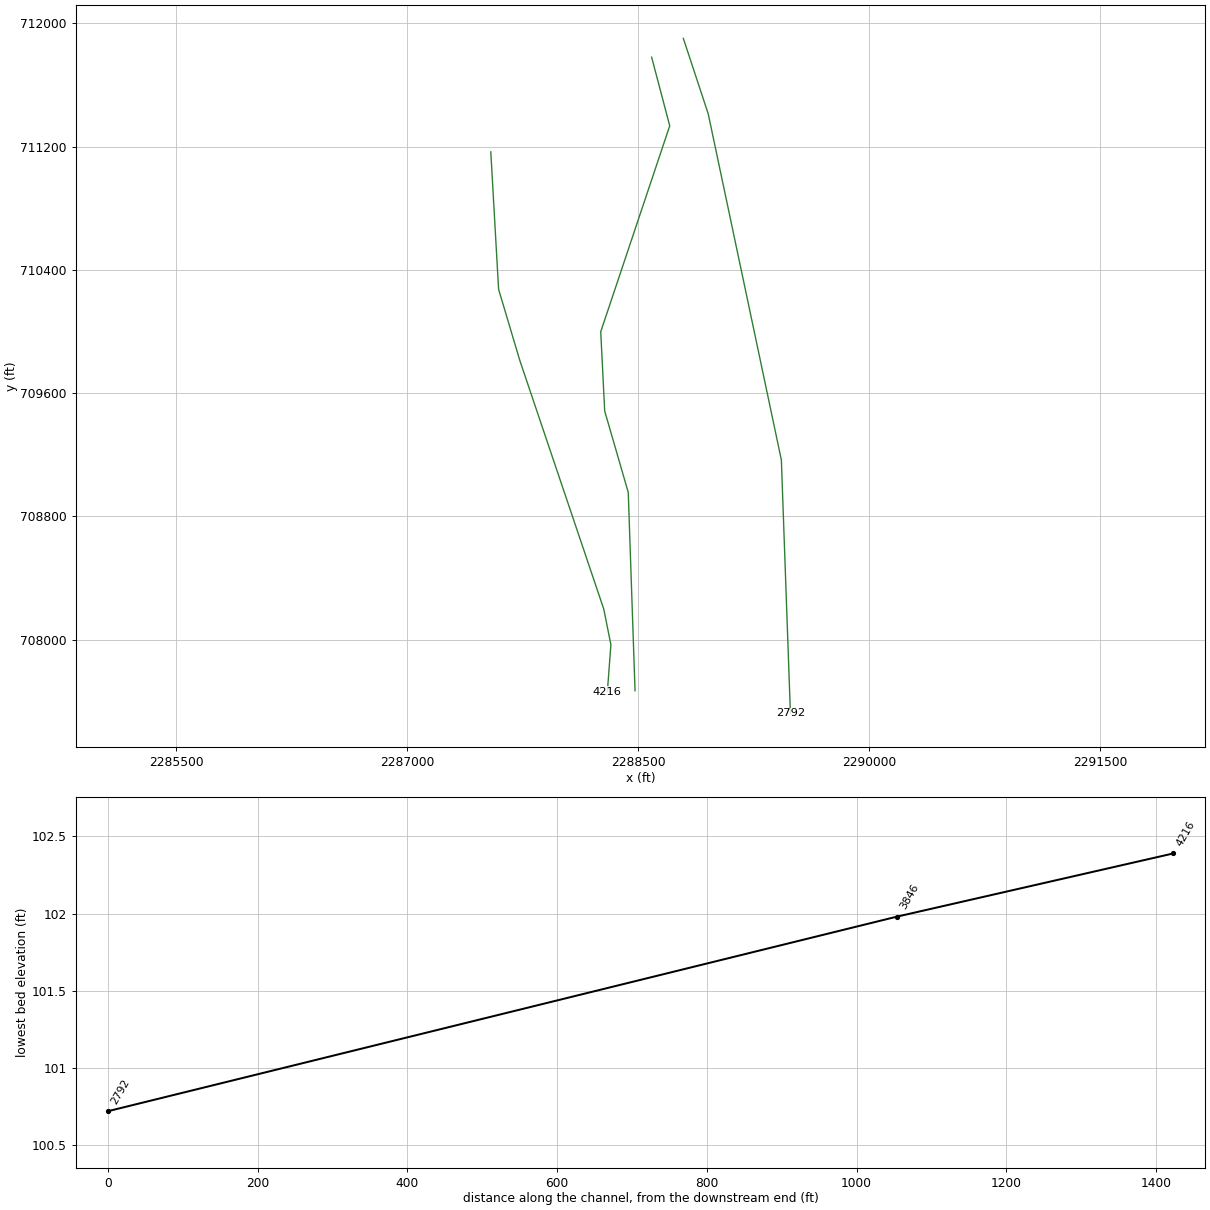
HEC-RAS study DTL_Little_Swamp_Main.prj: DTL_Little_Swamp

--- DTL_Little_Swamp_Main.g01 (geometry) --- (continued)

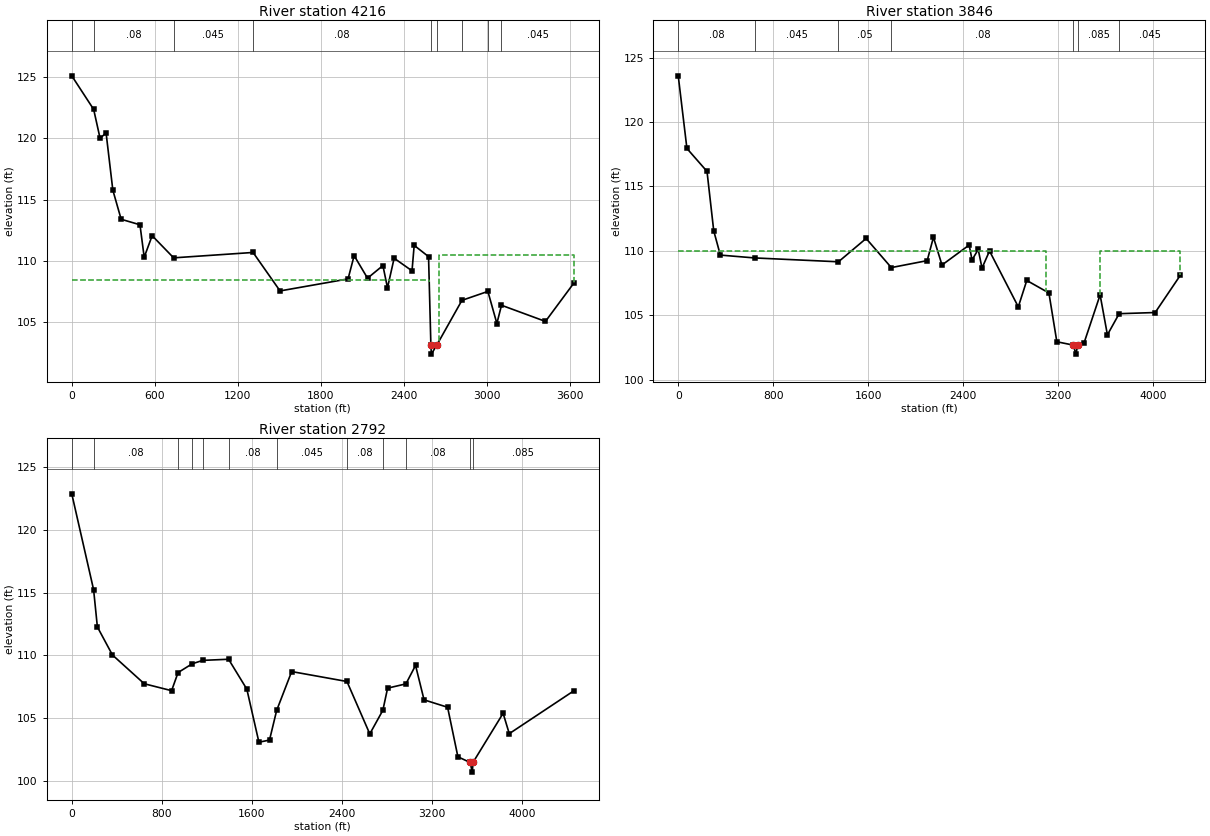
Type RM Length L Ch R = 1 ,4216    ,404.7,369.65,301.97
BEGIN DESCRIPTION:
Surveyed Section
END DESCRIPTION:
XS GIS Cut Line= 6
 2287543.5510635  711166.1745131 2287594.1835227  710274.0498282
 2287732.5372401  709810.0790781 2288276.7849051  708198.1929378
 2288323.3616564  707966.6163511 2288300.4597317  707662.2713133
#Sta/Elev= 30
       0  125.11  158.12  122.37  204.64     120  247.74  120.46  296.61  115.78
  356.64   113.4  492.66  112.95  523.13   110.3  580.63  112.06  735.84  110.25
 1309.56  110.69 1504.45  107.55 1995.65  108.53 2039.66  110.43 2136.32  108.59
 2247.48  109.62 2280.46   107.8 2328.49  110.22 2457.72  109.192473.236  111.27
2577.097  110.35 2593.82  103.17 2597.46  102.39 2638.77  103.17 2818.22  106.78
 3005.72  107.51  3070.6  104.89    3104  106.38 3421.45  105.06 3626.59  108.19
#Mann= 9 ,-1 , 0
       0    .045       0  158.12     .08       0  735.84    .045       0
 1309.56     .08       0 2593.82     .05       0 2638.77    .085       0
 2818.22    .045       0 3005.72    .085       0    3104    .045       0
#XS Ineff= 2 , 0
       0    2582  108.44    2652       0  110.48
Permanent Ineff=
       F       F
Bank Sta=2593.82,2638.77
XS Rating Curve= 0 ,0
Exp/Cntr=0.5,0.3

Type RM Length L Ch R = 1 ,3846    ,1012.42,1053.59,1024.78
XS GIS Cut Line= 6
 2288587.7723834  711780.7767446 2288705.2938242  711335.1746148
 2288257.2729642  709998.2471831 2288283.0140455  709483.8758271
 2288435.9738557  708955.3654381  2288480.044396  707667.5263158
#Sta/Elev= 30
       0  123.59   73.06  117.95   242.2  116.17  298.94  111.55  354.45  109.67
  642.13  109.45  1348.9  109.15 1581.92  110.96 1794.02   108.7 2096.09  109.24
 2148.58  111.05 2220.67   108.9 2449.46  110.45 2473.73  109.29 2525.66  110.11
 2557.55  108.66 2620.76  109.99  2863.2  105.65 2934.45   107.7 3120.89  106.73
 3187.68  102.94  3326.8  102.68 3347.82  101.98 3364.34  102.69 3417.54  102.87
 3551.94  106.58 3613.43  103.48 3712.32  105.12 4015.55  105.21  4227.2   108.1
#Mann= 7 ,-1 , 0
       0     .08       0  642.13    .045       0  1348.9     .05       0
 1794.02     .08       0  3326.8     .05       0 3364.34    .085       0
 3712.32    .045       0
#XS Ineff= 2 , 0
       0    3100     110    3551       0     110
Permanent Ineff=
       T       T
Bank Sta=3326.8,3364.34
XS Rating Curve= 0 ,0
Exp/Cntr=0.3,0.1

Type RM Length L Ch R = 1 ,2792    ,2497.48,2792.34,2301.56
XS GIS Cut Line= 4
 2288793.4349048  711903.1949121  2288955.026886   711413.522242
  2289430.009376  709165.9246863 2289488.7700964  707520.6245148
#Sta/Elev= 30
       0  122.86  193.98  115.23  227.43  112.27  361.15  110.04  643.89  107.75
  886.56   107.2  944.02  108.64 1069.77  109.34 1163.41  109.61 1392.62   109.7
 1554.87  107.32 1662.11   103.1 1756.16  103.27 1819.81  105.63  1953.1  108.72
 2444.11  107.93 2646.87  103.76 2762.94  105.64 2805.02   107.4 2967.62  107.74
 3053.25  109.21 3128.89  106.47 3337.93  105.88 3429.44  101.94 3537.52  101.49
 3557.37  100.72 3563.43  101.49 3831.03   105.4 3885.69  103.78 4459.23  107.19
#Mann= 12 ,-1 , 0
       0    .045       0  193.98     .08       0  944.02    .045       0
 1069.77     .08       0 1163.41    .045       0 1392.62     .08       0
 1819.81    .045       0 2444.11     .08       0 2762.94    .045       0
 2967.62     .08       0 3537.52     .05       0 3563.43    .085       0
#XS Ineff= 2 , 0
       0 3079.43  108.04               0
Permanent Ineff=
       F       F
Bank Sta=3537.52,3563.43
XS Rating Curve= 0 ,0
Exp/Cntr=0.3,0.1

Chan Stop Cuts=-1
Use User Specified Reach Order=0
User Specified Reach Order=Little Swamp    ,Main