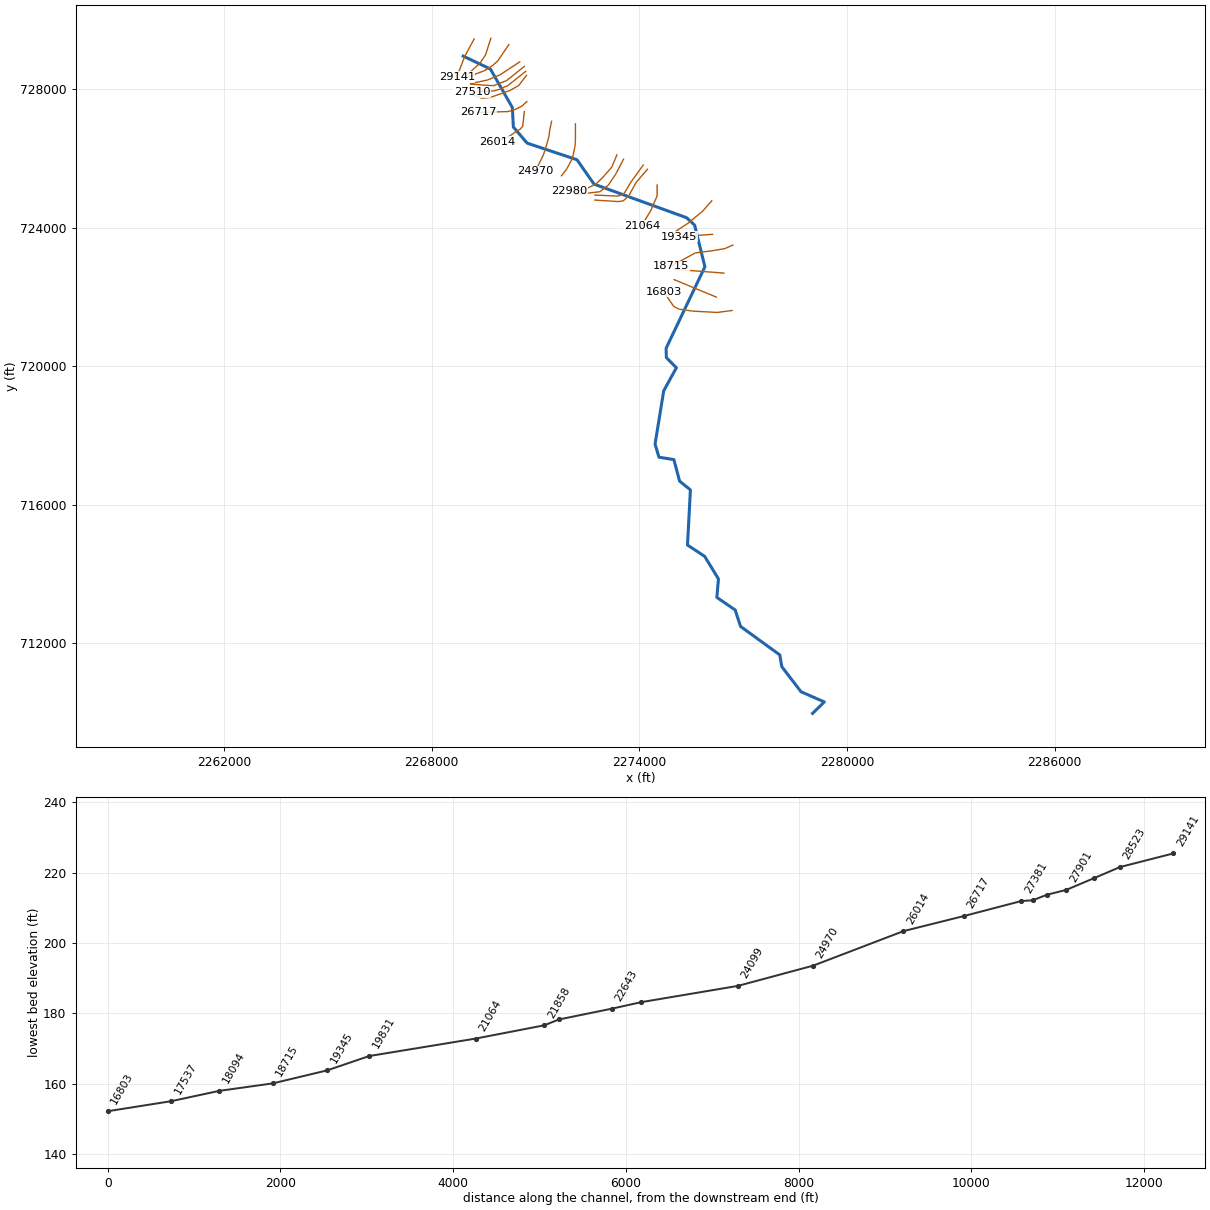
--- DTL_Marsh_Swamp.prj (project) ---

Proj Title=DTL_Marsh_Swamp
Current Plan=p02
Default Exp/Contr=0.3,0.1
English Units
Geom File=g01
Flow File=f01
Flow File=f02
Plan File=p02
Plan File=p03
Y Axis Title=Elevation
X Axis Title(PF)=Main Channel Distance
X Axis Title(XS)=Station
BEGIN DESCRIPTION:
END DESCRIPTION:
DSS Export Rating Curves= 0
DSS Export Rating Curve Sorted= 0
DSS Export Volume Flow Curves= 0
DXF Filename=DTL_Marsh_Swamp_Main.
DXF OffsetX= 0
DXF OffsetY= 0
DXF ScaleX= 1
DXF ScaleY= 10

--- DTL_Marsh_Swamp.p02 (plan) ---

Plan Title=DTL_Marsh_Swamp
Program Version=4.00
Short Identifier=Multi-Profile
Geom File=g01
Flow File=f01
Subcritical Flow
K Sum by GR= 0
Std Step Tol= 0.01
Critical Tol= 0.01
Num of Std Step Trials= 20
Max Error Tol= 0.3
Flow Tol Ratio= 0.001
Split Flow NTrial= 30
Split Flow Tol= 0.02
Split Flow Ratio= 0.02
Log Output Level= 0
Friction Slope Method= 1
Unsteady Friction Slope Method= 2
Unsteady Bridges Friction Slope Method= 1
Parabolic Critical Depth
Global Vel Dist= 0 , 0 , 0
Global Log Level= 0
CheckData=True
Encroach Param=-1 ,10,10, 2
Encroach River=Marsh Swamp
Encroach Reach=Main
Encroach Node=29141
       1  547.92  603.14
Encroach Node=28523
       1     550  784.35
Encroach Node=28219
       1     700 1006.67
Encroach Node=27901
       1  661.43 1036.74
Encroach Node=27679
       1  676.05 1141.47
Encroach Node=27510
       1     880     945
Encroach Node=27381
       1     875     930
Encroach Node=26717
       1     460     515
Encroach Node=26014
       1     620     675
Encroach Node=24970
       1     845     895
Encroach Node=24099
       1     965    1025
Encroach Node=22980
       1    1060    1100
Encroach Node=22643
       1     923    1020
Encroach Node=22026
       1     940     998
Encroach Node=21858
       1     917     950
Encroach Node=21064
       1     596     635
Encroach Node=19831
       1     775     895
Encroach Node=19345
       1     330     450
Encroach Node=18715
       1     880    1000
Encroach Node=18094
       1     498     618
Encroach Node=17537
       1     585     700
Encroach Node=16803
       1    1335    1450
Encroach Node=15956
       1     502     617
Encroach Node=15358
       1     465     565
Encroach Node=14688
       1     670     760
Encroach Node=13368
       1 1001.12 1072.97
Encroach Node=13145
       1  988.89 1032.81
Encroach Node=12355
       1     585     735
Encroach Node=10397
       1     850    1190
Encroach Node=8732
       1    1446    1785
Encroach Node=6463
       1     680    1050
Encroach Node=4955
       1     325     580
Encroach Node=4184
       1  651.02  723.23
Encroach Node=4094
       1  686.86   752.1
Encroach Node=3169
       1     790     925
Encroach Node=2334
       1    1158    1310
Encroach Node=1656
       1    1065    1220
Encroach Node=1001
       1 1600.63 1727.57
Encroach Node=900
       1 1561.56 1605.16
Encroach Node=528
       1     366     455
Computation Interval=1HOUR
Output Interval=1HOUR
Run HTab= 0
Run UNet= 0
Run PostProcess= 0
Run WQNet= 0
UNET Theta= 1
UNET Theta Warmup= 1
UNET ZTol= 0.02
UNET ZSATol= 0.05
UNET MxIter= 20
UNET MaxInSteps= 0
UNET DtIC= 0
UNET DtMin= 0
UNET MaxCRTS= 20
UNET WFStab= 2
UNET SFStab= 1
UNET WFX= 1
UNET SFX= 1
UNET DSS MLevel= 4
UNET DZMax Abort= 100
UNET Convert EG Bridges=-1
UNET Use Existing IB Tables=-1
UNET Froude Reduction=False
UNET Froude Limit= 1
UNET Froude Power= 10
UNET Time Slicing=0,0, 5
Instantaneous Interval=1HOUR
Write IC File= 0
Echo Input=False
Echo Output=False
Write Detailed= 0
Detailed Automatic Start=False, 10
WQ ULTIMATE=-1
WQ Max Comp Step=1HOUR
WQ Output Interval=15MIN
WQ Output Selected Increments= 0
WQ Output face flow=0
WQ Output face velocity=0
WQ Output face area=0
WQ Output face dispersion=0
WQ Output cell volume=0
WQ Output cell surface area=0
WQ Output cell continuity=0
WQ Output face conc=0
WQ Output face dconc_dx=0
WQ Output face courant=0
WQ Output face peclet=0
WQ Output face adv mass=0
WQ Output face disp mass=0
WQ Output cell mass=0
WQ Output cell source sink temp=0
WQ Output cell source sink nsm=0
WQ Output MaxMinRange=-1
WQ Daily Max Min Mean=-1
WQ Daily Range=0
WQ Daily Time=0
WQ Create Restart=0
WQ Fixed Restart=0
WQ System Summary=False
Sorting and Armoring Iterations= 10
XS Update Threshold= 0.02
Hydraulics Update Threshold= 0.02
Energy Slope Method= 1
Volume Change Method= 0
XS Weighting Method= 0
Number of US Weighted Cross Sections= 1
Number of DS Weighted Cross Sections= 1
Upstream XS Weight=0.25
Main XS Weight=0.5
Downstream XS Weight=0.25
Number of DS XS's Weighted with US Boundary= 1
Upstream Boundary Weight= 1
Weight of XSs Associated with US Boundary= 0
Number of US XS's Weighted with DS Boundary= 1
Downstream Boundary Weight= 0.5
Weight of XSs Associated with DS Boundary= 0.5
Sediment Output Level= 4
Mass or Volume Output= 0
Output Increment Type= 1
Profile and TS Output Increment= 10
XS Output Flag= 0
XS Output Increment= 10
Disregard all LS=0
Disregard all Conn=0
Disregard all Breaches=0
Disregard all Pumps=0

--- DTL_Marsh_Swamp.p03 (plan) ---

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Plan Title=DTL_Marsh_Swamp_Future
Short Identifier=Future
Geom File=g01
Flow File=f02

--- DTL_Marsh_Swamp.f01 (steady flow) ---

Flow Title=DTL_Marsh_Swamp
Program Version=4.00
Number of Profiles= 6
Profile Names=100-yr,FW,10-yr,25-yr,50-yr,500-yr
River Rch & RM=Marsh Swamp,Main            ,29141
     540     540     220     330     420     880
River Rch & RM=Marsh Swamp,Main            ,21064
     580     580     240     350     460     950
River Rch & RM=Marsh Swamp,Main            ,19831
    1020    1020     440     630     810    1620
River Rch & RM=Marsh Swamp,Main            ,10397
    1680    1680     750    1070    1350    2600
River Rch & RM=Marsh Swamp,Main            ,3169
    1710    1710     770    1090    1380    2650
Boundary for River Rch & Prof#=Marsh Swamp,Main            , 1
Up Type= 0
Dn Type= 3
Dn Slope=3.897849E-03
Boundary for River Rch & Prof#=Marsh Swamp,Main            , 2
Up Type= 0
Dn Type= 3
Dn Slope=3.897849E-03
Boundary for River Rch & Prof#=Marsh Swamp,Main            , 3
Up Type= 0
Dn Type= 3
Dn Slope=3.897849E-03
Boundary for River Rch & Prof#=Marsh Swamp,Main            , 4
Up Type= 0
Dn Type= 3
Dn Slope=3.897849E-03
Boundary for River Rch & Prof#=Marsh Swamp,Main            , 5
Up Type= 0
Dn Type= 3
Dn Slope=3.897849E-03
Boundary for River Rch & Prof#=Marsh Swamp,Main            , 6
Up Type= 0
Dn Type= 3
Dn Slope=3.897849E-03
DSS Import GetInterval= 0
DSS Import GetPeak= 0
DSS Import FillOption= 0

--- DTL_Marsh_Swamp.f02 (steady flow) ---

Flow Title=DTL_Marsh_Swamp_Future_Conditions
Program Version=4.00
Number of Profiles= 3
Profile Names=100-yr-10%,100-yr-20%,100-yr-35%
River Rch & RM=Marsh Swamp,Main            ,29141
     950    1210    1480
River Rch & RM=Marsh Swamp,Main            ,21064
    1020    1300    1590
River Rch & RM=Marsh Swamp,Main            ,19831
    1750    2250    2740
River Rch & RM=Marsh Swamp,Main            ,10397
    2840    3640    4450
River Rch & RM=Marsh Swamp,Main            ,3169
    2890    3710    4530
Boundary for River Rch & Prof#=Marsh Swamp,Main            , 1
Up Type= 0
Dn Type= 3
Dn Slope=3.897849E-03
Boundary for River Rch & Prof#=Marsh Swamp,Main            , 2
Up Type= 0
Dn Type= 3
Dn Slope=3.897849E-03
Boundary for River Rch & Prof#=Marsh Swamp,Main            , 3
Up Type= 0
Dn Type= 3
Dn Slope=3.897849E-03
DSS Import GetInterval= 0
DSS Import GetPeak= 0
DSS Import FillOption= 0

--- DTL_Marsh_Swamp.g01 (geometry) ---

Geom Title=DTL_Marsh_Swamp
Program Version=4.00

River Reach=Marsh Swamp     ,Main
Reach XY= 30
2268910.52998632728959.297890678 2269694.8652858728585.992047861
2270329.12713046727474.4253513222270358.65693374 726909.45892629
2270757.05699174726444.7269388442272195.59865841725966.601938844
2272688.59803459725261.4240365622275362.26532504724290.560272172
 2275595.5986584  724077.01860552275891.43199174  722873.8936055
2274771.64032507720521.8102721872274777.89032505720250.976938844
2275068.51532505719957.2269388442274702.89032504719293.685272172
2274451.84865841717750.9769388592274565.39032504717372.851938859
2274995.59865841717304.101938859 2275161.2236584716681.185272187
 2275472.6819917716429.1019388442275389.34865837714835.351938859
 2275886.2236584714507.2269388442276283.09865838  713858.2686055
2276237.26532507713322.8519388592276766.43199171712959.310272172
 2276922.6819917712483.2686055152278053.93199168711663.476938844
 2278113.3069917711321.8102721872278669.55699174710596.810272187
2279341.43199171710303.0602721872279001.84865838709972.851938859

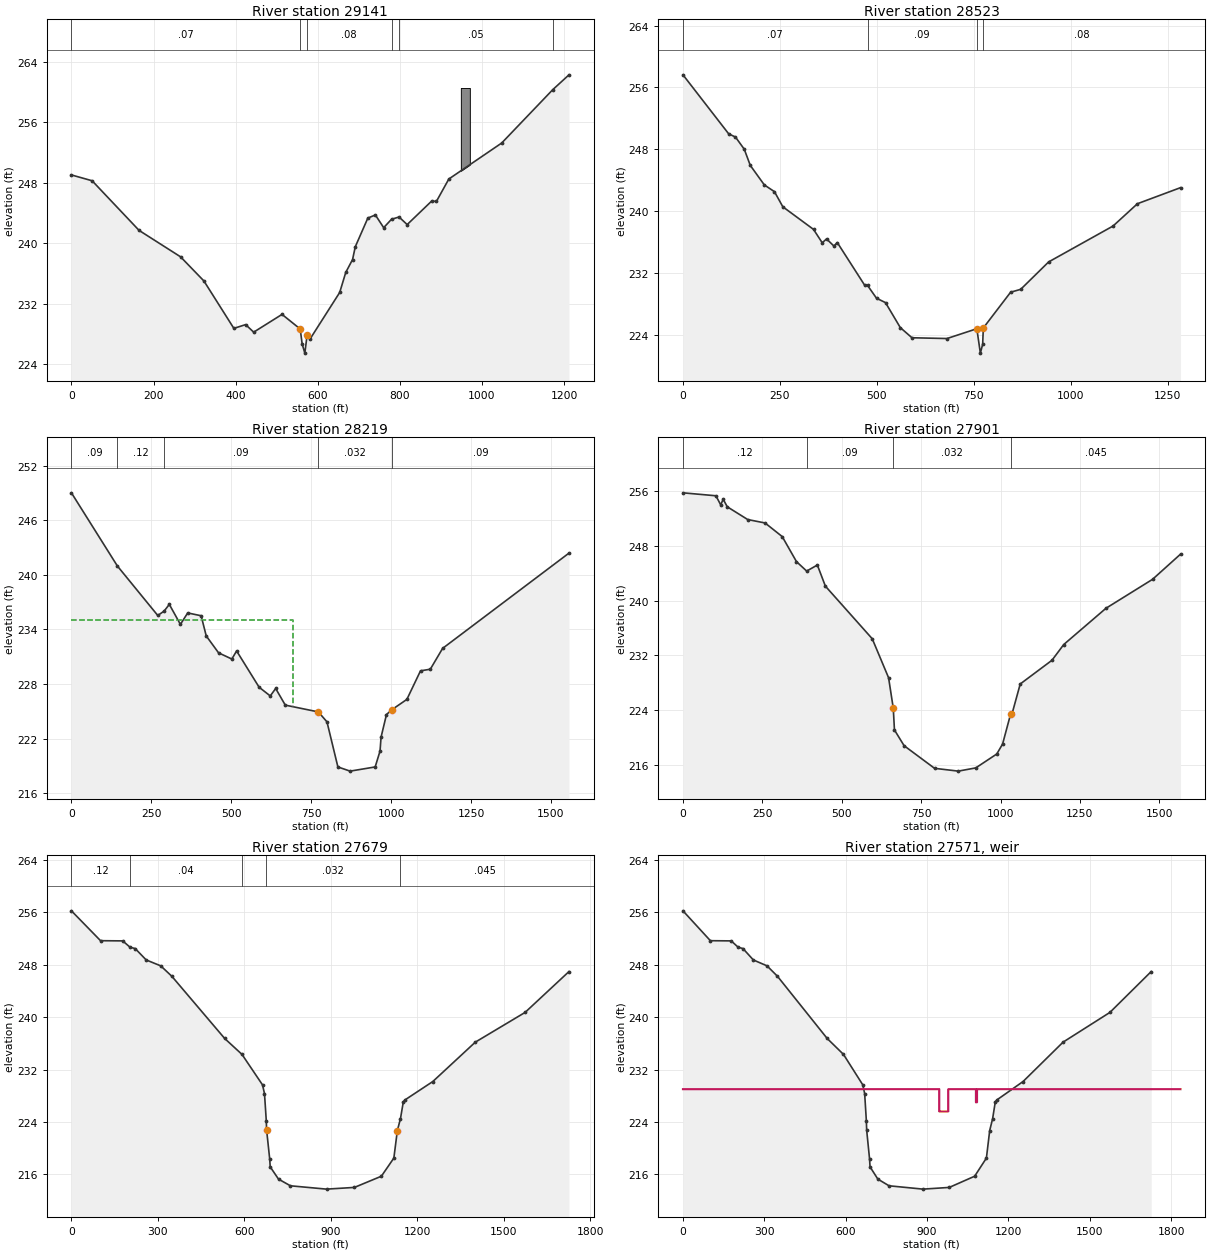
Type RM Length L Ch R = 1 ,29141   ,535.97,617.66,464.45
XS GIS Cut Line= 3
2269225.66469271729456.4219861032268956.40806051728956.904252023
2268723.56751873728355.842912704
#Sta/Elev= 30
       0  249.02   50.41  248.25  164.81  241.69  265.82   238.2  322.85     235
  395.72  228.74  424.41  229.24  443.97  228.24  513.05  230.59   557.3  228.66
  562.11  226.67   568.6  225.47  574.03  227.82  582.04   227.4  653.54  233.49
  668.28  236.14  684.86  237.84  691.49  239.53  722.07  243.32  740.46  243.73
  760.66  242.05  779.71  243.16  798.01  243.46  817.91  242.46  877.79  245.58
  889.01  245.51  919.33  248.48 1048.19  253.24 1172.54  260.29 1212.05  262.25
#Mann= 6 ,-1 , 0
       0     .07       0   557.3     .05       0  574.03     .08       0
  779.71    .035       0  798.01     .05       0 1172.54    .035       0
#Block Obstruct= 1 ,-1
  948.63  970.53 260.514
Bank Sta=557.3,574.03
XS Rating Curve= 0 ,0
Exp/Cntr=0.3,0.1

Type RM Length L Ch R = 1 ,28523   ,389.55,304.03,256.07
XS GIS Cut Line= 4
 2269707.0279433729472.6728990972269557.40746844728998.594540596
2269397.70021999728759.8742324112269029.53298412728423.648446247
#Sta/Elev= 30
       0  257.64  117.83     250  135.43  249.58  158.01  248.01  173.58  245.91
  209.82  243.38  235.89  242.51   257.5  240.55  336.69  237.62  359.05  235.89
  370.25  236.39  389.17  235.47  397.92  235.92  468.66  230.38  475.97  230.36
  499.05  228.71  522.24  228.14  560.33  224.91  590.44  223.59  680.76  223.49
  757.71  224.76  766.81   221.6  772.76  222.75  774.43  224.86  844.84  229.49
  870.79  229.86  942.82  233.41 1108.96  238.06 1171.84  240.95 1282.94  243.03
#Mann= 4 ,-1 , 0
       0     .07       0  475.97     .09       0  757.71     .05       0
  774.43     .08       0
Bank Sta=757.71,774.43
XS Rating Curve= 0 ,0
Exp/Cntr=0.3,0.1

Type RM Length L Ch R = 1 ,28219   ,372.51,318.24,304.59
XS GIS Cut Line= 5
2270228.17791182 729291.110974582269905.40115714728817.032616079
 2269757.4618112728685.9045594632269522.10376088728537.965213552
2269048.02540238728358.084417954
#Sta/Elev= 30
       0  249.03   143.8  240.98  270.09  235.54  289.93  236.02  306.18  236.76
   340.9  234.56   363.7  235.82  405.73  235.51  421.68  233.29  460.27  231.43
  501.75  230.75  516.69  231.64  587.04  227.65  621.92  226.69  638.86  227.51
  668.93  225.68  772.38224.9318   799.3  223.84  833.45  218.88  871.68  218.42
  950.06  218.88  965.35  220.64  968.46  222.15  985.37  224.64 1002.86225.1903
 1049.21  226.31 1091.84  229.45 1122.53  229.63 1160.99  231.92 1556.27   242.4
#Mann= 5 ,-1 , 0
       0     .09       0   143.8     .12       0  289.93     .09       0
  772.38    .032       0 1002.86     .09       0
#XS Ineff= 2 , 0
       0  694.12     235               0
Permanent Ineff=
       F       F
Bank Sta=772.38,1002.86
XS Rating Curve= 0 ,0
Exp/Cntr=0.3,0.1

Type RM Length L Ch R = 1 ,27901   ,241.76,222.3,164.38
XS GIS Cut Line= 4
2270544.23015082728793.4968110622269970.96518543728416.923930526
2269611.20359422728268.9845846152269130.40071997728164.754590884
#Sta/Elev= 30
       0  255.73  103.72   255.3  118.75  253.98  126.68  254.79   139.5  253.69
  203.89  251.83  258.57  251.33  312.59  249.34  357.41  245.69  389.52  244.31
  423.19  245.19  448.46  242.11  596.02  234.43  647.47  228.74  662.25   224.3
  665.96  221.12  696.39  218.82  792.25  215.52  866.96  215.11  921.94  215.58
  988.19  217.61 1006.52  219.07 1032.24  223.52 1036.74  223.56 1062.04  227.83
 1161.99  231.29 1199.11  233.59 1332.04  238.88 1478.61   243.1 1566.85  246.78
#Mann= 4 ,-1 , 0
       0     .12       0  389.52     .09       0  662.25    .032       0
 1032.24    .045       0
Bank Sta=662.25,1032.24
XS Rating Curve= 0 ,0
Exp/Cntr=0.5,0.3

Type RM Length L Ch R = 1 ,27679   ,194.2,168.77,235.81
XS GIS Cut Line= 5
2270676.79206596728661.8648358432270160.36552705728250.593022048
2269795.82914664728108.049950242 2269695.3479649728108.049950242
2269122.83890593728150.111840278
#Sta/Elev= 30
       0  256.23  101.02  251.67  177.87  251.64  203.51  250.67  221.22  250.47
  259.43  248.73  309.79  247.83  348.32  246.24  531.69  236.74  591.72  234.31
   662.9  229.66  669.77  228.34  676.05  224.16  677.18  222.75  687.82  218.36
  689.62  217.14  718.41  215.27  759.65  214.25  884.93  213.74  981.67     214
 1075.24  215.71 1118.58  218.48 1130.75  222.69 1141.47  224.49 1151.46  227.08
 1158.51   227.4 1253.78  230.17 1401.18  236.18 1573.86  240.72 1726.13  246.96
#Mann= 5 ,-1 , 0
       0     .12       0  203.51     .04       0  591.72     .09       0
  676.05    .032       0 1141.47    .045       0
Bank Sta=677.18,1130.75
XS Rating Curve= 0 ,0
Exp/Cntr=0.5,0.3

Type RM Length L Ch R = 5 ,27571   ,,,
IW Pilot Flow=0
#Inline Weir SE= 10
       0     229     945     229  945.01   225.6  978.01   225.6  978.02     229
 1079.99     229    1080     227    1084     227 1084.01     229 1834.23     229
IW Dist,WD,Coef,Skew,MaxSub,Min_El,Is_Ogee,SpillHt,DesHd
107,36,2.6,0,0.98,, 0 ,,,0,0,

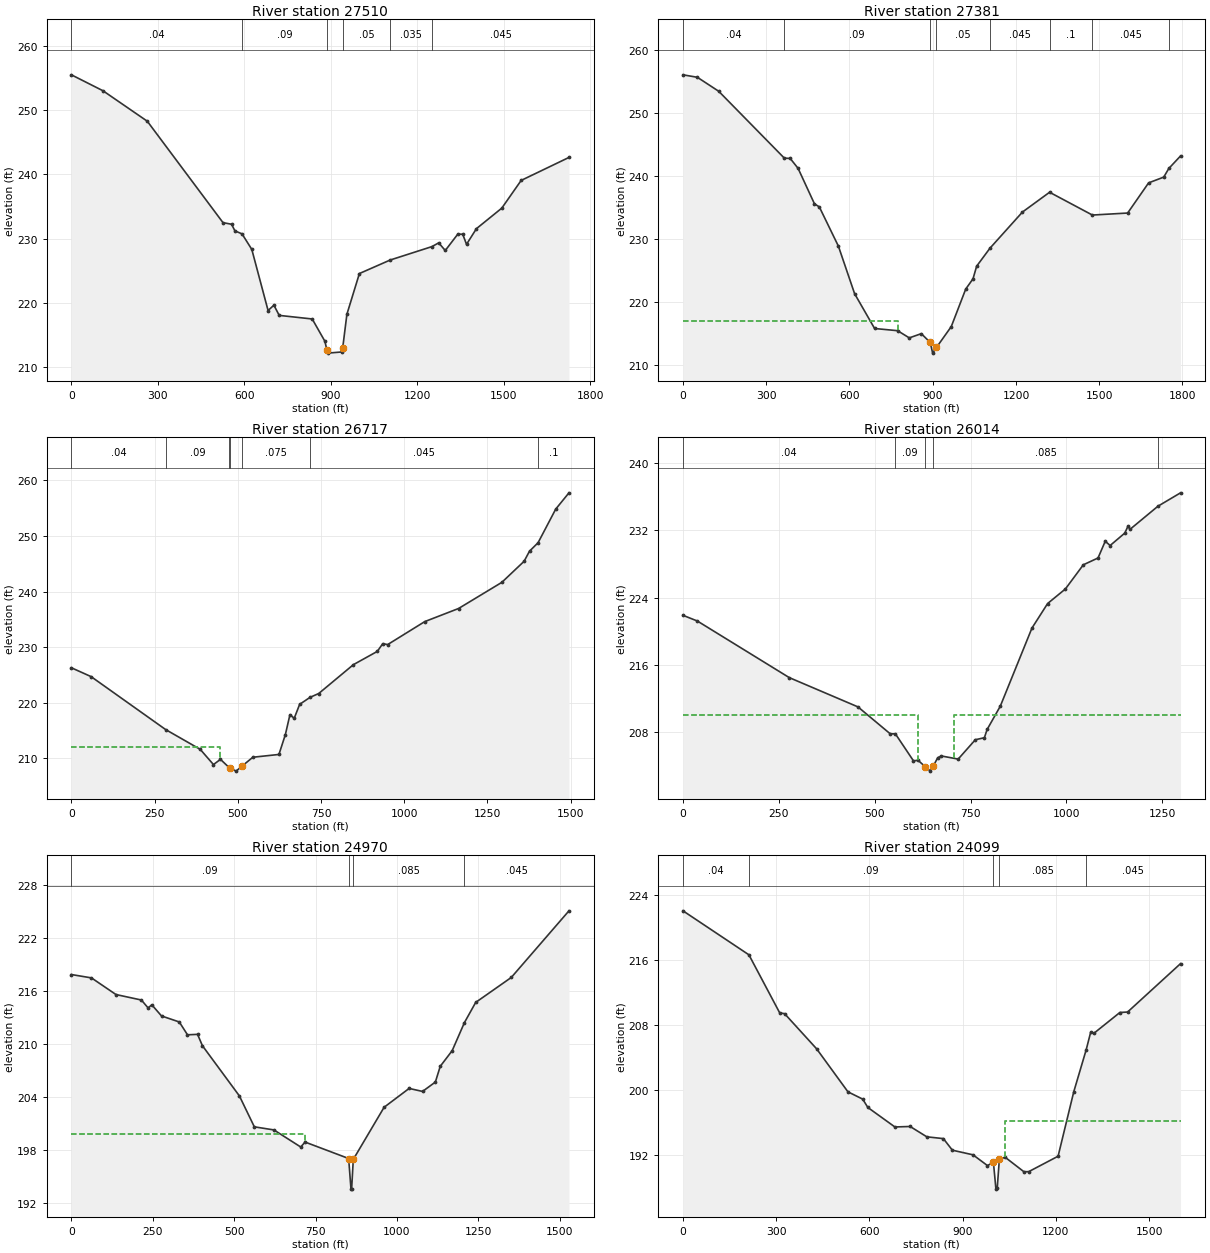
Type RM Length L Ch R = 1 ,27510   ,161.13,128.78,150.19
XS GIS Cut Line= 6
2270715.20621665728518.5402941112270185.65060341728096.156650215
2270116.30403501728075.9831030522269998.02085415728008.606607616
2269786.31681322727953.2869587392269169.06668535727909.538205072
#Sta/Elev= 30
       0  255.51  109.37  253.03  263.22  248.28  525.81  232.48  555.62  232.23
  567.13   231.2  591.85  230.73  625.74  228.31   682.2  218.79  702.48  219.62
  720.81  218.03  835.34  217.47  879.29     214   886.3  212.63  889.08  212.15
  940.14  212.34  940.92   212.9  955.68  218.21  998.98  224.55 1106.03  226.66
 1250.85  228.75 1274.08  229.33 1296.88  228.14 1340.38  230.69 1357.51  230.67
 1370.63   229.1 1404.92  231.54 1492.96  234.74  1560.2  239.06 1726.02  242.64
#Mann= 6 ,-1 , 0
       0     .04       0  591.85     .09       0   886.3     .05       0
  940.92     .05       0 1106.03    .035       0 1250.85    .045       0
Bank Sta=886.3,940.92
XS Rating Curve= 0 ,0
Exp/Cntr=0.5,0.3

Type RM Length L Ch R = 1 ,27381   ,576.23,664.22,531.09
XS GIS Cut Line= 6
 2270737.6457908728405.111990124 2270510.6963394728107.029128656
2270239.71191989727957.9876979142269690.96847036 727764.91129899
2269450.46979801727744.5874675512269182.87268375727842.819319621
#Sta/Elev= 30
       0  256.13   51.79  255.74  128.78  253.52  365.08  242.91  386.51  242.85
  414.86  241.28  473.72  235.66  491.36  235.16  560.02  228.94  618.55  221.38
  690.56  215.86  773.61  215.51  815.51  214.37  858.87  215.04  891.18  213.64
  899.75  211.95  913.41  212.85  966.83  216.16 1018.97  222.12 1045.24  223.75
 1058.29  225.75 1106.17   228.6 1223.25  234.34 1321.17237.4885 1475.38  233.87
 1602.59  234.19 1678.07  238.98 1732.56  239.89  1750.8  241.26 1793.12  243.25
#Mann= 8 ,-1 , 0
       0     .04       0  365.08     .09       0  891.18     .05       0
  913.41     .05       0 1106.17    .045       0 1321.17      .1       0
 1475.38    .045       0  1750.8    .035       0
#XS Ineff= 2 , 0
       0     775     217               0
Permanent Ineff=
       F       F
Bank Sta=891.18,913.41
XS Rating Curve= 0 ,0
Exp/Cntr=0.3,0.1

Type RM Length L Ch R = 1 ,26717   ,612.37,703.24,683.94
XS GIS Cut Line= 6
2270747.45066094727644.2295344772270608.00989872727519.863449261
2270525.09917523727474.6394182592270404.50175925727414.340710267
2270203.93199173727357.2269388592269334.19969247727331.429986805
#Sta/Elev= 30
       0  226.29   59.15   224.7  283.14  215.17  387.03  211.61  426.79  208.87
  447.84  209.81  473.57  208.35  475.39  208.29  494.84  207.69  512.17  208.57
  545.13  210.19  623.51  210.69  642.88  214.28  656.57  217.85  669.44   217.2
  685.72  219.71  716.97  220.97  743.07  221.66  847.15  226.85  919.05  229.24
  935.42  230.63  950.27  230.47 1061.54   234.6 1163.19  236.96 1293.31  241.67
 1360.14  245.46 1376.38  247.28 1402.11   248.8 1455.12  254.85 1494.94  257.78
#Mann= 7 ,-1 , 0
       0     .04       0  283.14     .09       0  473.57     .05       0
  475.39     .05       0  512.17    .075       0  716.97    .045       0
 1402.11      .1       0
#XS Ineff= 2 , 0
           447.4  212.12
Permanent Ineff=
       F       F
Bank Sta=475.39,512.17
XS Rating Curve= 0 ,0
Exp/Cntr=0.3,0.1

Type RM Length L Ch R = 1 ,26014   ,949.9,1043.38,1074.91
XS GIS Cut Line= 6
2270675.46415681727357.9421327112270627.93473759726929.940556347
2270549.65034974726845.6342924682270431.08978698726774.847208604
2270236.51279823726640.8905088452269890.35911748726489.315280691
#Sta/Elev= 30
       0  221.89   37.55  221.21  277.19  214.49  456.47  211.01  540.65  207.81
  554.07  207.81  601.09  204.61   613.3  204.66  631.68  203.92  645.54  203.38
  652.18  203.93   664.5  204.97  674.02  205.18  717.85  204.81  762.65  207.11
  786.23  207.35  793.36  208.33  827.66  211.09  910.24  220.37  951.17  223.29
  997.52  225.02 1044.31  227.89 1082.67   228.7 1101.48  230.69 1114.17  230.18
 1152.54  231.66 1160.92  232.49 1166.05   232.1 1238.96  234.85 1297.88  236.44
#Mann= 5 ,-1 , 0
       0     .04       0  554.07     .09       0  631.68     .05       0
  652.18    .085       0 1238.96    .045       0
#XS Ineff= 2 , 0
       0  613.32     210  707.79       0     210
Permanent Ineff=
       F       F
Bank Sta=631.68,652.18
XS Rating Curve= 0 ,0
Exp/Cntr=0.3,0.1

Type RM Length L Ch R = 1 ,24970   ,816.37,871.45,815.45
XS GIS Cut Line= 6
2271463.77017558727078.2522046272271409.19616476 726822.43652904
2271385.32003509726634.8383669562271289.81551617726290.339923829
2271218.18712701726089.098259062 2270993.0693325725635.451794371
#Sta/Elev= 30
       0  217.84   61.64  217.46  136.85  215.58  214.97  214.96  235.47  214.07
  246.98  214.42  276.75  213.16  331.37  212.48  356.56  211.03  387.51  211.08
  402.35   209.8  516.05  204.12  561.89  200.63  622.02  200.28  704.45  198.35
   717.7  198.91  851.62  197.05  858.79  193.59  860.85  193.64  865.87  196.95
  960.51  202.84 1037.43  204.97 1078.58  204.63 1117.99  205.69 1133.01  207.47
 1169.68  209.24 1207.28  212.41 1241.84  214.69  1351.2  217.51  1528.4  225.04
#Mann= 4 ,-1 , 0
       0     .09       0  851.62     .05       0  865.87    .085       0
 1207.28    .045       0
#XS Ineff= 2 , 0
          717.52  199.78
Permanent Ineff=
       F       F
Bank Sta=851.62,865.87
XS Rating Curve= 0 ,0
Exp/Cntr=0.3,0.1

Type RM Length L Ch R = 1 ,24099   ,1139.02,1118.95,1014.85
XS GIS Cut Line= 6
2272151.46936294727002.2030681972272151.46936294726526.474865034
2272139.42561094726357.862337321 2272064.3486584726003.060272172
2271898.55057138725695.4559784832271748.00367166 725502.75594683
#Sta/Elev= 30
       0     222  212.19   216.6  311.37  209.47  326.98  209.38  430.16  205.06
     531  199.78  578.37  198.89  595.04  197.86  682.09  195.47  731.06  195.53
  784.85  194.26  838.11  194.04  867.01  192.62   933.5  192.05  979.95  190.73
  999.12  191.14 1007.25  187.84 1011.36  187.93 1018.33  191.54 1037.29  191.74
 1097.44  189.97 1113.06  189.99  1207.3  191.88 1257.74  199.79 1297.62  204.93
    1312  207.07    1322  206.95 1406.12  209.52 1431.03  209.58  1601.4  215.52
#Mann= 5 ,-1 , 0
       0     .04       0  212.19     .09       0  999.12     .05       0
 1018.33    .085       0 1297.62    .045       0
#XS Ineff= 2 , 0
                         1036.76          196.15
Permanent Ineff=
       F       F
Bank Sta=999.12,1018.33
XS Rating Curve= 0 ,0
Exp/Cntr=0.3,0.1

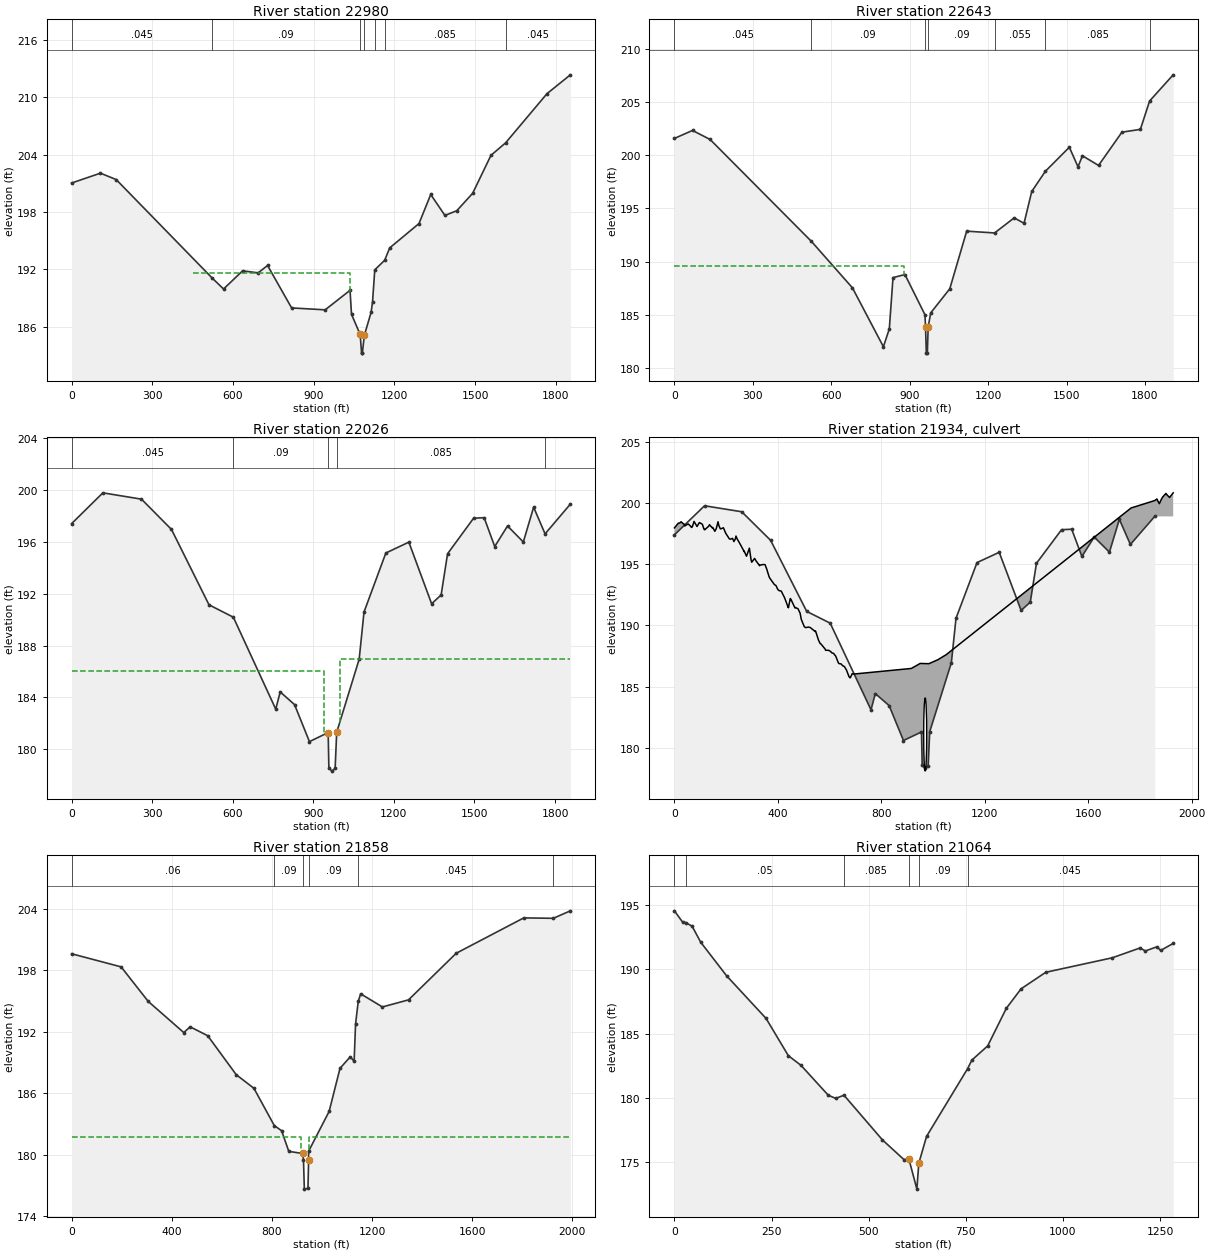
Type RM Length L Ch R = 1 ,22980   ,278.56,336.89,299.13
XS GIS Cut Line= 6
2273349.82268485726104.9435457592273199.27578512725749.652862385
2272940.33511755 725454.580938922272741.61320992725261.880907238
2272416.43190648725105.312131509 2271982.8568352725051.115247607
#Sta/Elev= 30
       0  201.02  107.21  202.05  165.74  201.38   522.7  191.07  564.89  189.93
  635.56  191.83  693.52  191.62  728.44  192.39  817.85  187.95  942.57  187.75
 1034.99  189.79 1040.58  187.28 1072.62  185.17 1077.99  183.22 1080.81  183.22
 1088.12  185.07 1113.34  187.49 1118.66  188.56 1126.94  191.93 1163.85  192.94
 1182.46  194.23 1291.39  196.78 1335.02  199.82 1387.71  197.63 1431.86  198.12
 1490.76  199.94 1558.96  203.92 1613.24  205.22  1767.2  210.37 1854.09  212.34
#Mann= 7 ,-1 , 0
       0    .045       0   522.7     .09       0 1072.62     .05       0
 1088.12    .085       0 1126.94    .055       0 1163.85    .085       0
 1613.24    .045       0
#XS Ineff= 1 ,-1
     450 1035.87  191.59
Permanent Ineff=
       F
Bank Sta=1072.62,1088.12
XS Rating Curve= 0 ,0
Exp/Cntr=0.3,0.1

Type RM Length L Ch R = 1 ,22643   ,535.26,616.59,570.14
XS GIS Cut Line= 5
2273540.99346125725979.9502374682273309.05391541 725539.94727549
2273100.99049924725232.9684647922272858.81832638725041.959427014
2272132.30180778724956.687535167
#Sta/Elev= 30
       0  201.58   69.16  202.33  136.59  201.48  524.37  191.89  680.99  187.53
  799.47  181.99  822.11  183.67  836.22  188.49  881.85  188.78  958.48     185
   960.7  183.83  963.57  181.43  967.58  181.39  970.75  183.84   980.4  185.17
 1053.39  187.44 1118.08  192.86 1224.86  192.69 1299.84  194.11 1337.48   193.6
 1367.03  196.59 1419.11  198.49 1510.84  200.75 1544.03  198.91 1560.95  199.95
 1622.56  199.04 1712.16  202.17 1782.61  202.43 1817.92   205.1 1908.18  207.56
#Mann= 7 ,-1 , 0
       0    .045       0  524.37     .09       0  958.48     .05       0
  970.75     .09       0 1224.86    .055       0 1419.11    .085       0
 1817.92    .045       0
#XS Ineff= 2 , 0
          877.32  189.55
Permanent Ineff=
       F       F
Bank Sta=960.7,970.75
XS Rating Curve= 0 ,0
Exp/Cntr=0.5,0.3

Type RM Length L Ch R = 1 ,22026   ,133.05,168.01,167.86
BEGIN DESCRIPTION:
Surveyed Section
END DESCRIPTION:
XS GIS Cut Line= 6
 2274111.1171578  725812.4715276 2273758.9608655    725325.85556
 2273570.4692276     725011.4789 2273507.6493296  724952.8900322
 2273373.1896543  724916.0736925 2272713.6969613  724944.8864801
#Sta/Elev= 30
       0  197.42  116.44   199.8  260.19  199.31  371.92  196.97  511.53  191.15
  602.23  190.19  760.01  183.09  776.67  184.42  830.03  183.44  885.51  180.58
   955.2  181.28   957.9  178.54  969.53   178.3  981.16  178.51     987   181.3
 1070.72  186.95 1088.67  190.59 1169.96  195.15 1255.66  195.99 1340.43  191.23
 1375.84  191.91 1399.73  195.09 1496.72  197.84 1535.99  197.88 1575.38  195.65
 1623.07  197.24 1681.84     196  1720.2  198.69 1762.86  196.63 1857.02  198.93
#Mann= 5 ,-1 , 0
       0    .045       0  602.23     .09       0   955.2     .05       0
     987    .085       0 1762.86    .055       0
#XS Ineff= 2 , 0
       0     940  186.03     998       0     187
Permanent Ineff=
       F       F
Bank Sta=955.2,987
XS Rating Curve= 0 ,0
Exp/Cntr=0.5,0.3

Type RM Length L Ch R = 2 ,21934   ,,,
BEGIN DESCRIPTION:
Old Raleigh Rd
END DESCRIPTION:
Bridge Culvert--1,0,-1,-1, 0
Deck Dist Width WeirC Skew NumUp NumDn MinLoCord MaxHiCord MaxSubmerge Is_Ogee
71.49,22.82,2.6,0, 147, 147, , , 0.95, 0, 1,1,,
       0    4.54    7.91   14.96   19.99   25.62   33.87   37.27   40.06   47.34
   53.57   62.18   66.31   68.47   69.61   75.75   78.63   87.47   93.57    94.2
    95.8   97.58  108.07  114.17   114.8  116.78  132.79  135.37  146.36  147.78
  148.67  156.15  161.57  168.62  171.72  177.46  181.81  189.38  192.58  198.11
  198.92  208.34  212.09  216.02   224.7  229.93  235.69  237.89  242.47  254.91
   269.4  269.85  270.11  277.99  278.15  278.32  278.64   289.8  296.36  298.81
  310.07  315.52   328.2  329.36  329.75  332.25  343.52  350.42   357.1   362.7
  363.34  366.12  369.15  383.95  386.39  392.51  399.55  404.16  413.11  425.84
  440.01  440.61   440.8  447.93  450.66  461.31   466.1   468.2  478.14  479.99
  485.82  490.57  502.08  507.75   516.9  518.21  524.02  524.97  528.16  543.83
  545.32  546.56  556.98  563.44  565.93  583.38  584.27  592.31  594.51  596.95
  604.24  608.48  615.55  620.59  623.34   633.6  634.85  635.96  644.38  650.05
  656.86  659.99  660.41  664.81  674.77  678.22  680.09  687.24  692.07 915.877
 950.091 983.6261018.064 1050.87 1765.58 1855.97 1864.17 1865.19 1874.68 1883.32
 1887.79 1893.48 1900.33 1902.07 1914.18 1922.06  1928.4
  197.99   198.1  198.19  198.38  198.38  198.49  198.34   198.3  198.14  198.25
  198.31  198.13  198.02  198.11   198.1  198.52  198.42   198.1  198.33  198.36
  198.41  198.42  198.28  197.89  197.89  197.83  198.13  198.25  197.99  198.02
  198.01  197.71  197.92  198.49  198.18  197.91  197.93     198  197.83  197.56
  197.53  197.23   197.1  197.06  197.13  196.87  197.09  197.32  197.09  196.63
  196.06  196.04  196.07  195.71   195.7   195.7  195.67  196.33  195.37  195.18
  195.49  195.29  194.92  194.89  194.92  194.95  194.99  194.98   194.6   194.2
  194.15  193.98  193.86  193.41  193.35  193.27  192.95  192.86  192.81  192.27
  191.47  191.49  191.46  192.21  192.13  191.65  191.43  191.47  191.36  191.27
  191.01  190.49   189.9  189.82  189.87  189.87  189.84  189.83  189.78  189.51
  189.55  189.49   188.8  188.52   188.5  188.05  187.97  187.97  187.96  187.96
  187.86  187.76  187.71  187.56   187.5  186.95  186.91  186.88  186.85  186.71
  186.64  186.53  186.51  186.37  185.82  185.72  185.72  186.05  186.02  186.48
  186.89  186.87  187.19  187.61  199.62  200.22  200.33  200.36  199.97  200.36
  200.52  200.65  200.81  200.75  200.48  200.69  200.86
                                                                                
                                                                                
                                                                                
                                                                                
                                                                                
                                                                                
                                                                                
                                                                                
                                                                                
                                                                                
                                                                                
                                                                                
                                                                                
                                                                                
                                                        
       0    4.54    7.91   14.96   19.99   25.62   33.87   37.27   40.06   47.34
   53.57   62.18   66.31   68.47   69.61   75.75   78.63   87.47   93.57    94.2
    95.8   97.58  108.07  114.17   114.8  116.78  132.79  135.37  146.36  147.78
  148.67  156.15  161.57  168.62  171.72  177.46  181.81  189.38  192.58  198.11
  198.92  208.34  212.09  216.02   224.7  229.93  235.69  237.89  242.47  254.91
   269.4  269.85  270.11  277.99  278.15  278.32  278.64   289.8  296.36  298.81
  310.07  315.52   328.2  329.36  329.75  332.25  343.52  350.42   357.1   362.7
  363.34  366.12  369.15  383.95  386.39  392.51  399.55  404.16  413.11  425.84
  440.01  440.61   440.8  447.93  450.66  461.31   466.1   468.2  478.14  479.99
  485.82  490.57  502.08  507.75   516.9  518.21  524.02  524.97  528.16  543.83
  545.32  546.56  556.98  563.44  565.93  583.38  584.27  592.31  594.51  596.95
  604.24  608.48  615.55  620.59  623.34   633.6  634.85  635.96  644.38  650.05
  656.86  659.99  660.41  664.81  674.77  678.22  680.09  687.24  692.07 915.877
 950.091 983.6261018.064 1050.87 1765.58 1855.97 1864.17 1865.19 1874.68 1883.32
 1887.79 1893.48 1900.33 1902.07 1914.18 1922.06  1928.4
  197.99   198.1  198.19  198.38  198.38  198.49  198.34   198.3  198.14  198.25
  198.31  198.13  198.02  198.11   198.1  198.52  198.42   198.1  198.33  198.36
  198.41  198.42  198.28  197.89  197.89  197.83  198.13  198.25  197.99  198.02
  198.01  197.71  197.92  198.49  198.18  197.91  197.93     198  197.83  197.56
  197.53  197.23   197.1  197.06  197.13  196.87  197.09  197.32  197.09  196.63
  196.06  196.04  196.07  195.71   195.7   195.7  195.67  196.33  195.37  195.18
  195.49  195.29  194.92  194.89  194.92  194.95  194.99  194.98   194.6   194.2
  194.15  193.98  193.86  193.41  193.35  193.27  192.95  192.86  192.81  192.27
  191.47  191.49  191.46  192.21  192.13  191.65  191.43  191.47  191.36  191.27
  191.01  190.49   189.9  189.82  189.87  189.87  189.84  189.83  189.78  189.51
  189.55  189.49   188.8  188.52   188.5  188.05  187.97  187.97  187.96  187.96
  187.86  187.76  187.71  187.56   187.5  186.95  186.91  186.88  186.85  186.71
  186.64  186.53  186.51  186.37  185.82  185.72  185.72  186.05  186.02  186.48
  186.89  186.87  187.19  187.61  199.62  200.22  200.33  200.36  199.97  200.36
  200.52  200.65  200.81  200.75  200.48  200.69  200.86
                                                                                
                                                                                
                                                                                
                                                                                
                                                                                
                                                                                
                                                                                
                                                                                
                                                                                
                                                                                
                                                                                
                                                                                
                                                                                
                                                                                
                                                        
BR Coef=-1 , 0 , 0 ,, 0 ,,,0.8,0,,0,
WSPro=,,,, 1 ,,,, 0 ,,,, 0 ,,,,-1 ,-1 ,-1 , 0 , 0 , 0 , 0 , 0
Culvert=5,6,11.5,60,0.021,0.5,1,42,1,178.0737,969.5,176.3805,936.67,Culvert #1  , 0 ,55.67
Culvert Bottom n=0.021
BC Design=,, 0 ,, 0 ,,,,,,
BC Use User HTab Curves=0
BC User HTab FreeFlow(D)= 0

Type RM Length L Ch R = 1 ,21858   ,751.4,794.33,775.94
BEGIN DESCRIPTION:
Survyed Section
END DESCRIPTION:
XS GIS Cut Line= 6
 2274232.7711497  725690.8175357 2273906.2262241  725313.0498766
    2273688.8156     724917.5148 2273531.6599858   724776.811886
 2273385.9953376   724757.603361 2272712.0962509  724800.8225423
#Sta/Elev= 30
       0  199.62  197.79  198.34  306.08  194.97  448.09  191.93  473.53  192.49
  543.72  191.62   657.5  187.82  728.25  186.49  809.66  182.85  838.79  182.35
 867.587  180.33  923.37  180.13  926.17  179.51  929.69  176.65  944.11  176.73
  946.72  179.49  946.72  180.351028.605  184.23 1072.14  188.44 1112.93  189.56
 1128.54  189.13 1134.22  192.77 1144.95  194.97 1154.56  195.71 1241.44  194.43
 1345.72  195.12 1536.27  199.67  1806.1  203.12 1924.13  203.08 1992.26  203.81
#Mann= 6 ,-1 , 0
       0     .06       0  809.66     .09       0  923.37     .05       0
  946.72     .09       0 1144.95    .045       0 1924.13    .055       0
#XS Ineff= 2 , 0
       0     917   181.7     950       0   181.7
Permanent Ineff=
       F       F
Bank Sta=923.37,946.72
XS Rating Curve= 0 ,0
Exp/Cntr=0.5,0.3

Type RM Length L Ch R = 1 ,21064   ,1293.5,1232.91,1194.81
XS GIS Cut Line= 5
 2274512.0447508  725237.7934033 2274512.0447508  724924.6558518
 2274325.3665952  724491.0807806 2274120.6228115  724153.8557252
  2274072.017873  724061.6145917
#Sta/Elev= 30
       0  194.57   21.01  193.69   28.63  193.66   45.48  193.37   67.98  192.11
  134.22  189.51  236.01  186.18  293.25  183.28  325.76  182.53  395.95   180.2
  415.12  179.95  436.42   180.2  535.34  176.72  590.92  175.18  603.54  175.23
  624.11  172.88  629.04  174.89  649.03  176.99  754.72  182.27   765.8  182.94
  806.34  184.04  854.35  186.97  892.33  188.49  955.93  189.78 1127.16  190.91
 1198.99  191.68 1212.05  191.44 1242.32  191.77 1251.55  191.48 1283.97  192.03
#Mann= 6 ,-1 , 0
       0     .04       0   28.63     .05       0  436.42    .085       0
  603.54     .05       0  629.04     .09       0  754.72    .045       0
Bank Sta=603.54,629.04
XS Rating Curve= 0 ,0
Exp/Cntr=0.3,0.1

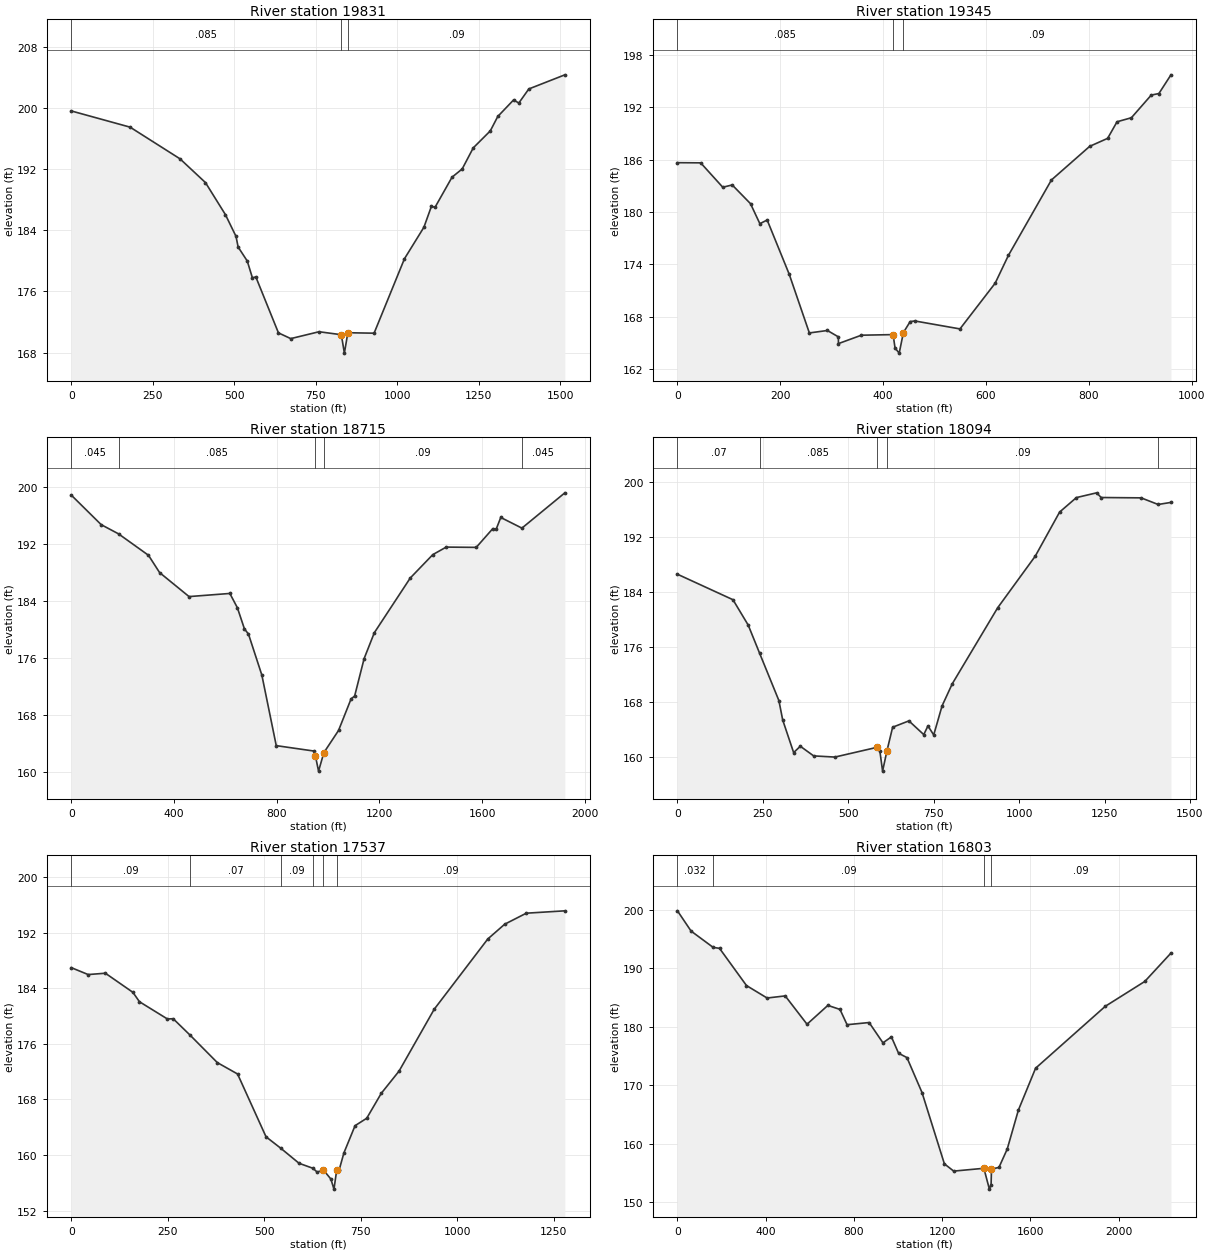
Type RM Length L Ch R = 1 ,19831   ,544.86,486.16,437
XS GIS Cut Line= 5
2276089.77626008724780.1308280972275830.83559249724485.058904588
2275403.28239724724129.7682212292275072.07921784723912.980685592
2274962.91720843723783.208549395
#Sta/Elev= 30
       0  199.62  180.24   197.5  333.49  193.35  411.52  190.24  472.64  186.05
  505.18   183.2  511.61  181.81   539.6  179.98  555.33  177.79  565.99  177.89
   635.3  170.57  673.12  169.82  759.86  170.72  828.26  170.33  837.54  167.92
  848.24  170.59  928.72  170.53 1021.92  180.28 1081.57   184.4 1104.74  187.16
  1115.4  186.99 1167.78  190.95 1198.96  192.03 1232.92  194.79 1285.15  197.01
 1308.14   198.9 1356.57  201.06 1372.67  200.66 1403.32   202.5 1513.91  204.35
#Mann= 3 ,-1 , 0
       0    .085       0  828.26     .05       0  848.24     .09       0
Bank Sta=828.26,848.24
XS Rating Curve= 0 ,0
Exp/Cntr=0.3,0.1

Type RM Length L Ch R = 1 ,19345   ,493.92,630.07,528.53
XS GIS Cut Line= 2
2276112.19554247723811.0842679442275155.01446645723740.832445845
#Sta/Elev= 30
       0  185.64   45.19  185.62    88.1  182.83  106.52  183.09  142.07  180.95
  160.27  178.66  174.48  179.08  217.34  172.88  256.52  166.16  291.64  166.44
  312.97  165.71  313.11  164.94  357.68   165.9  419.35  165.97   423.2  164.43
  431.27  163.85  439.38   166.2  452.59  167.46  461.61  167.53  549.41  166.62
  617.88  171.85  643.53  175.02  727.29  183.66  801.74  187.51  836.58  188.42
   854.9  190.32  882.81  190.78  921.38  193.37  936.28  193.55  959.76  195.69
#Mann= 3 ,-1 , 0
       0    .085       0  419.35     .05       0  439.38     .09       0
Bank Sta=419.35,439.38
XS Rating Curve= 0 ,0
Exp/Cntr=0.3,0.1

Type RM Length L Ch R = 1 ,18715   ,599.38,620.89,555.82
XS GIS Cut Line= 6
2276700.17091249723499.2343862352276462.51383968723397.527615801
2276112.37338518723338.1817760622275610.90103933723272.901352346
2275275.59704484723088.9292491382274907.23600002722886.741093144
#Sta/Elev= 30
       0   198.9  116.27  194.76  183.74  193.47  300.38  190.46  343.73  188.03
  458.42  184.66   617.3   185.1  646.67  183.09  674.13  180.12  689.79   179.4
  741.92  173.64  798.03  163.73  946.65  162.96  950.82  162.23  962.76  160.15
  983.35  162.74  1040.6  165.86 1089.49   170.3 1103.25  170.69 1140.19  175.95
 1180.02  179.59 1319.94  187.27 1407.61  190.55 1459.95  191.61 1576.86  191.57
 1641.28   194.2 1654.26   194.1 1672.38  195.77 1754.79194.2746    1922  199.23
#Mann= 5 ,-1 , 0
       0    .045       0  183.74    .085       0  950.82     .05       0
  983.35     .09       0 1754.79    .045       0
Bank Sta=950.82,983.35
XS Rating Curve= 0 ,0
Exp/Cntr=0.3,0.1

Type RM Length L Ch R = 1 ,18094   ,596.75,556.97,509.32
XS GIS Cut Line= 2
2276441.50095855722691.4458533232275001.33860567722801.214325368
#Sta/Elev= 30
       0  186.59   162.5  182.89  207.09  179.21  240.34  175.14  296.87  168.26
  308.04  165.44  340.06  160.71  359.59  161.63  398.67  160.23  460.75  160.06
   584.7  161.48  592.54  160.88  600.38  158.02  613.11  160.96  629.77  164.39
  677.38  165.31  720.87  163.32  733.12  164.58  750.01  163.27  774.48  167.49
  804.37   170.7  937.16  181.72 1047.26  189.22 1118.48  195.61 1167.61  197.71
 1226.82   198.4 1240.06  197.72 1356.97  197.67 1406.79  196.71 1444.34  197.01
#Mann= 5 ,-1 , 0
       0     .07       0  240.34    .085       0   584.7     .05       0
  613.11     .09       0 1406.79    .045       0
Bank Sta=584.7,613.11
XS Rating Curve= 0 ,0
Exp/Cntr=0.3,0.1

Type RM Length L Ch R = 1 ,17537   ,669.07,733.98,716.8
XS GIS Cut Line= 2
2276221.96401447721997.7091101712275001.33860567722502.644081458
#Sta/Elev= 30
       0  186.96   43.54  185.97   88.26  186.16   159.6  183.41  176.52  182.06
  248.95  179.58  264.06  179.61  308.18  177.23  378.38   173.3  430.88  171.66
  504.69  162.62  542.77  160.98  590.26  158.81  626.26  158.09  637.25  157.54
  653.19  157.86  672.76  156.54  680.76  155.09  688.02  157.87  694.25  157.85
  706.52   160.3  735.46  164.22   765.7  165.29  803.43  168.88  849.56  172.08
  940.54  180.97 1079.54  191.09 1123.25  193.21 1179.37   194.8 1279.31  195.14
#Mann= 6 ,-1 , 0
       0     .09       0  308.18     .07       0  542.77     .09       0
  626.26    .085       0  653.19     .05       0  688.02     .09       0
Bank Sta=653.19,688.02
XS Rating Curve= 0 ,0
Exp/Cntr=0.3,0.1

Type RM Length L Ch R = 1 ,16803   ,836.26,847.05,744.53
BEGIN DESCRIPTION:
Surveyed Section
END DESCRIPTION:
XS GIS Cut Line= 6
2276677.89842911721611.6414193362276255.83546422721554.464334279
 2275547.2664113721592.1541775322275145.63419999721649.909899995
2274989.45673135721727.8376131952274701.21552868722157.317262277
#Sta/Elev= 30
       0   199.8    61.8  196.34  161.93  193.55   190.7  193.39  312.89  187.03
   406.3   184.9  488.38  185.26  587.27  180.42  681.69  183.64  736.64  182.95
  768.75  180.34  868.67  180.71  931.39  177.24  969.72  178.26 1002.11  175.46
 1040.07  174.72 1108.47  168.74 1209.79  156.56  1251.9  155.32 1388.74   155.8
 1413.68  152.24 1421.41     1531423.263  155.681456.917  155.941494.518  159.08
1545.107  165.74 1623.06   172.9 1939.18  183.49 2117.95  187.73 2236.63  192.58
#Mann= 4 ,-1 , 0
       0    .032       0  161.93     .09       0 1388.74     .05       0
1423.263     .09       0
Bank Sta=1388.74,1423.263
XS Rating Curve= 0 ,0
Exp/Cntr=0.3,0.1