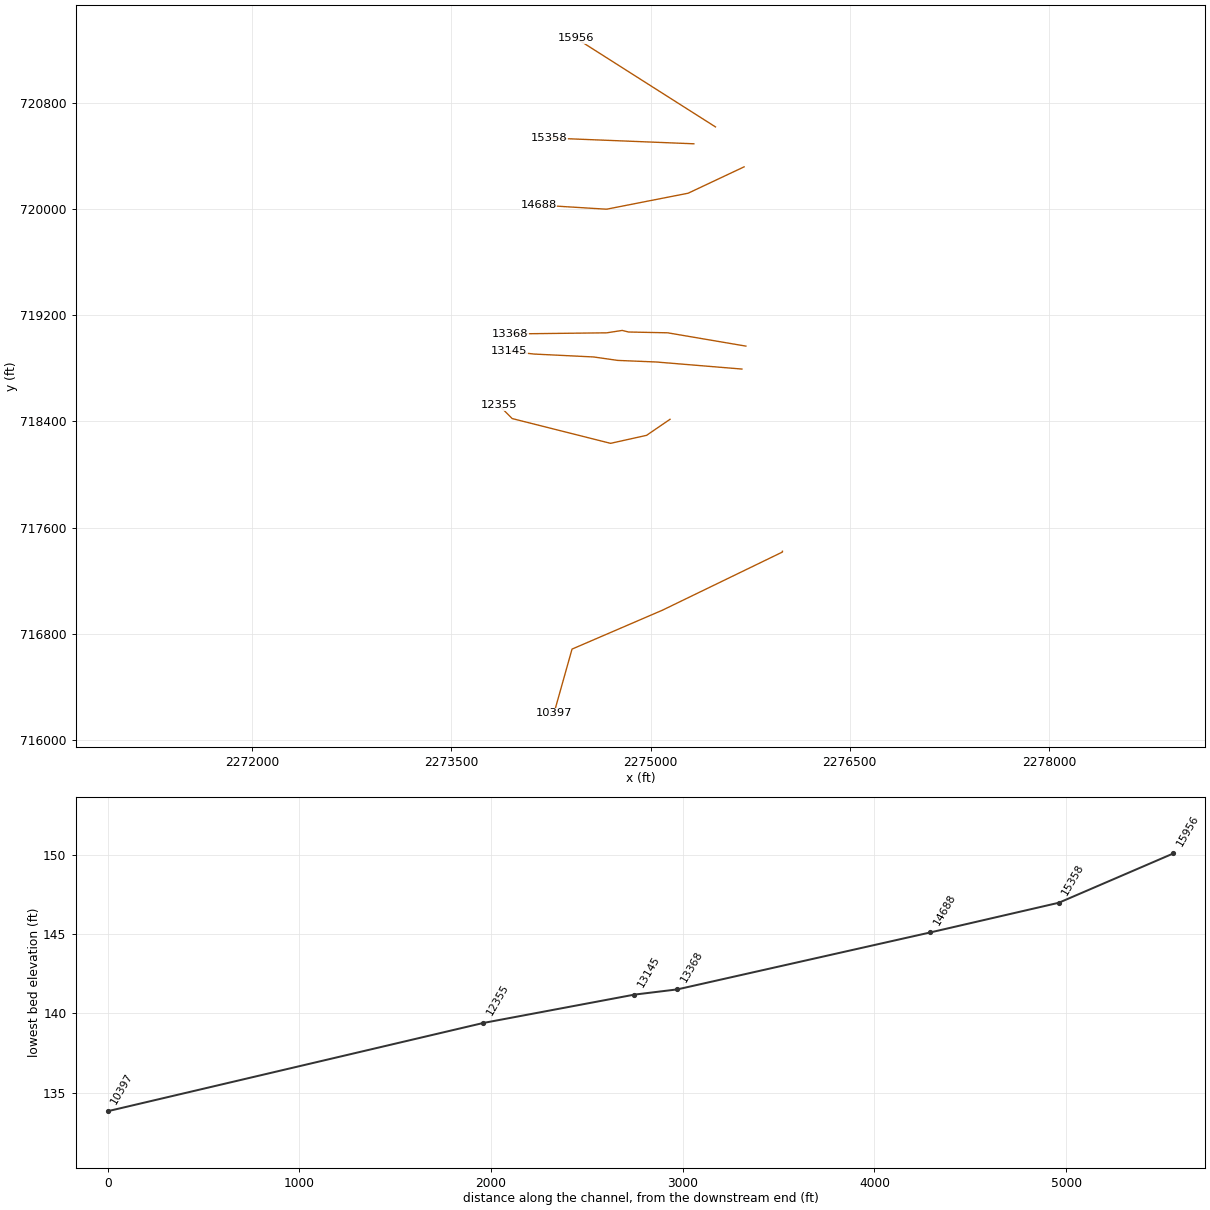
HEC-RAS study DTL_Marsh_Swamp.prj: DTL_Marsh_Swamp

--- DTL_Marsh_Swamp.g01 (geometry) --- (continued)

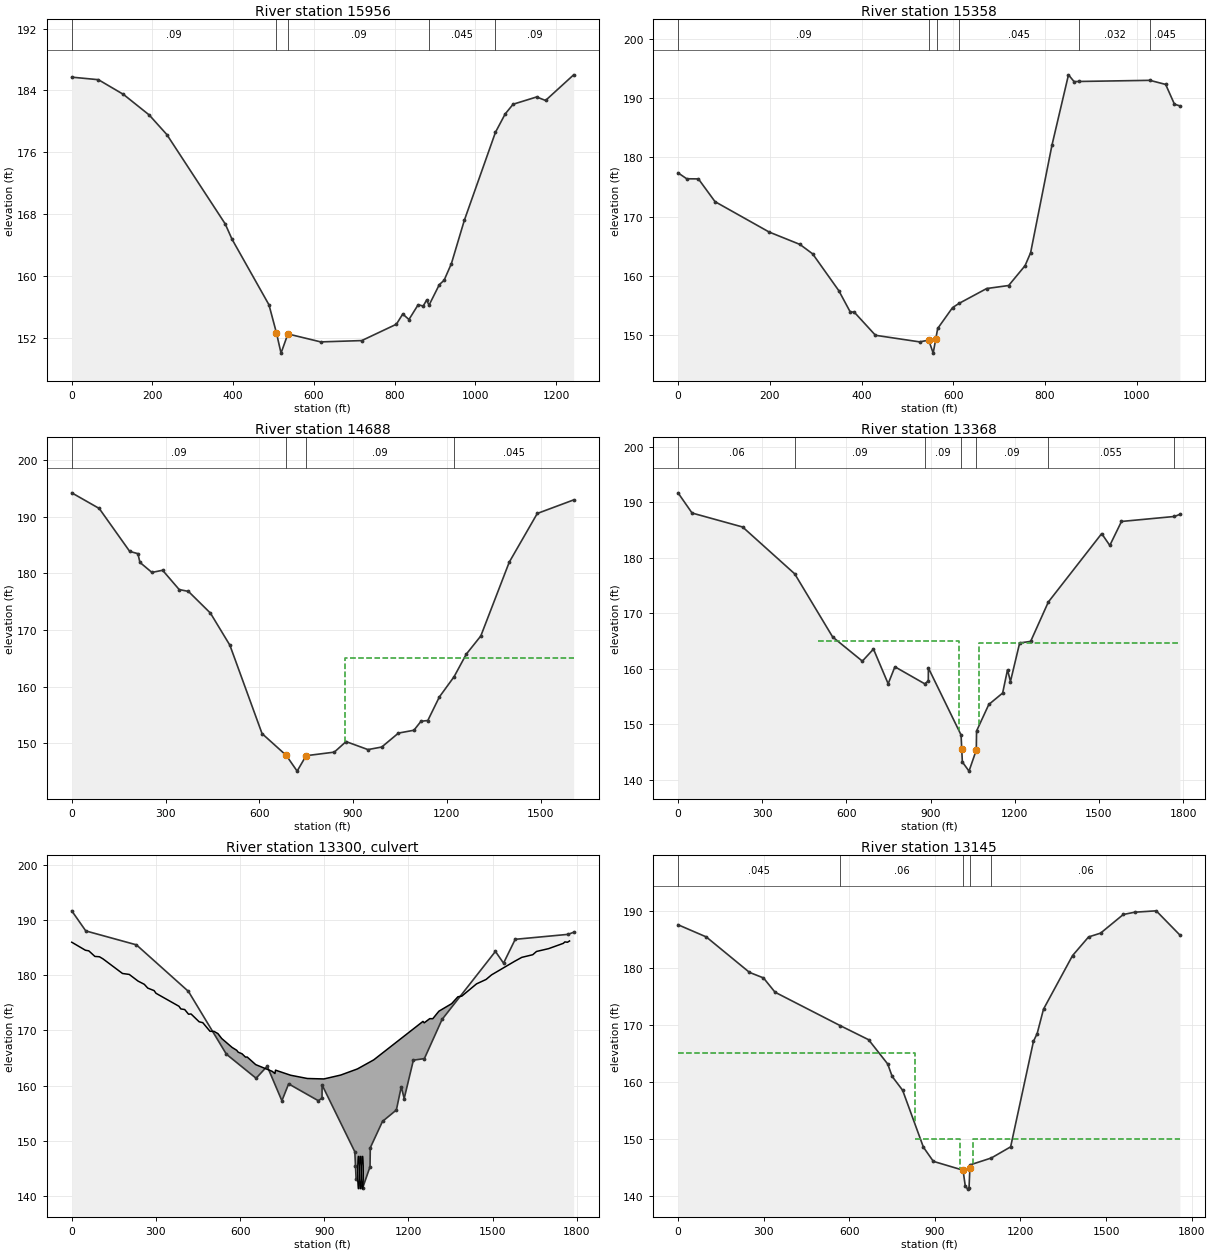
Type RM Length L Ch R = 1 ,15956   ,428.62,597.97,528.44
XS GIS Cut Line= 2
 2275488.7106214720619.0171016162274439.32402891 721286.40941149
#Sta/Elev= 30
       0  185.72   66.04  185.39  128.12  183.49  191.79  180.84  235.52  178.31
   380.1  166.78  397.12  164.79  488.66  156.32  507.01  152.73  518.58  150.08
  535.55  152.56  616.88  151.53   718.6   151.7  804.33  153.81  820.19  155.13
  835.52  154.42  858.33  156.33   870.8  156.16  879.22  156.92  885.34  156.28
  910.83  158.93  922.56  159.48  940.75  161.65   972.8  167.24 1049.88   178.6
 1073.87  180.96 1093.57  182.22 1151.82  183.16 1174.03  182.71 1243.63  186.02
#Mann= 5 ,-1 , 0
       0     .09       0  507.01     .05       0  535.55     .09       0
  885.34    .045       0 1049.88     .09       0
Bank Sta=507.01,535.55
XS Rating Curve= 0 ,0
Exp/Cntr=0.3,0.1

Type RM Length L Ch R = 1 ,15358   ,508.11,670.07,522.45
XS GIS Cut Line= 2
2275326.25328283720491.685674086 2274232.9593015720535.593062878
#Sta/Elev= 30
       0  177.39   18.98  176.39   44.44  176.37   80.67  172.53  198.74   167.4
  265.84  165.31  293.51  163.72  350.43  157.52  375.02  153.98  384.72  153.84
  430.46  149.98  526.58  148.87  546.54  149.16  556.27  146.97  561.85  149.35
  566.12  151.13  598.39  154.64  612.41  155.35  672.92  157.87  720.84  158.38
  756.62  161.73  768.68  163.91  815.19  182.05  851.24  193.93   863.4  192.79
  874.68  192.81 1028.74     193 1063.11  192.31 1082.28  188.97 1094.18  188.69
#Mann= 6 ,-1 , 0
       0     .09       0  546.54     .05       0  565.25     .09       0
  612.41    .045       0  874.68    .032       0 1028.74    .045       0
Bank Sta=546.54,561.85
XS Rating Curve= 0 ,0
Exp/Cntr=0.3,0.1

Type RM Length L Ch R = 1 ,14688   ,1092.57,1319.6,1048.44
XS GIS Cut Line= 4
 2275704.3761967  720317.9207199 2275282.8448775  720119.1988122
 2274668.6135266  719998.7612924 2274155.5396857   720030.295099
#Sta/Elev= 30
       0  194.19    87.9  191.43   185.4  183.86  211.57  183.46  218.18  181.92
  256.46  180.15  290.71  180.53  343.71  177.13  373.34   176.8  443.64  172.98
  505.98  167.31   608.9  151.72  686.29  147.88  721.16   145.1  749.84  147.82
  840.06  148.45  877.67  150.31  947.76   148.9  991.85  149.35 1045.36  151.81
 1094.85  152.31  1117.5  153.89 1139.34  154.03 1176.12  158.17 1223.45  161.76
 1262.25  165.72 1308.89  168.94 1399.89  181.96 1489.61  190.55 1605.99  192.94
#Mann= 4 ,-1 , 0
       0     .09       0  686.29     .05       0  749.84     .09       0
 1223.45    .045       0
#XS Ineff= 2 , 0
       0                     875       0     165
Permanent Ineff=
       F       F
Bank Sta=686.29,749.84
XS Rating Curve= 0 ,0
Exp/Cntr=0.5,0.3

Type RM Length L Ch R = 1 ,13368   ,228.76,223.94,196.44
BEGIN DESCRIPTION:
Surveyed Section
END DESCRIPTION:
XS GIS Cut Line= 6
 2275717.9636342  718967.0334172 2275128.9021998  719067.3446035
    2274834.7933     719073.3289 2274786.4483001     719085.2027
      2274670.11     719067.2397 2273944.3764891  719058.8074813
#Sta/Elev= 30
       0  191.66      50  188.02  230.32   185.5  415.86  177.06  551.01  165.69
  656.94  161.33  696.52  163.51  748.89  157.25  772.92  160.31  878.75  157.26
  891.96  157.73 892.146  160.111008.712  148.021011.122  145.471013.254  143.16
 1037.04  141.511062.975  145.311063.913  148.741107.509  153.521156.863  155.58
 1174.26  159.78 1184.69  157.66 1217.55  164.61 1256.71  164.89 1319.65  171.98
 1509.83  184.31 1538.76  182.18 1580.38   186.5 1769.14   187.4 1788.63  187.78
#Mann= 7 ,-1 , 0
       0     .06       0  415.86     .09       0  878.75     .09       0
1008.712     .05       01062.975     .09       0 1319.65    .055       0
 1769.14    .045       0
#XS Ineff= 3 ,-1
                             500 1001.12     165 1072.97 1788.63  164.51
Permanent Ineff=
       F       T       F
Bank Sta=1011.122,1062.975
XS Rating Curve= 0 ,0
Exp/Cntr=0.5,0.3

Type RM Length L Ch R = 2 ,13300   ,,,
BEGIN DESCRIPTION:
SR 1147
END DESCRIPTION:
Bridge Culvert--1,0,-1,-1, 0
Deck Dist Width WeirC Skew NumUp NumDn MinLoCord MaxHiCord MaxSubmerge Is_Ogee
55,20,2.6,0, 60, 60, , , 0.95, 0, 1,1,,
       0   48.72   60.71   82.44    98.6  111.76  180.86  204.86   236.3  258.43
  270.89  293.46   300.3   382.1  388.69  402.46  416.28  425.02  454.03  466.93
  492.71  507.12  520.94  534.27   571.3  587.89  592.97  606.73  619.27  625.24
  655.59  714.05  724.08 726.145     780 839.764 898.767 958.2891017.9021076.027
1251.607 1255.95 1275.74 1286.64  1308.4    1354 1376.06 1390.06 1442.53 1476.56
 1496.06 1577.33 1603.74 1642.83 1656.29 1699.33 1751.87 1757.28 1766.58 1774.02
  185.97  184.52  184.41   183.4  183.34  182.94  180.31  180.14  178.93  178.35
  177.66  177.21  176.72  174.37  173.89  173.78  172.93  172.98  171.56   171.4
  169.84  169.82  169.42  168.54  166.92   166.4  166.06  165.77  165.16  165.18
   163.8  162.59  162.19   162.8  161.88  161.29  161.21  161.91  163.02  164.66
  171.63  171.37  172.13  172.12  173.48  174.85  176.09  176.21  178.43  179.23
  180.06  182.49  183.23  183.71   184.3  184.81  185.77  186.03  185.97   186.2
                                                                                
                                                                                
                                                                                
                                                                                
                                                                                
                                                                                
       0   48.72   60.71   82.44    98.6  111.76  180.86  204.86   236.3  258.43
  270.89  293.46   300.3   382.1  388.69  402.46  416.28  425.02  454.03  466.93
  492.71  507.12  520.94  534.27   571.3  587.89  592.97  606.73  619.27  625.24
  655.59  714.05  724.08 726.145     780 839.764 898.767 958.2891017.9021076.027
1251.607 1255.95 1275.74 1286.64  1308.4    1354 1376.06 1390.06 1442.53 1476.56
 1496.06 1577.33 1603.74 1642.83 1656.29 1699.33 1751.87 1757.28 1766.58 1774.02
  185.97  184.52  184.41   183.4  183.34  182.94  180.31  180.14  178.93  178.35
  177.66  177.21  176.72  174.37  173.89  173.78  172.93  172.98  171.56   171.4
  169.84  169.82  169.42  168.54  166.92   166.4  166.06  165.77  165.16  165.18
   163.8  162.59  162.19   162.8  161.88  161.29  161.21  161.91  163.02  164.66
  171.63  171.37  172.13  172.12  173.48  174.85  176.09  176.21  178.43  179.23
  180.06  182.49  183.23  183.71   184.3  184.81  185.77  186.03  185.97   186.2
                                                                                
                                                                                
                                                                                
                                                                                
                                                                                
                                                                                
BR Coef=-1 , 0 , 0 ,, 0 ,,,0.8,0,,0,
WSPro=,,,, 1 ,,,, 0 ,,,, 0 ,,,,-1 ,-1 ,-1 , 0 , 0 , 0 , 0 , 0
Multiple Barrel Culv=1,6,,80,0.021,0.5,1,2,1,141.2498,141, 3,Culvert #1  , 0 ,27.18
1022.0431006.3471029.0431013.3471036.0431020.347
Culvert Bottom n=0.021
BC Design=,, 0 ,, 0 ,,,,,,
BC Use User HTab Curves=0
BC User HTab FreeFlow(D)= 0

Type RM Length L Ch R = 1 ,13145   ,622.97,789.48,632.47
BEGIN DESCRIPTION:
Surveyed Section
END DESCRIPTION:
XS GIS Cut Line= 6
 2275688.0837064  718794.1566918 2275041.3966968  718847.5137058
    2274753.0018     718859.2503    2274570.0521       718885.38
 2274121.5217756  718907.2735615 2273935.8393669  718928.6163671
#Sta/Elev= 30
       0  187.52   98.88  185.39  250.45  179.17  299.48   178.2  339.91   175.7
  568.32  169.84  667.86  167.37   734.8  163.12  750.53  160.93  787.13  158.51
  859.99  148.53 894.756  146.05 998.893   144.5 1006.55  141.78 1015.05  141.18
 1019.95  141.42 1022.81   144.81023.664  145.43 1098.11  146.64 1165.66  148.59
 1245.67  167.09 1258.66  168.45 1280.91  172.73 1382.57  182.11 1438.76  185.38
 1480.95  186.05 1560.57  189.32 1600.74  189.72 1675.86  189.96 1758.95  185.71
#Mann= 5 ,-1 , 0
       0    .045       0  568.32     .06       0 998.893     .05       0
 1022.81     .09       0 1098.11     .06       0
#XS Ineff= 3 ,-1
       0     830     165     830  988.89     150 1032.81 1758.95     150
Permanent Ineff=
       F       F       F
Bank Sta=998.893,1022.81
XS Rating Curve= 0 ,0
Exp/Cntr=0.5,0.3

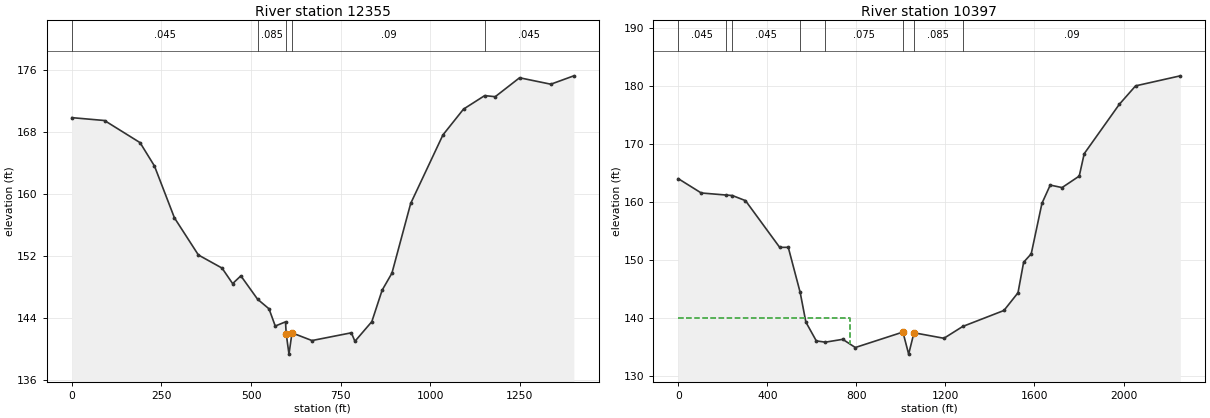
Type RM Length L Ch R = 1 ,12355   ,1489.1,1958.29,1683.36
XS GIS Cut Line= 5
 2275146.6651964  718415.5400536  2274969.707326  718294.5703874
 2274698.7229065  718234.3516275 2273958.0321598  718421.0297832
  2273855.660268   718523.401675
#Sta/Elev= 30
       0  169.87   91.36   169.5  190.46  166.65  230.65  163.64  286.35  156.96
   353.2  152.17  419.19  150.48  448.76  148.48   471.7  149.48  518.49  146.46
  550.21  145.23  567.63  143.01  596.25  143.55  598.15  142.03  605.92  139.39
  614.37  142.13  670.06  141.14  779.99  142.14  789.87  141.04  837.04  143.58
  865.78  147.63  893.15  149.83  945.43  158.81 1035.35  167.64 1092.78  170.97
 1151.84  172.71 1181.28  172.57 1249.21  175.01 1336.32  174.18 1400.58  175.26
#Mann= 5 ,-1 , 0
       0    .045       0  518.49    .085       0  598.15    .055       0
  614.37     .09       0 1151.84    .045       0
Bank Sta=598.15,614.37
XS Rating Curve= 0 ,0
Exp/Cntr=0.3,0.1

Type RM Length L Ch R = 1 ,10397   ,1333.4,1665.19,1255.41
XS GIS Cut Line= 5
 2275993.4262442  717421.3983689 2275993.4262442  717415.3764929
 2275090.8909393  716977.7049814 2274408.5506141  716683.7460946
 2274272.4702235  716199.4279567
#Sta/Elev= 30
       0  164.06  103.34  161.59  216.49  161.23   243.1  161.15   302.1  160.27
  455.74  152.22  494.21  152.23  547.77  144.45  573.26  139.35  620.13  136.11
  660.75  135.89  738.95  136.38  795.34  134.97 1009.17  137.63 1034.96  133.83
  1058.8  137.51 1193.45  136.56 1277.53  138.59 1462.97  141.35 1526.08   144.4
 1551.36  149.66 1585.52  151.11 1633.58   159.8 1670.82  162.95 1724.02  162.52
 1801.15   164.5 1823.49  168.36 1981.29  176.87  2054.2  180.04 2255.12  181.77
#Mann= 8 ,-1 , 0
       0    .045       0  216.49     .08       0   243.1    .045       0
  547.77     .07       0  660.75    .075       0 1009.17     .05       0
  1058.8    .085       0 1277.53     .09       0
#XS Ineff= 2 , 0
       0     770     140               0
Permanent Ineff=
       F       F
Bank Sta=1009.17,1058.8
XS Rating Curve= 0 ,0
Exp/Cntr=0.3,0.1