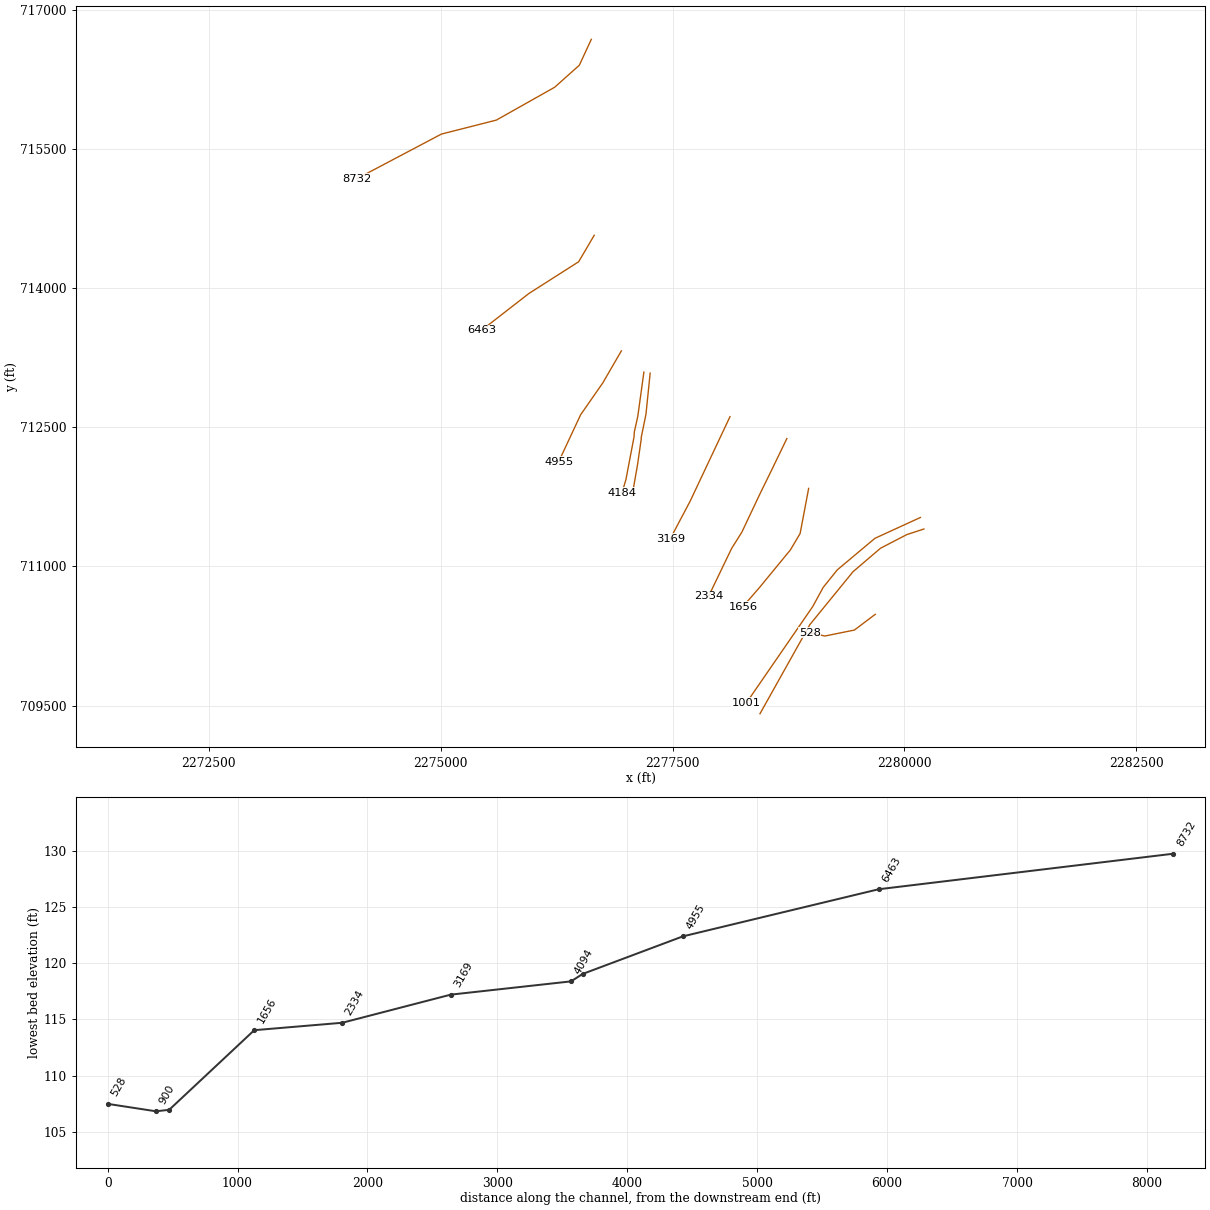
HEC-RAS study DTL_Marsh_Swamp.prj: DTL_Marsh_Swamp

--- DTL_Marsh_Swamp.g01 (geometry) --- (continued)

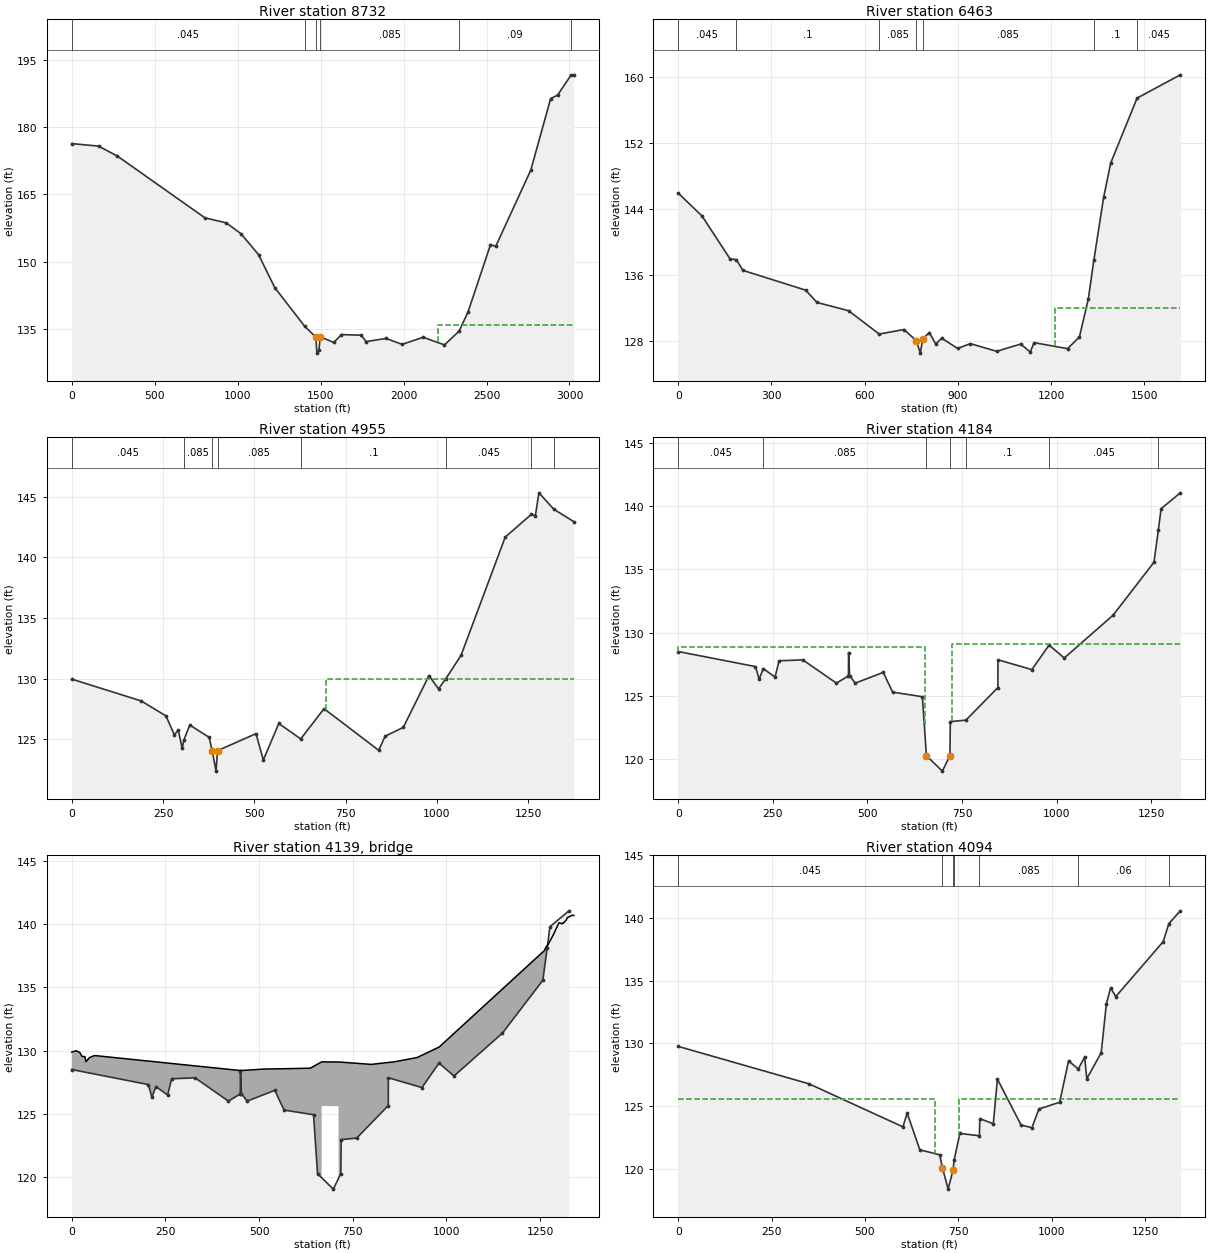
Type RM Length L Ch R = 1 ,8732    ,1825.71,2268.94,2034.55
BEGIN DESCRIPTION:
Surveyed Section
END DESCRIPTION:
XS GIS Cut Line= 6
 2276624.4216351  716679.4596045 2276495.2285954   716400.235938
 2276228.5074812  716162.6874457    2275600.0968     715809.0943
 2275007.4248802  715658.4178391 2274098.9060849   715179.153337
#Sta/Elev= 30
       0  176.31  161.27  175.75  275.31  173.53  802.67   159.8   931.5  158.68
 1020.63  156.25 1126.06  151.61 1223.23  144.31 1404.61  135.661471.079  133.28
1477.813  129.721489.982  130.371497.536  133.361579.182  132.09 1625.69  133.84
 1745.02  133.71 1773.86  132.29 1894.63  132.98 1991.36  131.67 2118.33  133.24
 2246.56  131.55 2335.26  134.62 2388.66  138.88 2524.04  153.82  2555.9  153.48
 2766.92  170.41 2886.72  186.31  2928.4  187.08 3010.48   191.6 3026.52  191.47
#Mann= 6 ,-1 , 0
       0    .045       0 1404.61    .085       01471.079     .05       0
1497.536    .085       0 2335.26     .09       0 3010.48    .045       0
#XS Ineff= 2 , 0
       0                    2205       0     136
Permanent Ineff=
       F       F
Bank Sta=1471.079,1497.536
XS Rating Curve= 0 ,0
Exp/Cntr=0.3,0.1

Type RM Length L Ch R = 1 ,6463    ,1458.24,1507.51,1386.8
XS GIS Cut Line= 4
 2276655.6259457  714567.9685488 2276487.9960161  714282.7833484
 2275951.2731123   713940.754047 2275439.4136532  713543.3102317
#Sta/Elev= 30
       0  145.95   76.81  143.16  167.26  137.95  186.73   137.9  207.87  136.59
  409.96  134.19  446.41   132.7  547.89   131.7   646.6  128.87  726.22  129.42
  766.45  128.05  778.65  126.56  786.96  128.31   807.8  129.05  828.49  127.66
  847.38  128.37  898.68  127.13  939.77  127.71 1024.52  126.78 1101.98  127.66
 1132.33  126.69 1145.06  127.83 1252.51   127.1 1290.77  128.52 1319.46  133.15
 1337.13  137.82 1368.55  145.42 1391.35  149.59 1476.21  157.46 1615.29  160.28
#Mann= 7 ,-1 , 0
       0    .045       0  186.73      .1       0   646.6    .085       0
  766.45     .05       0  786.96    .085       0 1337.13      .1       0
 1476.21    .045       0
#XS Ineff= 2 , 0
       0                    1211       0     132
Permanent Ineff=
       F       F
Bank Sta=766.45,786.96
XS Rating Curve= 0 ,0
Exp/Cntr=0.3,0.1

Type RM Length L Ch R = 1 ,4955    ,574.3,771.2,713.81
XS GIS Cut Line= 4
 2276948.3455403  713322.2430832 2276748.7236584  712978.0602722
 2276508.9366488  712633.6172084 2276272.8363488  712128.6249001
#Sta/Elev= 30
       0  129.96  190.31  128.16  258.16  126.92  281.03  125.35  291.66  125.77
  302.31  124.25  307.32  124.97  323.21  126.17  376.27  125.16  384.61  124.05
  395.19  122.37  399.15  124.06  504.53  125.46  524.56  123.29  567.09   126.3
  627.01  125.03  690.92  127.52  840.52  124.09  858.25  125.25  907.91  125.98
  978.33  130.25 1004.36  129.15 1024.54     130 1066.06  131.92 1187.14  141.68
 1258.84  143.56 1269.65  143.44 1279.33  145.33 1320.03  143.98 1375.03  142.95
#Mann= 8 ,-1 , 0
       0    .045       0  307.32    .085       0  384.61     .05       0
  399.15    .085       0  627.01      .1       0 1024.54    .045       0
 1258.84    .035       0 1320.03    .045       0
#XS Ineff= 2 , 0
       0                     695       0     130
Permanent Ineff=
       F       F
Bank Sta=384.61,399.15
XS Rating Curve= 0 ,0
Exp/Cntr=0.5,0.3

Type RM Length L Ch R = 1 ,4184    ,91.7,89.45,96.94
BEGIN DESCRIPTION:
Surveyed Section
END DESCRIPTION:
XS GIS Cut Line= 6
 2277191.3527867  713093.5484272 2277125.5480801  712615.9942705
    2277087.7378     712446.5323    2277085.5045     712397.2739
 2276997.6989358  711935.3855904 2276954.4558428  711790.6152359
#Sta/Elev= 30
       0   128.5  204.21  127.31  213.88   126.3  224.67  127.15  255.89  126.48
  266.67  127.77  329.22  127.84  418.15     126  449.85  126.57 450.348  128.42
  452.91  126.59  468.15     126  541.93  126.85  566.69  125.29 645.348  124.92
 656.016  120.25 698.145  119.03 718.231  120.26 719.167  122.95 760.513  123.07
 844.982  125.65  845.07  127.85  934.78  127.07  980.22  129.01 1020.35  127.99
 1149.45  131.38 1257.43  135.57 1269.01   138.1  1276.3  139.81 1327.13  141.07
#Mann= 7 ,-1 , 0
       0    .045       0  224.67    .085       0 656.016     .05       0
 718.231    .085       0 760.513      .1       0  980.22    .045       0
 1269.01    .035       0
#XS Ineff= 2 , 0
       0  651.02  128.85  723.23       0   129.1
Permanent Ineff=
       F       F
Bank Sta=656.016,718.231
XS Rating Curve= 0 ,0
Exp/Cntr=0.5,0.3

Type RM Length L Ch R = 3 ,4139    ,,,
BEGIN DESCRIPTION:
SR 1149 Rock Ridge Sinis Rd
END DESCRIPTION:
Bridge Culvert--1,0,-1,-1, 0
Deck Dist Width WeirC Skew NumUp NumDn MinLoCord MaxHiCord MaxSubmerge Is_Ogee
29,35,2.6,0, 38, 38, , , 0.95, 0, 1,1,,
       0     .48   11.34   21.62   27.03   34.89    37.8    46.4   46.73   60.65
 450.348 513.912 577.179 636.869 667.102   708.7 712.102 799.304 860.372 921.704
 980.931 1261.76 1265.51 1271.28 1276.05 1284.54 1299.97 1300.28 1300.76 1309.17
 1309.29 1311.27 1312.63 1319.98 1322.79 1333.85 1336.53 1340.18
  129.88  129.89  129.99  129.85  129.55  129.52  129.13  129.41  129.44  129.61
  128.42  128.54  128.57  128.61  129.11   129.1   129.1  128.91  129.11  129.45
  130.29  137.93  138.19  138.39  138.66  139.12   140.1  140.12  140.12  140.04
  140.04  140.13  140.11  140.35  140.53  140.69  140.73   140.7
                                                                                
                                  125.61   125.6   125.6
                                                                                
                                                                
       0     .48   11.34   21.62   27.03   34.89    37.8    46.4   46.73   60.65
 450.348 513.912 577.179 636.869 697.102   738.7 742.102 799.304 860.372 921.704
 980.931 1261.76 1265.51 1271.28 1276.05 1284.54 1299.97 1300.28 1300.76 1309.17
 1309.29 1311.27 1312.63 1319.98 1322.79 1333.85 1336.53 1340.18
  129.88  129.89  129.99  129.85  129.55  129.52  129.13  129.41  129.44  129.61
  128.42  128.54  128.57  128.61  129.11   129.1   129.1  128.91  129.11  129.45
  130.29  137.93  138.19  138.39  138.66  139.12   140.1  140.12  140.12  140.04
  140.04  140.13  140.11  140.35  140.53  140.69  140.73   140.7
                                                                                
                                  125.61   125.6   125.6
                                                                                
                                                                
BR Coef=-1 , 1 , 0 ,1.25, 0 ,,,0.8,0,2,0,
WSPro=,,,, 1 ,,,, 0 ,,,, 0 ,,,,-1 ,-1 ,-1 , 0 , 0 , 0 , 0 , 0
BC Design=,, 0 ,, 0 ,,,,,,
BC Use User HTab Curves=0
BC User HTab FreeFlow(D)= 0

Type RM Length L Ch R = 1 ,4094    ,819.62,925.83,735.01
BEGIN DESCRIPTION:
Surveyed Section
END DESCRIPTION:
XS GIS Cut Line= 6
 2277259.0376278  713082.2676203 2277213.9144004  712640.4360186
    2277162.6829     712389.7954    2277162.9698     712373.0527
 2277123.6679456  712100.8374243 2277063.5036424  711754.8926808
#Sta/Elev= 30
       0  129.76  349.69  126.78  601.57  123.34  612.96  124.44 646.787  121.51
 699.882  121.11  707.53  120.07 722.662  118.37 736.022  119.92 738.566  120.68
 754.124  122.81 806.377  122.63  807.52     124  843.59  123.58   854.6  127.15
  917.85  123.49  946.91  123.27  965.85  124.77 1021.23   125.3  1045.1  128.61
 1070.87  127.95 1088.17   128.9 1093.95  127.18 1132.53  129.26 1146.17  133.13
 1157.71  134.43 1171.55  133.74 1298.43  138.12 1313.65  139.56  1344.3  140.58
#Mann= 7 ,-1 , 0
       0    .045       0  707.53     .05       0 736.022     .05       0
 738.566     .06       0 806.377    .085       0 1070.87     .06       0
 1313.65    .035       0
#XS Ineff= 2 , 0
       0  686.86   125.6   752.1       0   125.6
Permanent Ineff=
       F       F
Bank Sta=707.53,736.022
XS Rating Curve= 0 ,0
Exp/Cntr=0.5,0.3

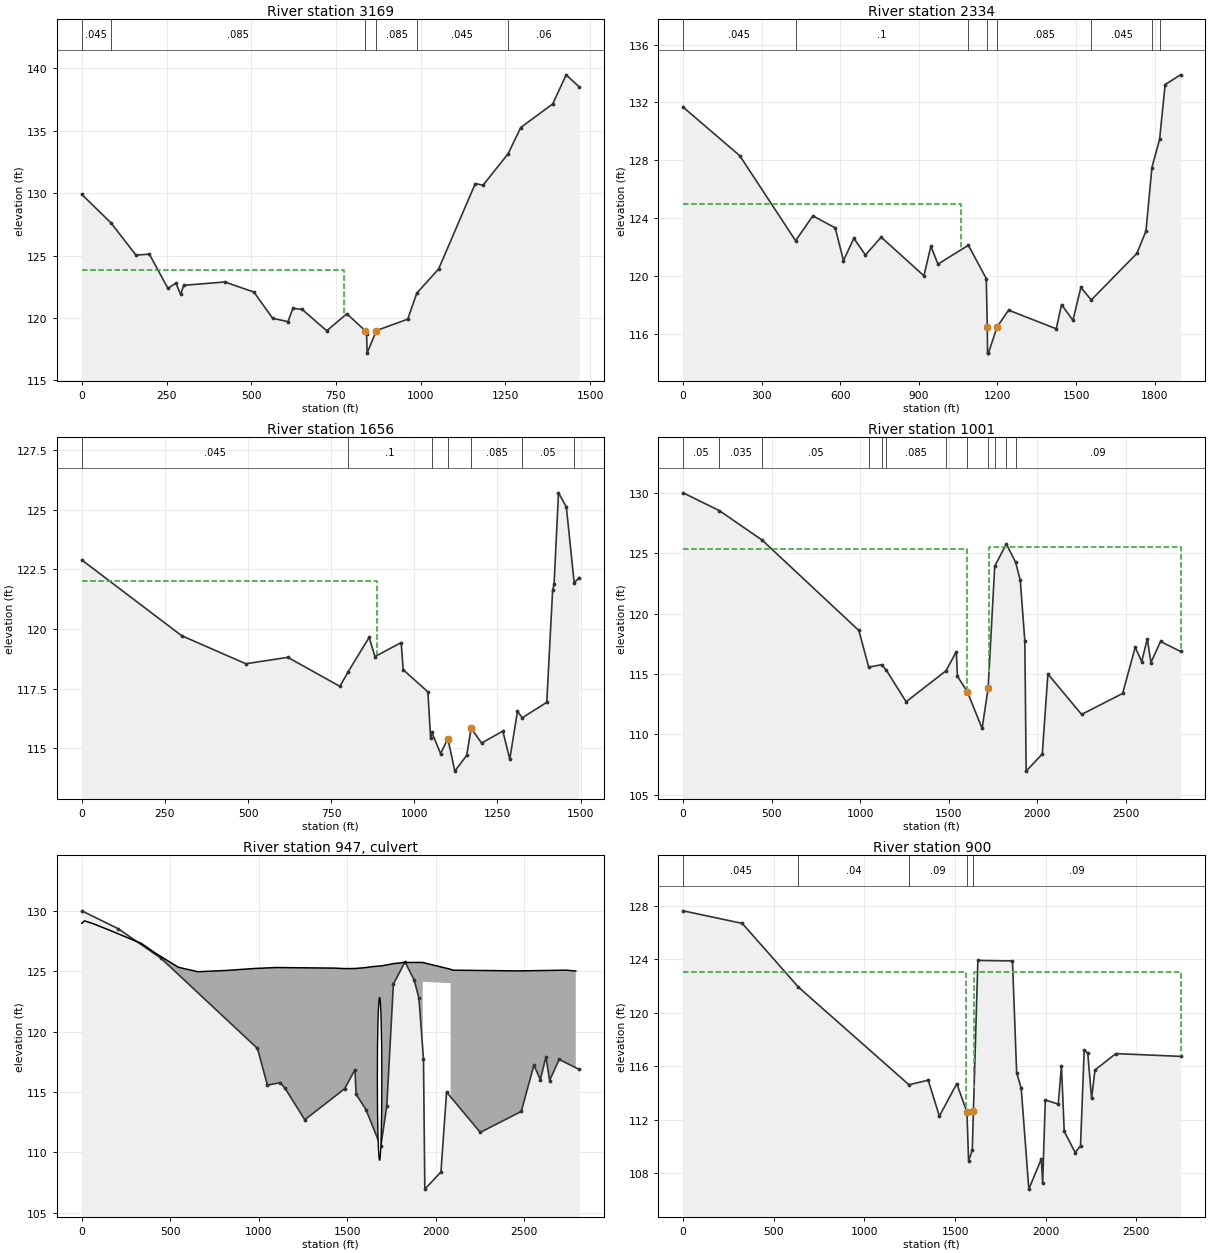
Type RM Length L Ch R = 1 ,3169    ,742.43,835.08,796.68
XS GIS Cut Line= 3
 2278120.0417283  712613.5581317  2277691.865568   711705.920553
 2277475.0129218  711295.4494726
#Sta/Elev= 30
       0   129.9   85.87  127.63  159.89  125.04  199.29  125.12  254.14  122.38
  277.83  122.79  291.85   121.9  300.71  122.62  421.74  122.89  508.08  122.08
   563.2  119.98  608.39  119.71  623.02  120.78  650.53  120.69  722.69  118.98
  782.12  120.34  835.84     119  840.54  118.71  841.86  117.19  869.58     119
  961.89  119.91  988.41  121.99 1052.95  123.93 1161.24  130.77 1183.92  130.64
 1258.05  133.16 1295.21  135.26 1389.56  137.15 1429.36  139.48  1467.8  138.51
#Mann= 6 ,-1 , 0
       0    .045       0   85.87    .085       0  835.84     .05       0
  869.58    .085       0  988.41    .045       0 1258.05     .06       0
#XS Ineff= 2 , 0
       0     775  123.82               0
Permanent Ineff=
       F       F
Bank Sta=835.84,869.58
XS Rating Curve= 0 ,0
Exp/Cntr=0.3,0.1

Type RM Length L Ch R = 1 ,2334    ,601.63,677.28,475.68
XS GIS Cut Line= 6
2278733.26079987 712377.350406172278563.67068362712026.864166006
2278450.61060616711796.9753418272278247.10246675711367.347047403
2278137.81105849711193.9882619382277889.07888807710677.680574819
#Sta/Elev= 30
       0  131.68  216.51  128.32  429.36122.4532  495.23  124.17  580.55  123.34
  612.09  121.08  651.72  122.62  695.96  121.47  756.09   122.7  919.26  120.03
  945.69  122.07  972.97  120.84 1088.87  122.14 1157.31  119.84 1161.21  116.49
 1162.11   114.7 1165.48  114.69 1198.42  116.49 1242.47  117.66 1424.48  116.37
 1444.57  118.04 1488.13  116.96 1518.51  119.23  1558.1  118.36 1732.34  121.58
 1767.01  123.12 1789.59   127.5 1819.02  129.46 1840.18  133.24 1898.97  133.91
#Mann= 8 ,-1 , 0
       0    .045       0  429.36      .1       0 1088.87    .085       0
 1161.21     .05       0 1198.42    .085       0  1558.1    .045       0
 1789.59    .035       0 1819.02    .045       0
#XS Ineff= 2 , 0
       0    1060     125               0
Permanent Ineff=
       F       F
Bank Sta=1161.21,1198.42
XS Rating Curve= 0 ,0
Exp/Cntr=0.3,0.1

Type RM Length L Ch R = 1 ,1656    ,559.89,655.08,594.8
XS GIS Cut Line= 5
 2278968.3147733  711840.0578668 2278876.4979899  711354.7405836
 2278771.5645233  711177.6653586 2278437.0890984  710771.0481754
 2278260.0138734  710567.7395838
#Sta/Elev= 30
       0   122.9  300.18  119.72  493.31  118.54  619.65  118.81  776.32  117.59
     800  118.18  864.28  119.65  881.54  118.84  960.51  119.43  966.56  118.29
 1040.86  117.36 1049.03  115.41  1052.5  115.67 1078.82  114.77 1101.02  115.39
 1121.79  114.03 1157.45  114.69    1171  115.83 1202.22  115.21 1266.27  115.71
 1287.08  114.53  1310.3  116.55 1324.45  116.27 1398.31  116.92 1415.92  121.62
  1420.3  121.87 1433.53  125.72 1457.21  125.13 1480.77  121.94 1495.88  122.16
#Mann= 7 ,-1 , 0
       0    .045       0     800      .1       0  1052.5    .085       0
 1101.02     .05       0    1171    .085       0 1324.45     .05       0
 1480.77    .035       0
#XS Ineff= 2 , 0
       0     889     122               0
Permanent Ineff=
       F       F
Bank Sta=1101.02,1171
XS Rating Curve= 0 ,0
Exp/Cntr=0.5,0.3

Type RM Length L Ch R = 1 ,1001    ,129.59,101.58,100.64
BEGIN DESCRIPTION:
Surveyed Section
END DESCRIPTION:
XS GIS Cut Line= 6
 2280173.5401931711527.0444068312279683.84873249711302.867471978
2279278.36317542710963.778715909 2279125.3955175710774.098820075
2279012.61970001 710567.549900012278298.69230406709531.680311528
#Sta/Elev= 30
       0  130.02  205.09  128.54  446.42   126.1  992.41  118.61 1048.21  115.57
 1121.26 115.773 1147.95  115.31  1259.5   112.7  1484.8  115.27 1542.83  116.85
1549.577  114.811605.631  113.521688.557  110.491722.574   113.81759.954  123.94
1825.454  125.781877.646  124.27  1904.2  122.78 1929.98  117.74 1937.49  106.95
 2028.61  108.37 2060.26     115 2250.71  111.65 2482.32  113.39 2553.58  117.22
 2590.12  116.03 2621.62  117.92 2642.26  115.95 2696.58   117.7 2809.46  116.87
#Mann= 12 ,-1 , 0
       0     .05       0  205.09    .035       0  446.42     .05       0
 1048.21    .085       0 1121.26     .05       0 1147.95    .085       0
  1484.8    .035       01605.631     .05       01722.574    .085       0
1759.954     .05       01825.454    .035       01877.646     .09       0
#XS Ineff= 2 , 0
       01600.631  125.371727.574       0  125.55
Permanent Ineff=
       F       F
Bank Sta=1605.631,1722.574
XS Rating Curve= 0 ,0
Exp/Cntr=0.5,0.3

Type RM Length L Ch R = 2 ,947     ,,,
BEGIN DESCRIPTION:
RT 42
END DESCRIPTION:
Bridge Culvert--1,0,-1,-1, 0
Deck Dist Width WeirC Skew NumUp NumDn MinLoCord MaxHiCord MaxSubmerge Is_Ogee
42,25,2.6,0, 40, 49, , , 0.95, 0, 0.5,0.25,,
       0     .93   15.02   65.15  159.16  337.63  416.82   545.9  656.48  820.41
  974.54    10981427.957 1486.25 1545.061600.9841640.2991698.5881759.8821819.524
  1925.6  1925.6 1963.25 1963.25 1966.75 1966.75 2002.65 2002.65 2006.15 2006.15
 2042.05 2042.05 2045.55 2045.55 2083.19 2083.19 2095.79 2468.95 2736.61 2790.15
  128.99  128.99  129.19  128.95   128.4  127.31   126.5  125.34  124.97  125.08
  125.24  125.32  125.27  125.23  125.24  125.31  125.39  125.47  125.64  125.74
  125.74  125.74   125.6   125.6  125.59  125.59  125.46  125.46  125.45  125.45
  125.32  125.32  125.31  125.31  125.17  125.17   125.1  125.04   125.1  125.03
                                                                                
                                                                                
          124.14  124.11                  124.11  124.08                  124.08
  124.05                  124.05  124.02
       0     .93   15.02   65.15  159.16  337.63  416.82   545.9  656.48  820.41
  974.54    10981427.957 1486.25 1545.061600.9841640.2991698.5881759.8821819.524
 1842.94 1842.94 1880.59 1880.59 1884.09 1884.09 1919.99 1919.99 1923.49 1923.49
 1959.39 1959.39 1962.89 1962.89 2000.53 2000.53  2218.7 2612.24 2737.34 2738.03
 2744.35 2748.16 2758.68 2765.08 2769.64 2780.59 2785.91 2786.93 2790.15
  128.99  128.99  129.19  128.95   128.4  127.31   126.5  125.34  124.97  125.08
  125.24  125.32  125.27  125.23  125.24  125.31  125.39  125.47  125.64  125.74
  125.74  125.74   125.9   125.9  125.89  125.89  125.76  125.76  125.75  125.75
  125.62  125.62  125.61  125.61  125.17  125.17  125.17  125.33  125.14  125.11
  124.84  124.88  124.75  125.03  125.03  125.13  125.07  125.01  125.03
                                                                                
                                                                                
          124.14  124.17                  124.17  124.14                  124.14
  124.11                  124.11  124.02
                                                                        
BR Coef=-1 , 0 , 0 ,, 0 ,,,0.8,-1,,0,
WSPro=,,,, 1 ,,,, 0 ,,,, 0 ,,,,-1 ,-1 ,-1 , 0 , 0 , 0 , 0 , 0
Culvert=9,13.5,25,36,0.014,0.4,1,60,2,109.3418,1682,109.57,1583,Culvert #1  , 0 ,35
Culvert Bottom n=0.014
BC Design=,, 0 ,, 0 ,,,,,,
BC Use User HTab Curves=0
BC User HTab FreeFlow(D)= 0

Type RM Length L Ch R = 1 ,900     ,393.79,371.97,261.35
BEGIN DESCRIPTION:
Surveyed Section
END DESCRIPTION:
XS GIS Cut Line= 6
 2280211.6979692711403.0316343752280027.26871786711342.615155473
 2279744.2652114711196.3436802332279446.62759915710942.363243788
2278981.03690001710371.9655000272278443.39032506709412.100217171
#Sta/Elev= 30
       0  127.64  326.32   126.7  636.35  121.93 1245.81  114.63 1352.11  114.97
 1413.65  112.281509.565  114.711565.675  112.591574.793  108.931595.159  109.74
 1601.27  112.641626.002  123.93  1816.9  123.89 1840.02  115.51 1865.04  114.37
 1907.14  106.82 1976.16  109.08  1983.3  107.25 1998.07  113.49 2069.47  113.18
 2087.14  116.06 2102.41  111.14  2162.9  109.56 2192.24  110.06 2212.67  117.24
 2232.36  116.97 2253.32   113.6 2272.02  115.73 2387.19  116.96 2744.08  116.75
#Mann= 5 ,-1 , 0
       0    .045       0  636.35     .04       0 1245.81     .09       0
1565.675     .05       0 1601.27     .09       0
#XS Ineff= 2 , 0
       01561.562  123.071605.159       0  123.07
Permanent Ineff=
       F       F
Bank Sta=1565.675,1601.27
XS Rating Curve= 0 ,0
Exp/Cntr=0.5,0.3

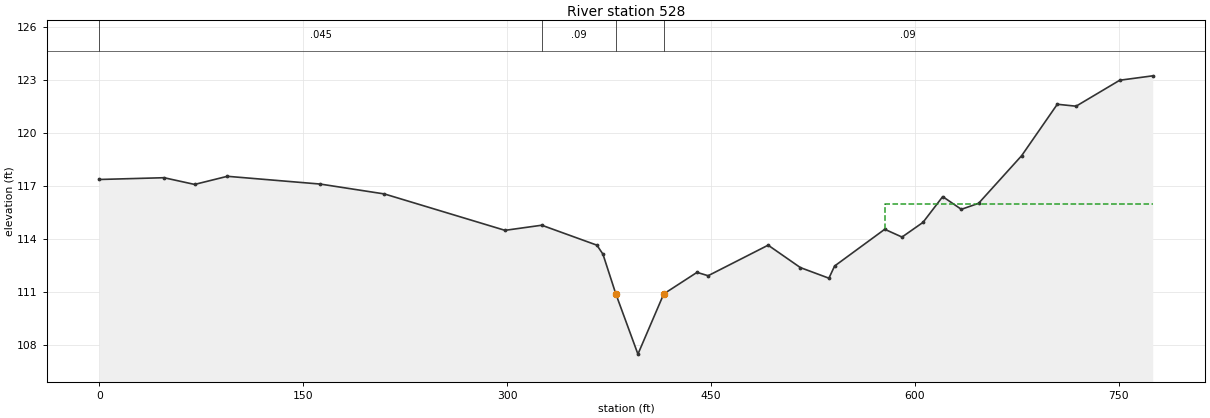
Type RM Length L Ch R = 1 ,528     ,629.65,527.66,413.11
XS GIS Cut Line= 4
 2279686.4405896  710483.4384417 2279462.0042289   710313.996421
 2279142.8776302  710249.5921386 2278978.9458367  710287.2424178
#Sta/Elev= 30
       0  117.37    47.6  117.47   70.09  117.09   94.19  117.55   162.6  117.11
  209.77  116.55  298.45  114.49  325.49  114.78  366.06  113.65   370.5  113.14
  379.89  110.91  396.24  107.48  415.23  110.89   439.7  112.11  447.88  111.92
  492.03  113.65  515.76  112.38  536.74  111.78  540.93  112.47  577.81  114.55
  590.53  114.11  605.94  114.94  620.46   116.4  634.16  115.68  646.85  116.02
  678.56  118.72  704.76  121.63  718.58  121.52  750.69  122.99  774.98  123.24
#Mann= 4 ,-1 , 0
       0    .045       0  325.49     .09       0  379.89     .05       0
  415.23     .09       0
#XS Ineff= 2 , 0
       0                  577.81       0     116
Permanent Ineff=
       F       F
Bank Sta=379.89,415.23
XS Rating Curve= 0 ,0
Exp/Cntr=0.3,0.1
Stream Node=Marsh Swamp     ,Main            , 0 , 0 ,Upstream end
Stream Node=Marsh Swamp     ,Main            , 0 , 1 ,Downstream end

Chan Stop Cuts=-1
Use User Specified Reach Order=0
User Specified Reach Order=Marsh Swamp     ,Main