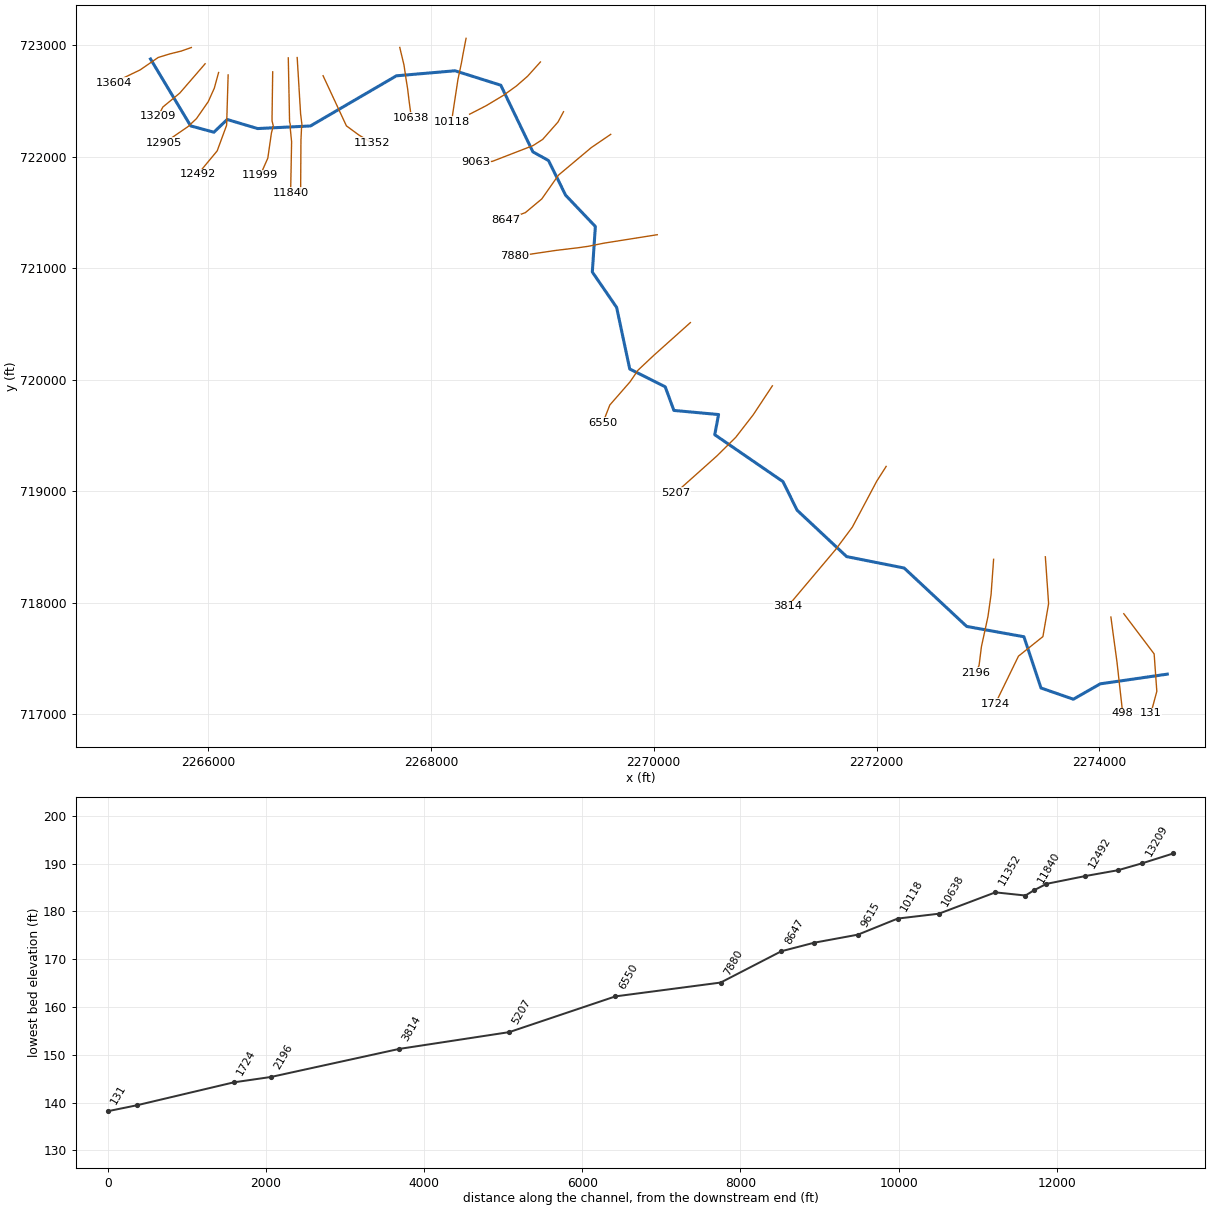
--- DTL_Marsh_Swamp_Tri.prj (project) ---

Proj Title=DTL_Marsh_Swamp_Tri
Current Plan=p01
Default Exp/Contr=0.3,0.1
English Units
Geom File=g01
Flow File=f01
Flow File=f02
Plan File=p01
Plan File=p02
Y Axis Title=Elevation
X Axis Title(PF)=Main Channel Distance
X Axis Title(XS)=Station
BEGIN DESCRIPTION:
END DESCRIPTION:
DSS Export Rating Curves= 0
DSS Export Rating Curve Sorted= 0
DSS Export Volume Flow Curves= 0
DXF OffsetX= 0
DXF OffsetY= 0
DXF ScaleX= 1
DXF ScaleY= 10

--- DTL_Marsh_Swamp_Tri.p01 (plan) ---

Plan Title=DTL_Marsh_Swamp_Tri
Program Version=4.00
Short Identifier=Plan 01
Geom File=g01
Flow File=f01
Subcritical Flow
K Sum by GR= 0
Std Step Tol= 0.01
Critical Tol= 0.01
Num of Std Step Trials= 20
Max Error Tol= 0.3
Flow Tol Ratio= 0.001
Split Flow NTrial= 30
Split Flow Tol= 0.02
Split Flow Ratio= 0.02
Log Output Level= 0
Friction Slope Method= 1
Unsteady Friction Slope Method= 2
Unsteady Bridges Friction Slope Method= 1
Parabolic Critical Depth
Global Vel Dist= 0 , 0 , 0
Global Log Level= 0
CheckData=True
Encroach Param=-1 ,10,10, 2
Encroach River=Marsh Swamp
Encroach Reach=Marsh Swamp
Encroach Node=13604
       4       1
Encroach Node=13209
       4       1
Encroach Node=12905
       4       1
Encroach Node=12492
       4       1
Encroach Node=11999
       4       1
Encroach Node=11840
       1  570.71  640.71
Encroach Node=11733
       1  596.46  639.44
Encroach Node=11352
       1     245     430
Encroach Node=10638
       1     230  341.42
Encroach Node=10118
       1     250     350
Encroach Node=9615
       1     380     475
Encroach Node=9063
       1  426.68     520
Encroach Node=8647
       1     595     710
Encroach Node=7880
       1     485     580
Encroach Node=6550
       4       1
Encroach Node=5207
       4       1
Encroach Node=3814
       1     810     915
Encroach Node=2196
       1     584     735
Encroach Node=1724
       1     865    1033
Encroach Node=498
       1     520     670
Encroach Node=131
       4       1
Computation Interval=1HOUR
Output Interval=1HOUR
Run HTab= 0
Run UNet= 0
Run PostProcess= 0
Run WQNet= 0
UNET Theta= 1
UNET Theta Warmup= 1
UNET ZTol= 0.02
UNET ZSATol= 0.05
UNET MxIter= 20
UNET MaxInSteps= 0
UNET DtIC= 0
UNET DtMin= 0
UNET MaxCRTS= 20
UNET WFStab= 2
UNET SFStab= 1
UNET WFX= 1
UNET SFX= 1
UNET DSS MLevel= 4
UNET DZMax Abort= 100
UNET Convert EG Bridges= 0
UNET Use Existing IB Tables=-1
UNET Froude Reduction=False
UNET Froude Limit= 1
UNET Froude Power= 10
UNET Time Slicing=0,0, 5
Instantaneous Interval=1HOUR
Write IC File= 0
Echo Input=False
Echo Output=False
Write Detailed= 0
Detailed Automatic Start=False, 10
WQ ULTIMATE=-1
WQ Max Comp Step=1HOUR
WQ Output Interval=15MIN
WQ Output Selected Increments= 0
WQ Output face flow=0
WQ Output face velocity=0
WQ Output face area=0
WQ Output face dispersion=0
WQ Output cell volume=0
WQ Output cell surface area=0
WQ Output cell continuity=0
WQ Output face conc=0
WQ Output face dconc_dx=0
WQ Output face courant=0
WQ Output face peclet=0
WQ Output face adv mass=0
WQ Output face disp mass=0
WQ Output cell mass=0
WQ Output cell source sink temp=0
WQ Output cell source sink nsm=0
WQ Output MaxMinRange=-1
WQ Daily Max Min Mean=-1
WQ Daily Range=0
WQ Daily Time=0
WQ Create Restart=0
WQ Fixed Restart=0
WQ System Summary=False
Sorting and Armoring Iterations= 10
XS Update Threshold= 0.02
Hydraulics Update Threshold= 0.02
Energy Slope Method= 1
Volume Change Method= 0
XS Weighting Method= 0
Number of US Weighted Cross Sections= 1
Number of DS Weighted Cross Sections= 1
Upstream XS Weight=0.25
Main XS Weight=0.5
Downstream XS Weight=0.25
Number of DS XS's Weighted with US Boundary= 1
Upstream Boundary Weight= 1
Weight of XSs Associated with US Boundary= 0
Number of US XS's Weighted with DS Boundary= 1
Downstream Boundary Weight= 0.5
Weight of XSs Associated with DS Boundary= 0.5
Sediment Output Level= 4
Mass or Volume Output= 0
Output Increment Type= 1
Profile and TS Output Increment= 10
XS Output Flag= 0
XS Output Increment= 10
Disregard all LS=0
Disregard all Conn=0
Disregard all Breaches=0
Disregard all Pumps=0

--- DTL_Marsh_Swamp_Tri.p02 (plan) ---

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Plan Title=DTL_Marsh_Swamp_Tri_future
Short Identifier=DTL_Marsh_Sw
Geom File=g01
Flow File=f02
Encroach Param=-1 ,0,0, 0

--- DTL_Marsh_Swamp_Tri.f01 (steady flow) ---

Flow Title=DTL_Marsh_Swamp_Tri
Program Version=4.00
Number of Profiles= 6
Profile Names=100-yr,FW,10-yr,25-yr,50-yr,500-yr
River Rch & RM=Marsh Swamp,Marsh Swamp     ,13604
     760     760     320     470     600    1230
River Rch & RM=Marsh Swamp,Marsh Swamp     ,11352
     870     870     370     540     690    1400
River Rch & RM=Marsh Swamp,Marsh Swamp     ,7880
    1060    1060     460     660     850    1680
River Rch & RM=Marsh Swamp,Marsh Swamp     ,3814
    1140    1140     490     710     910    1800
Boundary for River Rch & Prof#=Marsh Swamp,Marsh Swamp     , 1
Up Type= 0
Dn Type= 3
Dn Slope=4.118549E-03
Boundary for River Rch & Prof#=Marsh Swamp,Marsh Swamp     , 2
Up Type= 0
Dn Type= 3
Dn Slope=4.118549E-03
Boundary for River Rch & Prof#=Marsh Swamp,Marsh Swamp     , 3
Up Type= 0
Dn Type= 3
Dn Slope=4.118549E-03
Boundary for River Rch & Prof#=Marsh Swamp,Marsh Swamp     , 4
Up Type= 0
Dn Type= 3
Dn Slope=4.118549E-03
Boundary for River Rch & Prof#=Marsh Swamp,Marsh Swamp     , 5
Up Type= 0
Dn Type= 3
Dn Slope=4.118549E-03
Boundary for River Rch & Prof#=Marsh Swamp,Marsh Swamp     , 6
Up Type= 0
Dn Type= 3
Dn Slope=4.118549E-03
DSS Import GetInterval= 0
DSS Import GetPeak= 0
DSS Import FillOption= 0

--- DTL_Marsh_Swamp_Tri.f02 (steady flow) ---

Flow Title=DTL_Marsh_Swamp_Tri_Future
Program Version=4.00
Number of Profiles= 3
Profile Names=100-yr-10%,100-yr-20%,100-yr-35%
River Rch & RM=Marsh Swamp,Marsh Swamp     ,13604
    1320    1700    2070
River Rch & RM=Marsh Swamp,Marsh Swamp     ,11733
    1510    1940    2370
River Rch & RM=Marsh Swamp,Marsh Swamp     ,7880
    1820    2340    2860
River Rch & RM=Marsh Swamp,Marsh Swamp     ,3814
    1960    2510    3060
Boundary for River Rch & Prof#=Marsh Swamp,Marsh Swamp     , 1
Up Type= 0
Dn Type= 3
Dn Slope=4.118549E-03
Boundary for River Rch & Prof#=Marsh Swamp,Marsh Swamp     , 2
Up Type= 0
Dn Type= 3
Dn Slope=4.118549E-03
Boundary for River Rch & Prof#=Marsh Swamp,Marsh Swamp     , 3
Up Type= 0
Dn Type= 3
Dn Slope=4.118549E-03
DSS Import GetInterval= 0
DSS Import GetPeak= 0
DSS Import FillOption= 0

--- DTL_Marsh_Swamp_Tri.g01 (geometry) ---

Geom Title=DTL_March_Swamp_Tri
Program Version=4.00

River Reach=Marsh Swamp     ,Marsh Swamp
Reach XY= 30
2265484.45091711722877.7857318522265844.58851229722277.709831178
 2266052.8850573722220.9447648972266172.26739131722334.972741738
2266445.33960724722253.6658365132266919.67509583722277.120967686
2267690.58148959722726.9675221592268216.61173475722772.314957082
2268627.45949517722642.6212931722268915.46773542 722044.72175467
2269055.62774399721966.8550832272269209.41442008 721655.38839753
 2269476.1077697721375.0683803862269448.85443471 720966.26835537
2269666.88111471720648.9616693112269784.72603446720095.909347743
2270102.93447474719936.4816257362270180.80114615719724.294946074
2270581.81450401719687.3082771452270547.46988989719506.392693713
2271159.66026144719085.568497598 2271286.6330792 718828.90201591
2271731.03794146718412.6125632972272247.09175093718310.127360359
2272808.49299532 717785.911012622273321.82595868717693.402245358
2273475.10028873717233.5792552082273765.32387227717132.907949656
2274006.57222606717270.7641518562274608.78616187  717357.8312269

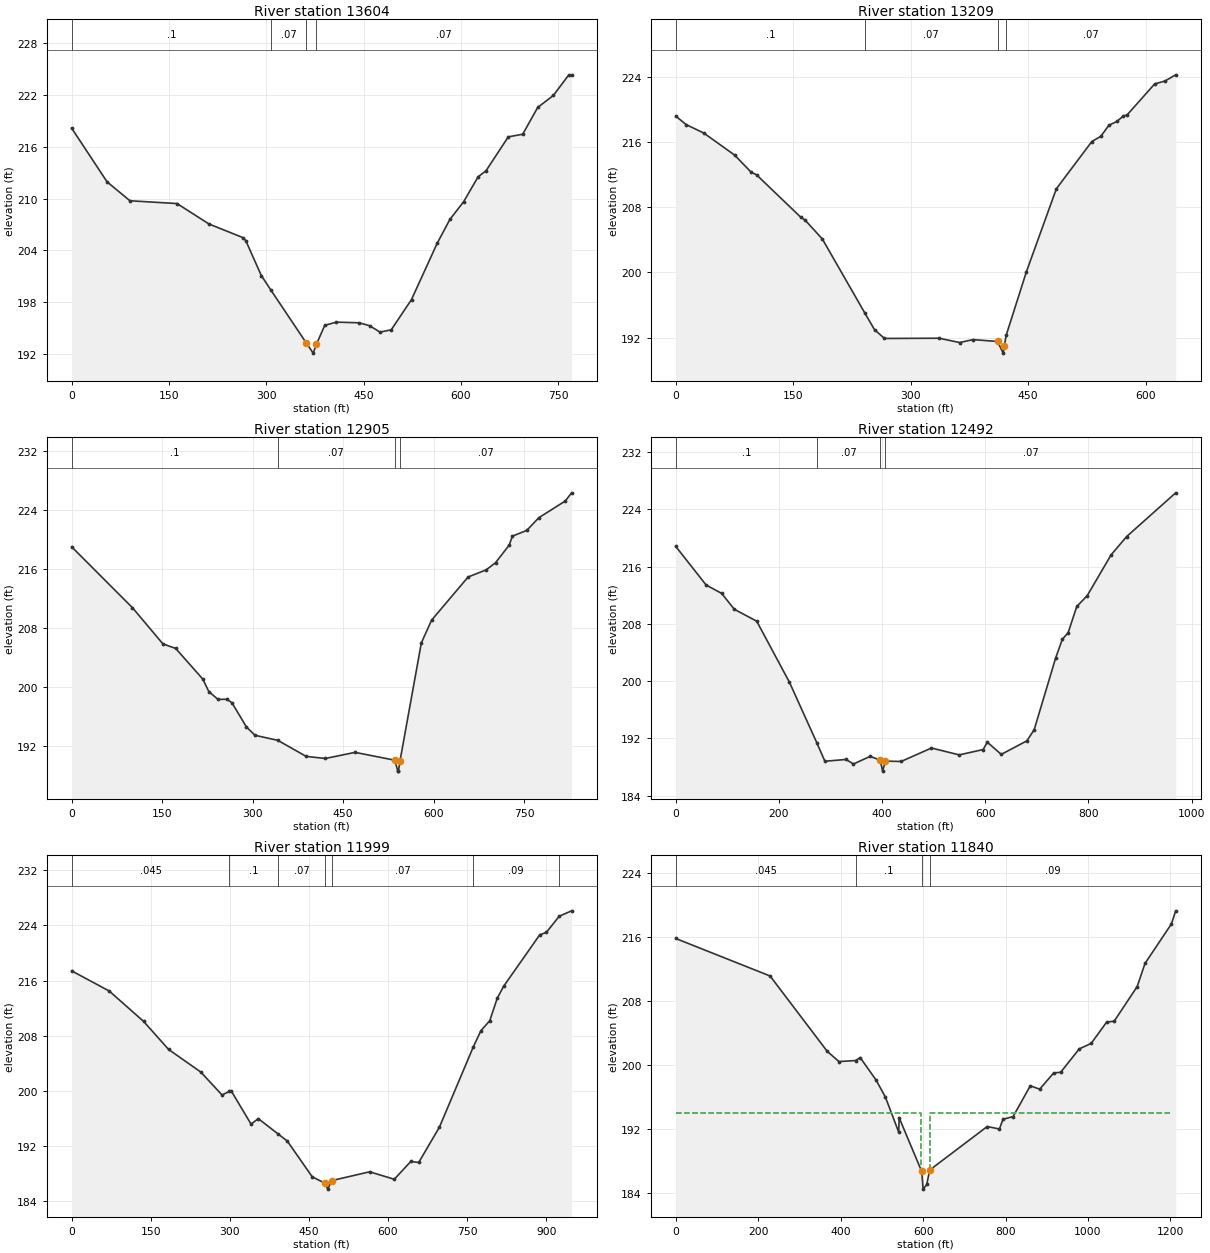
Type RM Length L Ch R = 1 ,13604   ,389.43,394.49,422.72
XS GIS Cut Line= 6
2265850.48429279722980.9314862792265760.23142451722949.175847441
2265655.77208626 722923.269931572265552.98409739722891.514292732
2265391.69887909  722780.36955682265154.36726259 722665.88212207
#Sta/Elev= 30
       0  218.12   54.52  211.93   89.79  209.74  162.31  209.42  211.57  207.06
  263.73  205.49  268.24  205.15  292.21  201.11  307.06  199.42   361.3  193.35
  372.16  192.15  377.25  193.19  389.96  195.36  407.95  195.73  442.97  195.65
  459.05  195.32  475.04  194.58  492.42  194.84  523.66  198.34   563.1  204.81
  582.82  207.59  603.91  209.62  626.32  212.51  638.43   213.2  672.81  217.12
  694.98  217.42  718.17  220.52  742.23   221.9  765.61  224.23  770.33  224.28
#Mann= 4 ,-1 , 0
       0      .1       0  307.06     .07       0   361.3    .055       0
  377.25     .07       0
Bank Sta=361.3,377.25
XS Rating Curve= 0 ,0
Exp/Cntr=0.3,0.1

Type RM Length L Ch R = 1 ,13209   ,287.08,304.42,284.71
XS GIS Cut Line= 4
2265974.16414925722834.9669709352265746.86062923722572.007996738
2265595.32494919722447.2139073012265550.75563151722364.017847657
#Sta/Elev= 30
       0  219.19    13.3  218.15   35.99   217.1   75.08  214.41   96.09  212.32
  103.17  211.98  159.88  206.75  165.07  206.43  187.18   204.1  241.71  194.96
  253.82  192.96  266.48  191.89   336.3  191.92  362.43  191.39  379.49  191.75
  410.81  191.52  418.05  190.09   419.6  190.99  421.77  192.26  447.78  200.11
  485.92  210.27   531.2  216.07  542.68  216.71     553  218.07  563.08  218.53
  571.45   219.2  576.45  219.36  611.39  223.14  624.59   223.5  638.27  224.26
#Mann= 4 ,-1 , 0
       0      .1       0  241.71     .07       0  410.81    .055       0
  421.77     .07       0
Bank Sta=410.81,419.6
XS Rating Curve= 0 ,0
Exp/Cntr=0.3,0.1

Type RM Length L Ch R = 1 ,12905   ,342.77,413.02,339.94
XS GIS Cut Line= 6
2266095.21317804722756.8468613772266056.58643603722615.710688785
2266001.61761092 722493.887887182265896.13689248722342.352207139
2265820.36905244722271.0412988812265606.27125612722123.797479063
#Sta/Elev= 30
       0  219.01  100.71  210.77  151.19  205.87  172.41  205.25  217.33   201.1
  227.32  199.41  242.53  198.35   257.1  198.37  265.56  197.91  289.64  194.62
   303.9  193.49  341.59  192.81  388.56  190.64  420.25  190.35  469.69  191.18
  535.46  190.12  540.58  188.64  541.55  188.64  544.08     190  579.54  206.01
   596.5  209.08  656.96  214.92  687.14   215.9  702.58  216.87  725.09  219.24
  730.41  220.46  754.19  221.23   774.2  222.95  817.99  225.21   828.5  226.32
#Mann= 4 ,-1 , 0
       0      .1       0  341.59     .07       0  535.46    .055       0
  544.08     .07       0
Bank Sta=535.46,544.08
XS Rating Curve= 0 ,0
Exp/Cntr=0.3,0.1

Type RM Length L Ch R = 1 ,12492   ,425.16,492.8,431.53
XS GIS Cut Line= 4
2266180.83372599722735.0986850862266167.29785915722283.793075889
2266082.61615558722053.518267959 2265908.7958167 721844.04247497
#Sta/Elev= 30
       0  218.83    58.9  213.43   89.05  212.26  113.49  210.04   156.9  208.38
  220.31  199.85  273.47  191.38  289.08   188.8  329.81  189.05  344.52  188.42
  376.74  189.48  396.44  188.96  400.88  187.42  406.52188.8185  436.82  188.77
  495.66  190.65  549.57  189.69   595.9  190.44  603.85  191.47  630.95  189.76
  680.53  191.65  694.68  193.19  736.36  203.23  749.25  205.83  760.67  206.79
  777.37  210.44  797.54  211.94  843.79  217.64  874.01  220.21  969.06  226.32
#Mann= 4 ,-1 , 0
       0      .1       0  273.47     .07       0  396.44    .055       0
  406.52     .07       0
Bank Sta=396.44,406.52
XS Rating Curve= 0 ,0
Exp/Cntr=0.3,0.1

Type RM Length L Ch R = 1 ,11999   ,159.15,159.38,178.69
XS GIS Cut Line= 6
2266580.67641883722762.6204045412266574.40192115722324.700932458
2266585.91797477722277.1209676862266569.39827096722214.882771552
2266536.82599215721988.1782910082266469.42089778721835.283808634
#Sta/Elev= 30
       0  217.41   71.22  214.49  136.41  210.09  183.91  206.02  244.75  202.76
  285.16  199.43  299.35  199.94  302.51  200.03  340.29   195.2  353.99     196
  392.28  193.73  408.99  192.75  456.22  187.57  480.06  186.65  485.73  185.78
  493.45  187.02  565.24  188.29   611.9  187.21  643.28  189.79  658.25  189.64
  697.66  194.78   761.9  206.41  776.25  208.74  792.99  210.19  807.31  213.46
  819.61  215.21  887.88  222.64  900.21  222.97   924.8  225.33  948.22  226.11
#Mann= 7 ,-1 , 0
       0    .045       0  299.35      .1       0  392.28     .07       0
  480.06    .055       0  493.45     .07       0   761.9     .09       0
   924.8    .055       0
Bank Sta=480.06,493.45
XS Rating Curve= 0 ,0
Exp/Cntr=0.5,0.3

Type RM Length L Ch R = 1 ,11840   ,103.98,106.38,89.63
BEGIN DESCRIPTION:
Surveyed Section
END DESCRIPTION:
XS GIS Cut Line= 6
2266720.56419975722887.9490223382266732.08849999722315.050700009
     2266738.373722291.413499996    2266736.5175722273.419100001
2266750.26730002722134.5324000122266741.53871326721677.307624236
#Sta/Elev= 30
       0  215.77  228.84  211.08  367.47  201.66  395.88  200.38  436.23  200.51
  447.37  200.88  485.67  198.09  508.41  195.96  540.82  191.56 541.902  193.36
 596.637  186.64 600.109  184.43 608.937  185.01 615.836  186.81 755.604  192.26
  785.15  191.95  793.77  193.16  818.31   193.5  860.07  197.35  882.83  196.93
  916.74  198.95  933.87  199.05  978.75  201.96 1007.88  202.66 1045.36  205.32
 1063.58  205.43  1119.4  209.76 1138.32  212.65 1202.39  217.59 1212.77  219.23
#Mann= 4 ,-1 , 0
       0    .045       0  436.23      .1       0 596.637    .055       0
 615.836     .09       0
#XS Ineff= 2 ,-1
       0  594.71  193.89  617.71    1200  193.89
Permanent Ineff=
       F       F
Bank Sta=596.637,615.836
XS Rating Curve= 0 ,0
Exp/Cntr=0.5,0.3

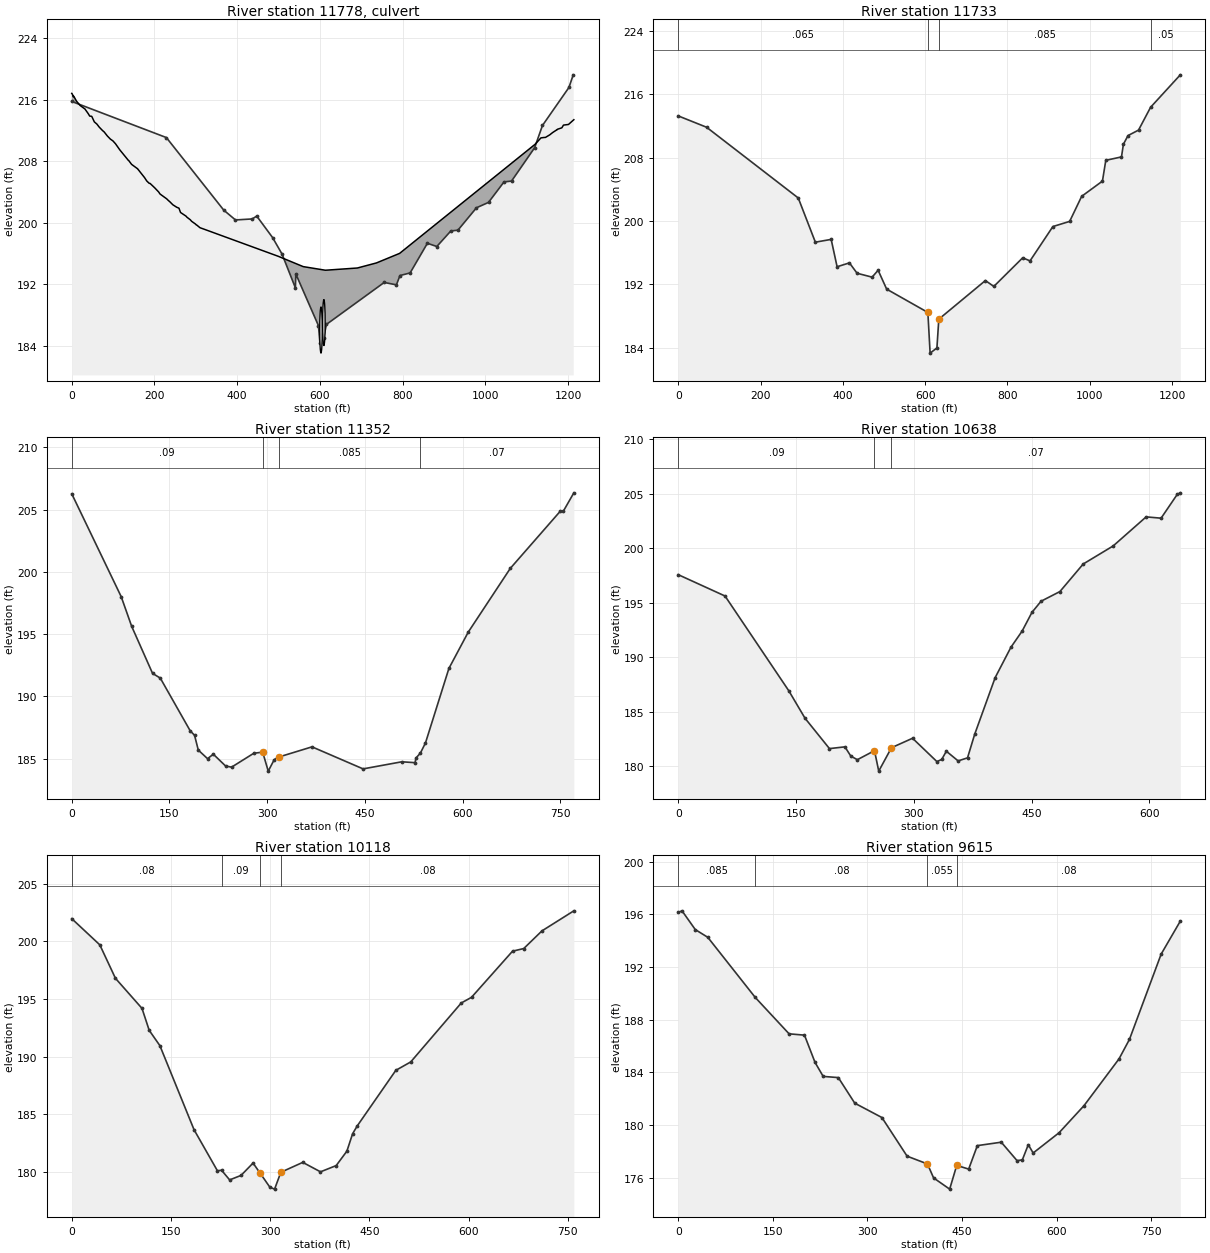
Type RM Length L Ch R = 2 ,11778   ,,,
Bridge Culvert--1,0,-1,-1, 0
Deck Dist Width WeirC Skew NumUp NumDn MinLoCord MaxHiCord MaxSubmerge Is_Ogee
53.27,21.6,2.6,0, 79, 79, , , 0.95, 0, 1,1,,
       0     .85    1.89    3.43    4.85   11.41   20.25   28.04   31.74   39.53
   43.39   48.26   54.56   57.75   60.62   66.52   74.47   78.38   85.99   93.39
   99.49  105.72  116.07  135.78  136.47  136.63  137.68  144.66  158.34  158.66
  176.01  181.38  187.25  189.47  200.07  210.23   213.1  216.75  229.62  233.16
  237.44  240.73  244.49  253.81  259.23  263.06  276.41  278.67  286.69  289.75
  299.38  301.02  301.53  302.21  310.14  321.03 499.305 559.706 613.465 690.723
 736.924 792.895  1118.7 1120.34 1134.66 1141.79 1145.58 1156.09 1162.64 1172.55
 1173.35 1173.75  1174.8 1185.24 1189.15  1197.8 1201.21 1212.02 1214.23
  216.82  216.76  216.67  216.38  216.45  215.81  215.25  214.94   214.8  214.21
  213.87  213.84  213.12  212.97  212.84  212.43  211.99  211.81  211.29  210.88
  210.65  210.28  209.49  208.19  208.14  208.13   208.1   207.6  207.06  207.06
  205.88  205.44  205.14  205.12  204.58  204.01  203.77  203.62  203.12  202.93
  202.73  202.55  202.35  202.03  201.91  201.35  200.87  200.73   200.4  200.21
  199.84  199.74  199.73  199.72  199.37  199.16  195.66  194.32  193.85  194.14
   194.8  196.04  210.13   210.2  211.04  211.09   211.1  211.44  211.72  212.07
  212.11   212.1  212.16  212.35   212.7  212.76  212.78   213.3   213.4
                                                                                
                                                                                
                                                                                
                                                                                
                                                                                
                                                                                
                                                                                
                                                                        
       0     .85    1.89    3.43    4.85   11.41   20.25   28.04   31.74   39.53
   43.39   48.26   54.56   57.75   60.62   66.52   74.47   78.38   85.99   93.39
   99.49  105.72  116.07  135.78  136.47  136.63  137.68  144.66  158.34  158.66
  176.01  181.38  187.25  189.47  200.07  210.23   213.1  216.75  229.62  233.16
  237.44  240.73  244.49  253.81  259.23  263.06  276.41  278.67  286.69  289.75
  299.38  301.02  301.53  302.21  310.14  321.03 499.305 559.706 613.465 690.723
 736.924 792.895  1118.7 1120.34 1134.66 1141.79 1145.58 1156.09 1162.64 1172.55
 1173.35 1173.75  1174.8 1185.24 1189.15  1197.8 1201.21 1212.02 1214.23
  216.82  216.76  216.67  216.38  216.45  215.81  215.25  214.94   214.8  214.21
  213.87  213.84  213.12  212.97  212.84  212.43  211.99  211.81  211.29  210.88
  210.65  210.28  209.49  208.19  208.14  208.13   208.1   207.6  207.06  207.06
  205.88  205.44  205.14  205.12  204.58  204.01  203.77  203.62  203.12  202.93
  202.73  202.55  202.35  202.03  201.91  201.35  200.87  200.73   200.4  200.21
  199.84  199.74  199.73  199.72  199.37  199.16  195.66  194.32  193.85  194.14
   194.8  196.04  210.13   210.2  211.04  211.09   211.1  211.44  211.72  212.07
  212.11   212.1  212.16  212.35   212.7  212.76  212.78   213.3   213.4
                                                                                
                                                                                
                                                                                
                                                                                
                                                                                
                                                                                
                                                                                
                                                                        
BR Coef=-1 , 0 , 0 ,, 0 ,,,0.8,0,,0,
WSPro=,,,, 1 ,,,, 0 ,,,, 0 ,,,,-1 ,-1 ,-1 , 0 , 0 , 0 , 0 , 0
Culvert=1,6,,65,0.24,0.9,1,2,3,183.0823,602.71,184.4601,614.439,Culvert #1  , 0 ,28.82
Culvert Bottom n=0.24
Culvert=1,6,,65,0.24,0.9,1,2,3,184.0503,609.71,184.0506,621.439,Culvert #2  , 0 ,28.82
Culvert Bottom n=0.24
BC Design=,, 0 ,, 0 ,,,,,,
BC Use User HTab Curves=0
BC User HTab FreeFlow(D)= 0

Type RM Length L Ch R = 1 ,11733   ,350.21,380.91,426.89
BEGIN DESCRIPTION:
Surveyed Section
END DESCRIPTION:
XS GIS Cut Line= 6
2266800.42841242722891.0123072122266831.08400002722385.373000011
2266844.03270002722280.6035999952266839.37620004     722260.3081
2266834.20320003722147.2227000152266831.33907719721673.614535689
#Sta/Elev= 30
       0  213.25   68.94  211.82   291.7   202.9  333.23  197.33  371.67  197.68
  386.07  194.23  416.02  194.72  434.66  193.41  471.16  192.92  485.78  193.79
 506.501  191.41 606.648  188.47 612.132  183.34 628.648  183.99 633.255  187.62
 746.446  192.49  766.95  191.75  837.14  195.36  854.96  194.97  910.49   199.3
  951.25  199.95  980.44  203.11 1030.93  205.03 1039.08  207.65 1077.19  208.08
 1081.89  209.68 1093.05  210.77 1118.61  211.46 1147.93  214.34 1220.16  218.43
#Mann= 4 ,-1 , 0
       0    .065       0 606.648    .055       0 633.255    .085       0
 1147.93     .05       0
#XS Ineff= 2 , 0
       0  596.46     185  639.44       0     185
Permanent Ineff=
       F       F
Bank Sta=606.648,633.255
XS Rating Curve= 0 ,0
Exp/Cntr=0.5,0.3

Type RM Length L Ch R = 1 ,11352   ,692.24,714.64,665.42
XS GIS Cut Line= 4
2267032.70554318722727.7847991292267242.31894638722277.732492149
2267351.23571476722197.586190924 2267470.4276499722125.660023123
#Sta/Elev= 30
       0  206.27    75.9  198.01   91.97  195.63  124.05  191.85  135.94  191.47
  181.81  187.24  188.52  186.88  194.27  185.69   208.5     185  217.32  185.36
  236.23  184.41   245.4  184.32  279.66  185.44  293.17  185.52  301.67     184
  310.84  184.92  317.72  185.13  368.88  185.95   447.3  184.18  506.77  184.75
  527.03  184.68  528.63  185.06  535.32  185.45  543.13  186.27  579.08  192.25
  608.73  195.16   673.3  200.28  750.36  204.89  754.93  204.89  770.91  206.35
#Mann= 4 ,-1 , 0
       0     .09       0  293.17    .055       0  317.72    .085       0
  535.32     .07       0
Bank Sta=293.17,317.72
XS Rating Curve= 0 ,0
Exp/Cntr=0.3,0.1

Type RM Length L Ch R = 1 ,10638   ,517.11,519.36,470.67
XS GIS Cut Line= 6
2267721.05195659722981.5315351192267758.64569339722824.522399083
2267776.33686364722705.1069998292267791.81663758722607.805563435
 2267805.0850153722497.2357493192267824.98758186722351.283594698
#Sta/Elev= 30
       0  197.58   59.58  195.62  140.81  186.91  161.45  184.39  192.56   181.6
  212.26  181.76  219.77  180.91   228.1  180.58  249.92  181.41  255.33  179.53
  271.52  181.68  298.38  182.55  329.34  180.41  335.51   180.6  341.42  181.36
  356.42  180.47   368.4  180.75  377.48  182.91  403.57  188.12  423.65  190.91
  437.95   192.4  450.46  194.12  462.04  195.14  486.07  196.03   515.7  198.56
  553.86  200.22  595.85  202.89  614.87  202.77   635.4  204.95  639.36   205.1
#Mann= 3 ,-1 , 0
       0     .09       0  249.92    .055       0  271.52     .07       0
Bank Sta=249.92,271.52
XS Rating Curve= 0 ,0
Exp/Cntr=0.3,0.1

Type RM Length L Ch R = 1 ,10118   ,524.43,503.75,404.18
XS GIS Cut Line= 6
2268315.91755649 723063.353197562268289.38080111722926.246628076
2268273.90102711722840.0021730812268242.94147916 722694.05001843
2268223.03891265722563.5776377922268185.44517584722315.901254162
#Sta/Elev= 30
       0  201.97   42.39   199.7   66.02   196.8  106.18  194.19  117.05  192.29
   133.2  190.96  184.85  183.67  220.19  180.11   226.4  180.16  238.66  179.32
  255.87  179.71  274.05  180.78  284.05  179.96  299.56  178.68  306.61  178.52
  316.03  179.98   349.2  180.84  375.99  180.02  399.69  180.56  415.87  181.81
  424.52  183.32  431.41  183.99  489.86  188.82  512.43  189.55  588.81  194.66
  604.27  195.15  666.26  199.15  683.23  199.38  710.75  200.91  758.97  202.65
#Mann= 4 ,-1 , 0
       0     .08       0   226.4     .09       0  284.05    .055       0
  316.03     .08       0
Bank Sta=284.05,316.03
XS Rating Curve= 0 ,0
Exp/Cntr=0.3,0.1

Type RM Length L Ch R = 1 ,9615    ,528.45,551.55,509.44
XS GIS Cut Line= 6
2268982.93220671722851.0868010222268868.38790935722723.658150226
2268767.15370335722635.3082976792268650.01680152722551.051929727
2268495.88929915722458.5754282772268347.92689683722382.539193779
#Sta/Elev= 30
       0  196.14    6.01  196.26      27  194.84   46.88  194.25  122.12  189.69
  175.76  186.93  200.18  186.83  216.93  184.76  229.84   183.7  253.84  183.61
   279.9  181.67  322.98  180.58  362.88  177.65  395.15  177.06  404.92     176
  430.39  175.15  441.58  176.95  460.54  176.67  474.27  178.45  512.21  178.71
  537.25  177.31  545.61  177.37  555.06  178.52  562.77  177.89  603.93  179.43
  643.37  181.48  698.93  185.03  715.47  186.51  765.76  192.98   796.1  195.48
#Mann= 4 ,-1 , 0
       0    .085       0  122.12     .08       0  395.15    .055       0
  441.58     .08       0
Bank Sta=395.15,441.58
XS Rating Curve= 0 ,0
Exp/Cntr=0.3,0.1

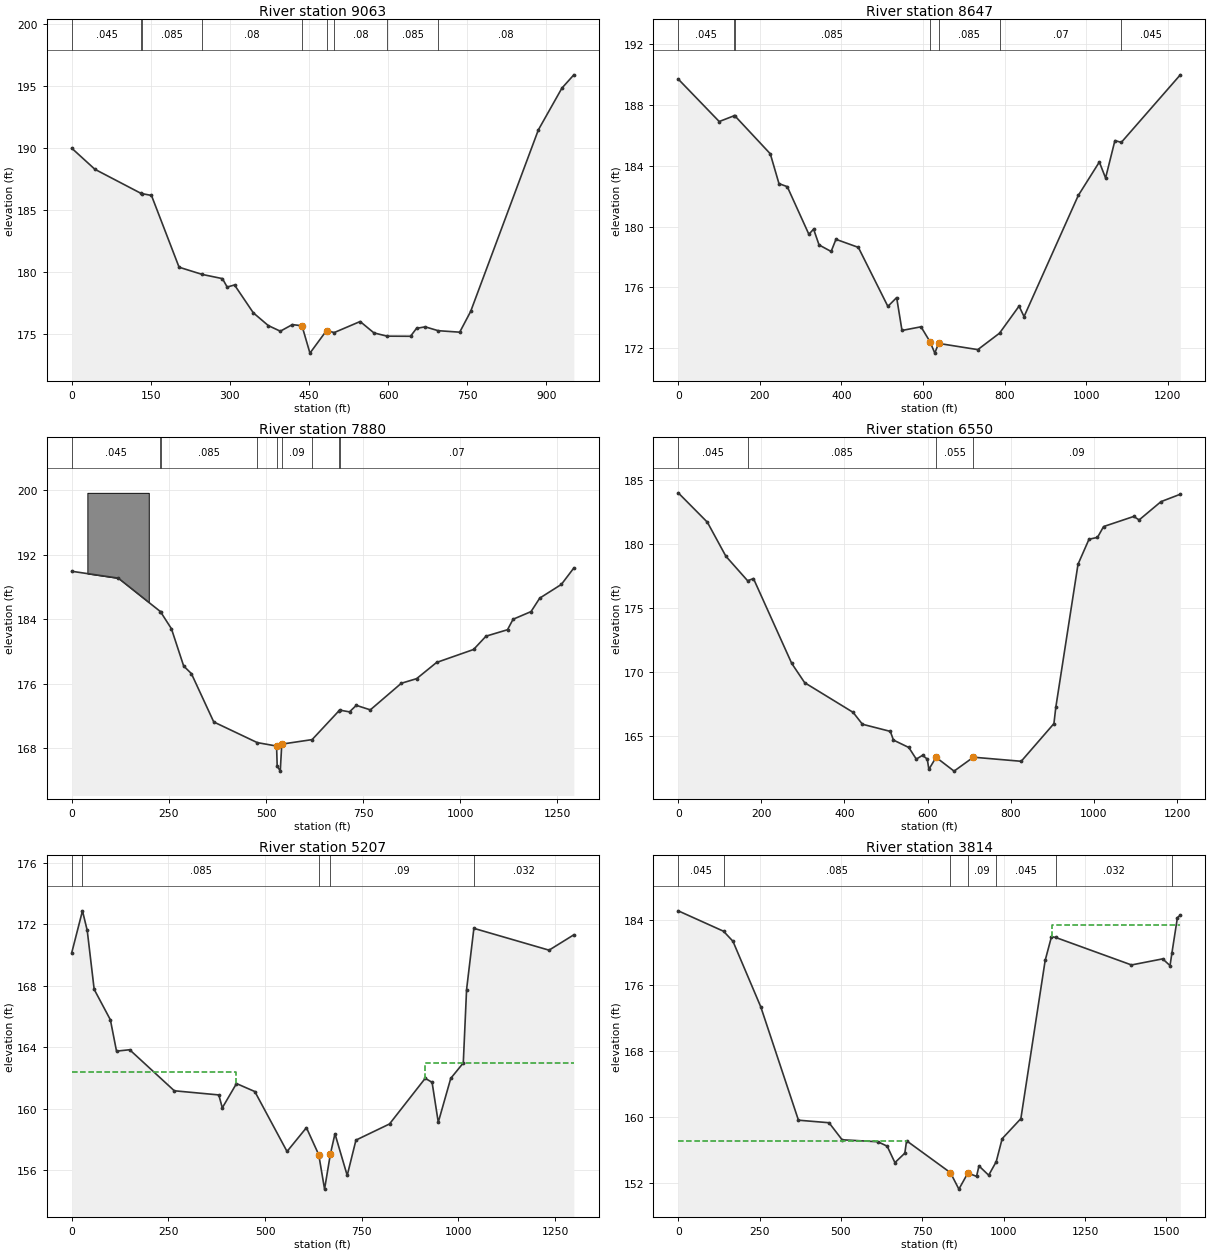
Type RM Length L Ch R = 1 ,9063    ,352.38,416.24,445.38
XS GIS Cut Line= 6
2269190.49057654722405.1445607842269141.16977578722312.668059364
2269003.48254032722156.4855236112268917.17113899722100.999622762
    2268551.3752721959.2023205612268407.52286446721950.982187107
#Sta/Elev= 30
       0     190   43.87   188.3  131.72186.3489  132.77  186.34  151.18  186.19
  203.56   180.4  247.34  179.82  285.77  179.48  294.83   178.8  308.71  178.97
   344.4  176.72  372.86  175.69   395.6  175.24  418.37  175.77  436.68  175.68
   451.8  173.47  483.25  175.29  497.92  175.13  547.01  176.02  573.24   175.1
   598.2174.8392  642.56  174.83  654.01  175.47  670.48  175.59  695.06  175.28
  735.91  175.16  756.62  176.83  885.09  191.48  929.78  194.85   952.4  195.92
#Mann= 9 ,-1 , 0
       0    .045       0  131.72    .045       0  132.77    .085       0
  247.34     .08       0  436.68    .055       0  483.25     .08       0
  497.92     .08       0   598.2    .085       0  695.06     .08       0
Bank Sta=436.68,483.25
XS Rating Curve= 0 ,0
Exp/Cntr=0.3,0.1

Type RM Length L Ch R = 1 ,8647    ,764.94,766.84,641.2
XS GIS Cut Line= 6
2269613.82744978722201.6962576512269439.14961374722082.504322454
2269145.27984257721835.9003186372268995.26240687 721622.17684868
 2268847.3000046721498.8748467562268676.73223528721437.223845795
#Sta/Elev= 30
       0  189.69  100.49   186.9  137.87 187.289  138.36187.2884  225.68  184.78
  246.97  182.82  267.31  182.62  320.31  179.49  331.85  179.83  345.27  178.79
  374.86  178.36  386.67  179.16  441.57  178.63     514  174.75  535.48  175.33
   548.6  173.17  595.19  173.41  617.07  172.44  629.04  171.68  638.18  172.32
  734.46  171.91  787.68  172.99  835.62  174.77  847.84  174.08  980.75  182.04
 1032.42  184.24 1047.74  183.19 1070.63  185.65 1086.31  185.53 1230.95  189.97
#Mann= 7 ,-1 , 0
       0    .045       0  137.87    .045       0  138.36    .085       0
  617.07    .055       0  638.18    .085       0  787.68     .07       0
 1086.31    .045       0
Bank Sta=617.07,638.18
XS Rating Curve= 0 ,0
Exp/Cntr=0.3,0.1

Type RM Length L Ch R = 1 ,7880    ,1131.14,1329.87,1333.69
BEGIN DESCRIPTION:
Surveyed Section
END DESCRIPTION:
XS GIS Cut Line= 6
2270031.56944515721301.1815191952269552.96270001721225.284700021
2269412.86670002721197.2454999982269322.68947627721184.368341491
2269122.66691169721160.3656337412268754.62539285 721105.95949617
#Sta/Elev= 30
       0  189.92  119.68  189.07  227.93  184.93  228.84  184.87  256.52  182.79
  287.98  178.17  307.83  177.23  365.41  171.23  477.31  168.67 527.088  168.24
 528.648  165.77  536.56  165.13 540.474  168.48  618.54  169.04  688.19  172.64
  689.35   172.7  714.76  172.48  732.24  173.29  768.35  172.73  848.16  176.03
  887.51   176.6  938.86  178.61 1034.11  180.22 1066.06  181.87 1121.39  182.67
 1135.75  183.97 1181.98  184.92 1204.33  186.59 1259.99  188.29 1292.13  190.33
#Mann= 9 ,-1 , 0
       0    .045       0  227.93    .045       0  228.84    .085       0
  477.31     .09       0 527.088    .055       0 540.474     .09       0
  618.54     .07       0  688.19    .045       0  689.35     .07       0
#Block Obstruct= 1 ,-1
   40.17  198.14 199.653
Bank Sta=527.088,540.474
XS Rating Curve= 0 ,0
Exp/Cntr=0.3,0.1

Type RM Length L Ch R = 1 ,6550    ,1097.37,1342.95,1057.72
XS GIS Cut Line= 6
2270328.97906084720512.4588314742269996.06365572720214.478993535
2269858.37642026720085.0118915292269788.50528583719982.260223269
2269605.60731633719772.646820039 2269543.9563154  719614.4092509
#Sta/Elev= 30
       0  184.02   70.09  181.72   114.6  179.06  166.95  177.14  181.03  177.31
  273.08  170.67  304.25  169.16  420.73  166.84  443.13  165.91  510.32  165.35
  517.81  164.67  554.81  164.09   572.8  163.18  587.94  163.48  599.18  163.18
  603.08  162.38  620.36  163.32  663.68  162.24  710.18  163.33  825.27  163.01
  903.97  165.96  908.42  167.22  961.92  178.43  988.38  180.39 1008.77  180.53
 1023.44  181.38 1095.94  182.17 1109.01   181.9 1161.59  183.33 1208.06  183.91
#Mann= 4 ,-1 , 0
       0    .045       0  166.95    .085       0  620.36    .055       0
  710.18     .09       0
Bank Sta=620.36,710.18
XS Rating Curve= 0 ,0
Exp/Cntr=0.3,0.1

Type RM Length L Ch R = 1 ,5207    ,1409.02,1393.62,1393.79
XS GIS Cut Line= 5
 2271064.6810056719945.2696227132270892.05820291 719684.28038533
2270735.87566718719482.8871155532270567.36293124719316.429412961
2270198.80141002718987.192835033
#Sta/Elev= 30
       0  170.15   27.67  172.87   40.01  171.59   57.95  167.76   99.86  165.78
  115.76  163.74  149.81  163.83  265.23  161.16  380.37  160.89   389.4  160.05
  426.12  161.63  473.54  161.11  556.89  157.21  607.05  158.76   638.9     157
  653.96  154.76  669.05  157.05  680.87  158.36  712.54  155.65  735.15  157.95
  821.99     159  914.34  161.97  932.13  161.71  948.11  159.11  980.42  161.97
 1012.83  162.97 1021.34  167.75 1040.24  171.73 1234.66  170.31 1298.83  171.31
#Mann= 5 ,-1 , 0
       0    .035       0   27.67    .085       0   638.9    .055       0
  669.05     .09       0 1040.24    .032       0
#XS Ineff= 2 , 0
       0  425.32  162.37  913.92       0     163
Permanent Ineff=
       F       F
Bank Sta=638.9,669.05
XS Rating Curve= 0 ,0
Exp/Cntr=0.3,0.1

Type RM Length L Ch R = 1 ,3814    ,1530.4,1617.44,1589.36
XS GIS Cut Line= 5
2272085.69008252 719221.783709662272001.66205157719090.261574283
2271782.45849264718677.4282049092271632.66939403718476.491609216
 2271201.5690614717965.016638324
#Sta/Elev= 30
       0  185.07  139.18  182.59  168.11  181.37  253.74  173.39  369.45  159.62
  463.45  159.31  503.64  157.24  613.39     157  642.16  156.46   665.9  154.46
  696.39  155.61  701.73  157.12  836.55  153.24  862.52  151.24  890.22   153.2
   916.8  152.79  924.25  154.06   954.1  152.93  977.32  154.58  995.54  157.37
 1053.01  159.81 1127.75  179.05 1147.13  181.93 1160.21  181.83 1392.96  178.49
 1488.79  179.23 1511.44  178.41 1517.42  179.99 1534.11  184.24 1543.04  184.54
#Mann= 7 ,-1 , 0
       0    .045       0  139.18    .085       0  836.55    .055       0
  890.22     .09       0  977.32    .045       0 1160.21    .032       0
 1517.42    .045       0
#XS Ineff= 2 , 0
          701.62  157.13  1147.2          183.31
Permanent Ineff=
       F       F
Bank Sta=836.55,890.22
XS Rating Curve= 0 ,0
Exp/Cntr=0.3,0.1

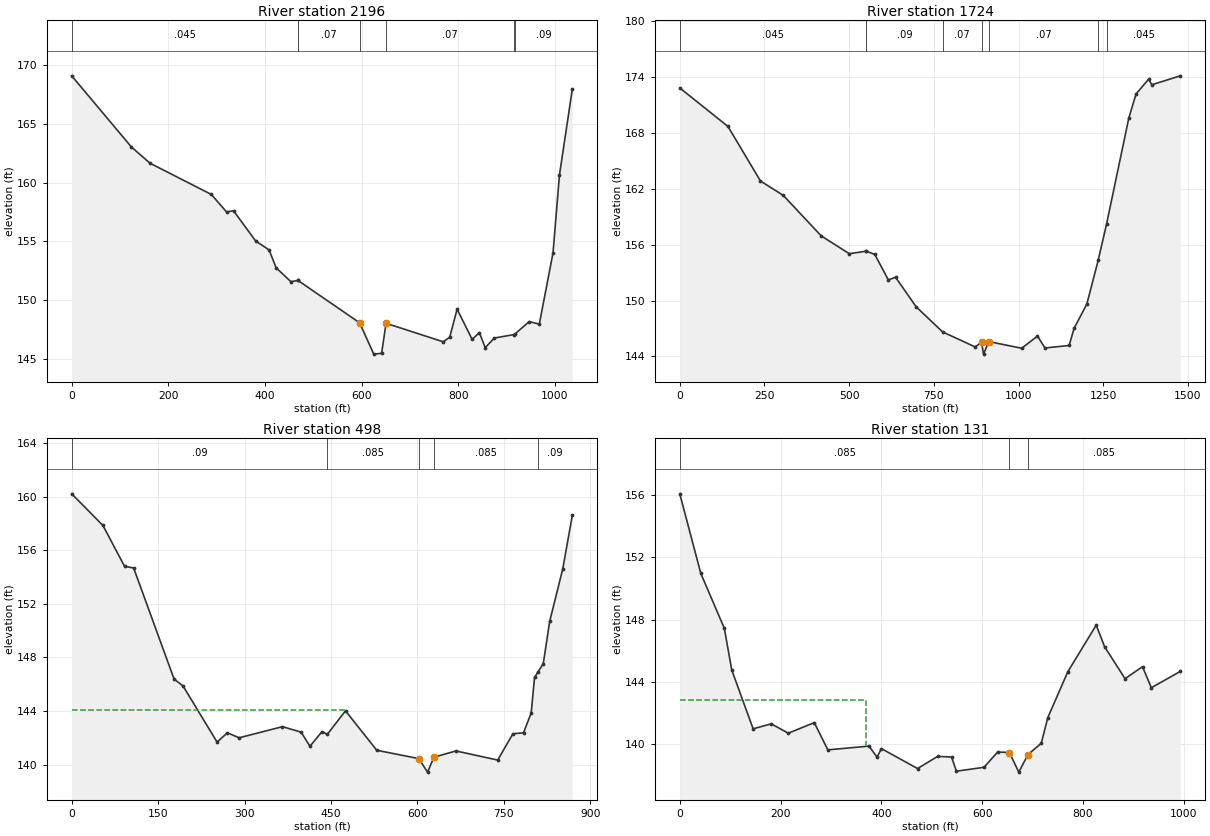
Type RM Length L Ch R = 1 ,2196    ,500.74,471.63,336.42
BEGIN DESCRIPTION:
Surveyed Section
END DESCRIPTION:
XS GIS Cut Line= 6
2273049.82230547  718388.38776212273027.17127101 718073.16086635
2272999.24770002717875.2926000212272940.34230569717603.151902035
2272919.57885751717437.0443162772272889.37747827717369.091212988
#Sta/Elev= 30
       0   169.1  123.77  163.03  162.19  161.65  289.07  158.99   320.6   157.5
     335   157.6  380.78  155.03  408.66  154.26  423.24  152.74  453.88  151.55
  468.03  151.66  468.45  151.66 596.118  148.05 625.349  145.38 641.587  145.45
 650.806  148.01  769.27  146.43  782.66  146.83  797.91  149.21   829.1  146.63
  843.97  147.22  856.15  145.93  874.77  146.75  916.16  147.05  916.89  147.07
  947.11  148.15  968.09  147.94  996.47  154.01 1009.75  160.63 1036.38  167.95
#Mann= 7 ,-1 , 0
       0    .045       0  468.03    .045       0  468.45     .07       0
 596.118    .055       0 650.806     .07       0  916.16     .07       0
  916.89     .09       0
Bank Sta=596.118,650.806
XS Rating Curve= 0 ,0
Exp/Cntr=0.3,0.1

Type RM Length L Ch R = 1 ,1724    ,918.31,1226.16,1113.72
XS GIS Cut Line= 5
2273514.16660836718410.7305415272273543.39374955717990.590386868
2273492.24625246717694.6655822992273273.04269348 717519.30273512
 2273064.7993125717091.855795175
#Sta/Elev= 30
       0  172.85   142.2  168.71  238.17  162.85  305.61   161.3  417.54  156.95
  500.39  155.04  550.58  155.31  550.87  155.31  575.62  154.96   615.7  152.22
   636.9  152.51  697.59  149.34  775.62  146.64  871.55  145.03  890.88   145.5
  896.56  144.25  912.07   145.6 1009.19  144.88 1055.87  146.19 1077.96  144.91
 1149.35  145.18 1163.83  147.02 1201.57  149.63 1235.03  154.33 1259.71  158.22
 1325.52  169.63 1346.77   172.2  1384.1   173.8 1393.12  173.19 1477.66  174.15
#Mann= 8 ,-1 , 0
       0    .045       0  550.58    .045       0  550.87     .09       0
  775.62     .07       0  890.88    .055       0  912.07     .07       0
 1235.03     .09       0 1259.71    .045       0
Bank Sta=890.88,912.07
XS Rating Curve= 0 ,0
Exp/Cntr=0.3,0.1

Type RM Length L Ch R = 1 ,498     ,337.46,367.45,349.62
XS GIS Cut Line= 3
2274102.36282484717870.028429449 2274157.1637146 717464.50184539
2274208.31121169717007.827764258
#Sta/Elev= 30
       0   160.2   54.23  157.84   91.65   154.8  107.52  154.67  177.74  146.38
  192.98  145.89  252.32  141.69  270.12  142.38   290.6  142.01  365.81  142.84
  398.15  142.43  413.46  141.38  434.42  142.47  443.67  142.27  475.16  144.02
   529.4  141.08   602.2  140.46  617.59  139.45   628.5  140.56  666.76  141.03
  739.34  140.35  765.68  142.31  784.06  142.38   797.4  143.86  803.21  146.51
  809.41  146.93  818.33  147.53  829.56   150.7  852.18   154.6  868.74  158.59
#Mann= 5 ,-1 , 0
       0     .09       0  443.67    .085       0   602.2    .055       0
   628.5    .085       0  809.41     .09       0
#XS Ineff= 2 , 0
          475.08  144.08
Permanent Ineff=
       F       F
Bank Sta=602.2,628.5
XS Rating Curve= 0 ,0
Exp/Cntr=0.3,0.1

Type RM Length L Ch R = 1 ,131     ,75.22,130.83,195.07
XS GIS Cut Line= 4
2274218.22785826717899.8070783762274490.43761143717539.529463917
2274514.45611905717203.2703571022274461.08165766717005.784849912
#Sta/Elev= 30
       0  156.08    41.7  150.97   88.42  147.44  103.17  144.76  145.54  140.99
  181.29  141.31  215.45  140.71  266.83  141.39  293.77  139.64  375.38  139.88
  391.45  139.17  400.06  139.72  471.74  138.44  511.58  139.22  539.14  139.18
  548.94  138.27  603.61  138.52  630.63   139.5  653.95  139.47  672.63  138.21
   690.9  139.34  717.15  140.06  730.19  141.71   769.8  144.65  826.24  147.65
  842.76  146.27  883.43  144.21  918.09  144.98  935.59  143.63  993.24  144.68
#Mann= 3 , 0 , 0
       0    .085       0  653.95    .055       0   690.9    .085       0
#XS Ineff= 2 , 0
          370.07  142.87
Permanent Ineff=
       F       F
Bank Sta=653.95,690.9
XS Rating Curve= 0 ,0
Exp/Cntr=0.3,0.1

Chan Stop Cuts=-1
Use User Specified Reach Order=0