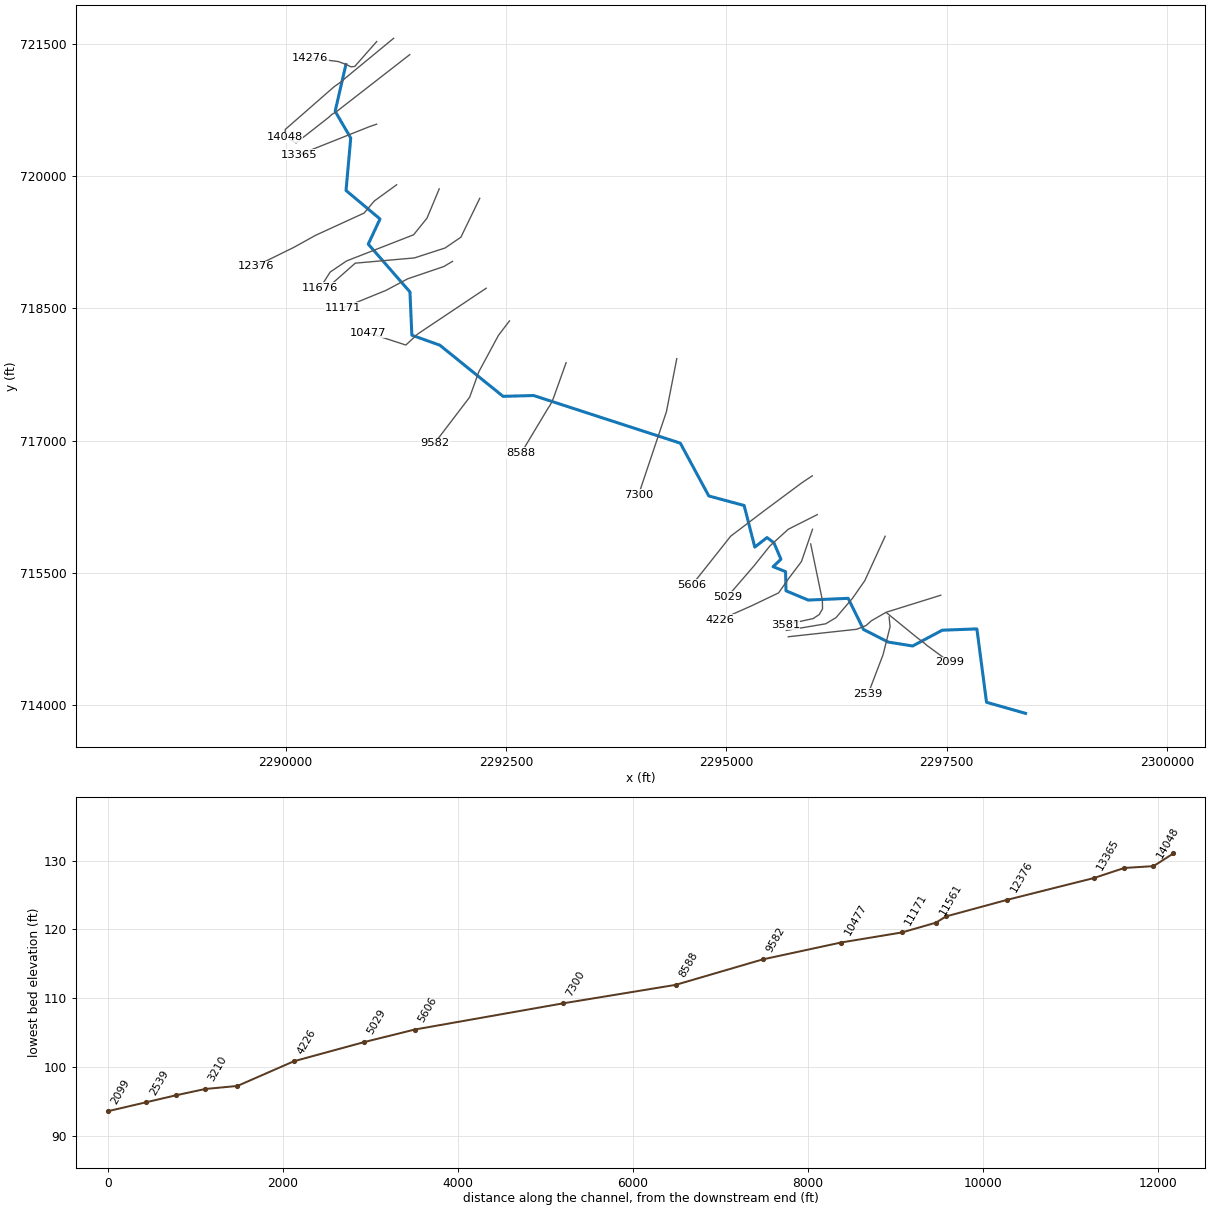
--- DTL_Mill_Branch_into_Contentnea.prj (project) ---

Proj Title=DTL_Mill_Branch_into_Contentnea
Current Plan=p01
Default Exp/Contr=0.3,0.1
English Units
Geom File=g01
Flow File=f01
Flow File=f02
Plan File=p01
Plan File=p02
Y Axis Title=Elevation
X Axis Title(PF)=Main Channel Distance
X Axis Title(XS)=Station
BEGIN DESCRIPTION:
END DESCRIPTION:
DSS Export Rating Curves= 0
DSS Export Rating Curve Sorted= 0
DSS Export Volume Flow Curves= 0
DXF OffsetX= 0
DXF OffsetY= 0
DXF ScaleX= 1
DXF ScaleY= 10

--- DTL_Mill_Branch_into_Contentnea.p01 (plan) ---

Plan Title=DTL_Mill_Branch_into_Contentnea
Program Version=4.00
Short Identifier=Multi
Geom File=g01
Flow File=f01
Subcritical Flow
K Sum by GR= 0
Std Step Tol= 0.01
Critical Tol= 0.01
Num of Std Step Trials= 20
Max Error Tol= 0.3
Flow Tol Ratio= 0.001
Split Flow NTrial= 30
Split Flow Tol= 0.02
Split Flow Ratio= 0.02
Log Output Level= 0
Friction Slope Method= 1
Unsteady Friction Slope Method= 2
Unsteady Bridges Friction Slope Method= 1
Parabolic Critical Depth
Global Vel Dist= 0 , 0 , 0
Global Log Level= 0
CheckData=True
Encroach Param=-1 ,0,0, 2
Encroach River=Mill Branch
Encroach Reach=Trib
Encroach Node=14276
       1     434     595
Encroach Node=14048
       1  552.96     782
Encroach Node=13713
       1     725     850
Encroach Node=13365
       1     330     430
Encroach Node=12376
       1     350     450
Encroach Node=11676
       1    1040    1081
Encroach Node=11561
       1    1490    1534
Encroach Node=11171
       1     575     648
Encroach Node=10477
       1     860     987
Encroach Node=9582
       1     675     790
Encroach Node=8588
       1     430     530
Encroach Node=7300
       1     880     990
Encroach Node=5606
       1     895    1005
Encroach Node=5029
       1     540     650
Encroach Node=4226
       1     680     795
Encroach Node=3581
       1     500   616.5
Encroach Node=3210
       1     815     866
Encroach Node=2875
       1     951    1008
Encroach Node=2539
       1     265     340
Encroach Node=2099
       1     458   546.5
Encroach Node=1871
       1  414.56  482.63
Encroach Node=1728
       1     369     445
Encroach Node=1572
       1     371     460
Encroach Node=1400
       1     785     903
Computation Interval=1HOUR
Output Interval=1HOUR
Run HTab= 0
Run UNet= 0
Run PostProcess= 0
Run WQNet= 0
UNET Theta= 1
UNET Theta Warmup= 1
UNET ZTol= 0.02
UNET ZSATol= 0.05
UNET MxIter= 20
UNET MaxInSteps= 0
UNET DtIC= 0
UNET DtMin= 0
UNET MaxCRTS= 20
UNET WFStab= 2
UNET SFStab= 1
UNET WFX= 1
UNET SFX= 1
UNET DSS MLevel= 4
UNET DZMax Abort= 100
UNET Convert EG Bridges=-1
UNET Use Existing IB Tables=-1
UNET Froude Reduction=False
UNET Froude Limit= 1
UNET Froude Power= 10
UNET Time Slicing=0,0, 5
Instantaneous Interval=1HOUR
Write IC File= 0
Echo Input=False
Echo Output=False
Write Detailed= 0
Detailed Automatic Start=False, 10
WQ ULTIMATE=-1
WQ Max Comp Step=1HOUR
WQ Output Interval=15MIN
WQ Output Selected Increments= 0
WQ Output face flow=0
WQ Output face velocity=0
WQ Output face area=0
WQ Output face dispersion=0
WQ Output cell volume=0
WQ Output cell surface area=0
WQ Output cell continuity=0
WQ Output face conc=0
WQ Output face dconc_dx=0
WQ Output face courant=0
WQ Output face peclet=0
WQ Output face adv mass=0
WQ Output face disp mass=0
WQ Output cell mass=0
WQ Output cell source sink temp=0
WQ Output cell source sink nsm=0
WQ Output MaxMinRange=-1
WQ Daily Max Min Mean=-1
WQ Daily Range=0
WQ Daily Time=0
WQ Create Restart=0
WQ Fixed Restart=0
WQ System Summary=False
Sorting and Armoring Iterations= 10
XS Update Threshold= 0.02
Hydraulics Update Threshold= 0.02
Energy Slope Method= 1
Volume Change Method= 0
XS Weighting Method= 0
Number of US Weighted Cross Sections= 1
Number of DS Weighted Cross Sections= 1
Upstream XS Weight=0.25
Main XS Weight=0.5
Downstream XS Weight=0.25
Number of DS XS's Weighted with US Boundary= 1
Upstream Boundary Weight= 1
Weight of XSs Associated with US Boundary= 0
Number of US XS's Weighted with DS Boundary= 1
Downstream Boundary Weight= 0.5
Weight of XSs Associated with DS Boundary= 0.5
Sediment Output Level= 4
Mass or Volume Output= 0
Output Increment Type= 1
Profile and TS Output Increment= 10
XS Output Flag= 0
XS Output Increment= 10
Disregard all LS=0
Disregard all Conn=0
Disregard all Breaches=0
Disregard all Pumps=0

--- DTL_Mill_Branch_into_Contentnea.p02 (plan) ---

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Plan Title=DTL_Mill_Branch_into_Contentnea_Future
Short Identifier=Future
Geom File=g01
Flow File=f02
Encroach Param=-1 ,0,0, 0

--- DTL_Mill_Branch_into_Contentnea.f01 (steady flow) ---

Flow Title=DTL_Mill_Branch_into_Contentnea
Program Version=4.00
Number of Profiles= 6
Profile Names=100-yr,FW,10-yr,25-yr,50-yr,500-yr
River Rch & RM=Mill Branch,Trib            ,14276
     700     700     290     430     550    1130
River Rch & RM=Mill Branch,Trib            ,11676
     890     890     380     550     710    1420
River Rch & RM=Mill Branch,Trib            ,9582
     990     990     420     620     790    1580
Boundary for River Rch & Prof#=Mill Branch,Trib            , 1
Up Type= 0
Dn Type= 3
Dn Slope=0.00328
Boundary for River Rch & Prof#=Mill Branch,Trib            , 2
Up Type= 0
Dn Type= 3
Dn Slope=0.00328
Boundary for River Rch & Prof#=Mill Branch,Trib            , 3
Up Type= 0
Dn Type= 3
Dn Slope=0.00328
Boundary for River Rch & Prof#=Mill Branch,Trib            , 4
Up Type= 0
Dn Type= 3
Dn Slope=0.00328
Boundary for River Rch & Prof#=Mill Branch,Trib            , 5
Up Type= 0
Dn Type= 3
Dn Slope=0.00328
Boundary for River Rch & Prof#=Mill Branch,Trib            , 6
Up Type= 0
Dn Type= 3
Dn Slope=0.00328
DSS Import GetInterval= 0
DSS Import GetPeak= 0
DSS Import FillOption= 0

--- DTL_Mill_Branch_into_Contentnea.f02 (steady flow) ---

Flow Title=DTL_Mill_Branch_into_Contentnea_Future
Program Version=4.00
Number of Profiles= 3
Profile Names=100-yr-10%,100-yr-20%,100-yr-35%
River Rch & RM=Mill Branch,Trib            ,14276
    1220    1560    1910
River Rch & RM=Mill Branch,Trib            ,11676
    1540    1970    2410
River Rch & RM=Mill Branch,Trib            ,9582
    1700    2190    2670
Boundary for River Rch & Prof#=Mill Branch,Trib            , 1
Up Type= 0
Dn Type= 3
Dn Slope=0.00328
Boundary for River Rch & Prof#=Mill Branch,Trib            , 2
Up Type= 0
Dn Type= 3
Dn Slope=0.00328
Boundary for River Rch & Prof#=Mill Branch,Trib            , 3
Up Type= 0
Dn Type= 3
Dn Slope=0.00328
DSS Import GetInterval= 0
DSS Import GetPeak= 0
DSS Import FillOption= 0

--- DTL_Mill_Branch_into_Contentnea.g01 (geometry) ---

Geom Title=DTL_Mill_Branch_into_Contentnea
Program Version=4.00

River Reach=Mill Branch     ,Trib
Reach XY= 30
 2290683.1534209  721267.1474652     2290561.233     720736.4975
 2290737.9638652  720433.8670189 2290684.8388652  719838.0336856
 2291070.2555319  719515.1170189 2290936.9221986  719229.7003522
 2291409.8388652  718686.9920189 2291431.7138652  718196.3670189
 2291749.4221986  718082.8253522 2292466.0888652  717502.6170189
 2292812.9638652  717511.9920189 2294477.5471986  716971.3670189
 2294800.4638652  716372.4086856 2295201.5055319  716264.0753522
 2295322.3388652  715792.2003522 2295460.8805319  715900.5336856
 2295539.0055319  715841.1586856 2295619.2138652  715654.7003522
 2295529.6305319  715570.3253522 2295671.2971985  715514.0753522
 2295676.5055319  715296.3670189 2295928.5888652  715191.1586856
 2296381.7138652  715210.9503522 2296555.6721985  714857.8253522
 2296834.8388652  714715.1170189 2297112.9638652  714670.3253522
 2297449.4221986  714849.4920189 2297842.1305319  714864.0753522
 2297951.5055319  714031.7836856 2298394.2138652  713905.7420189

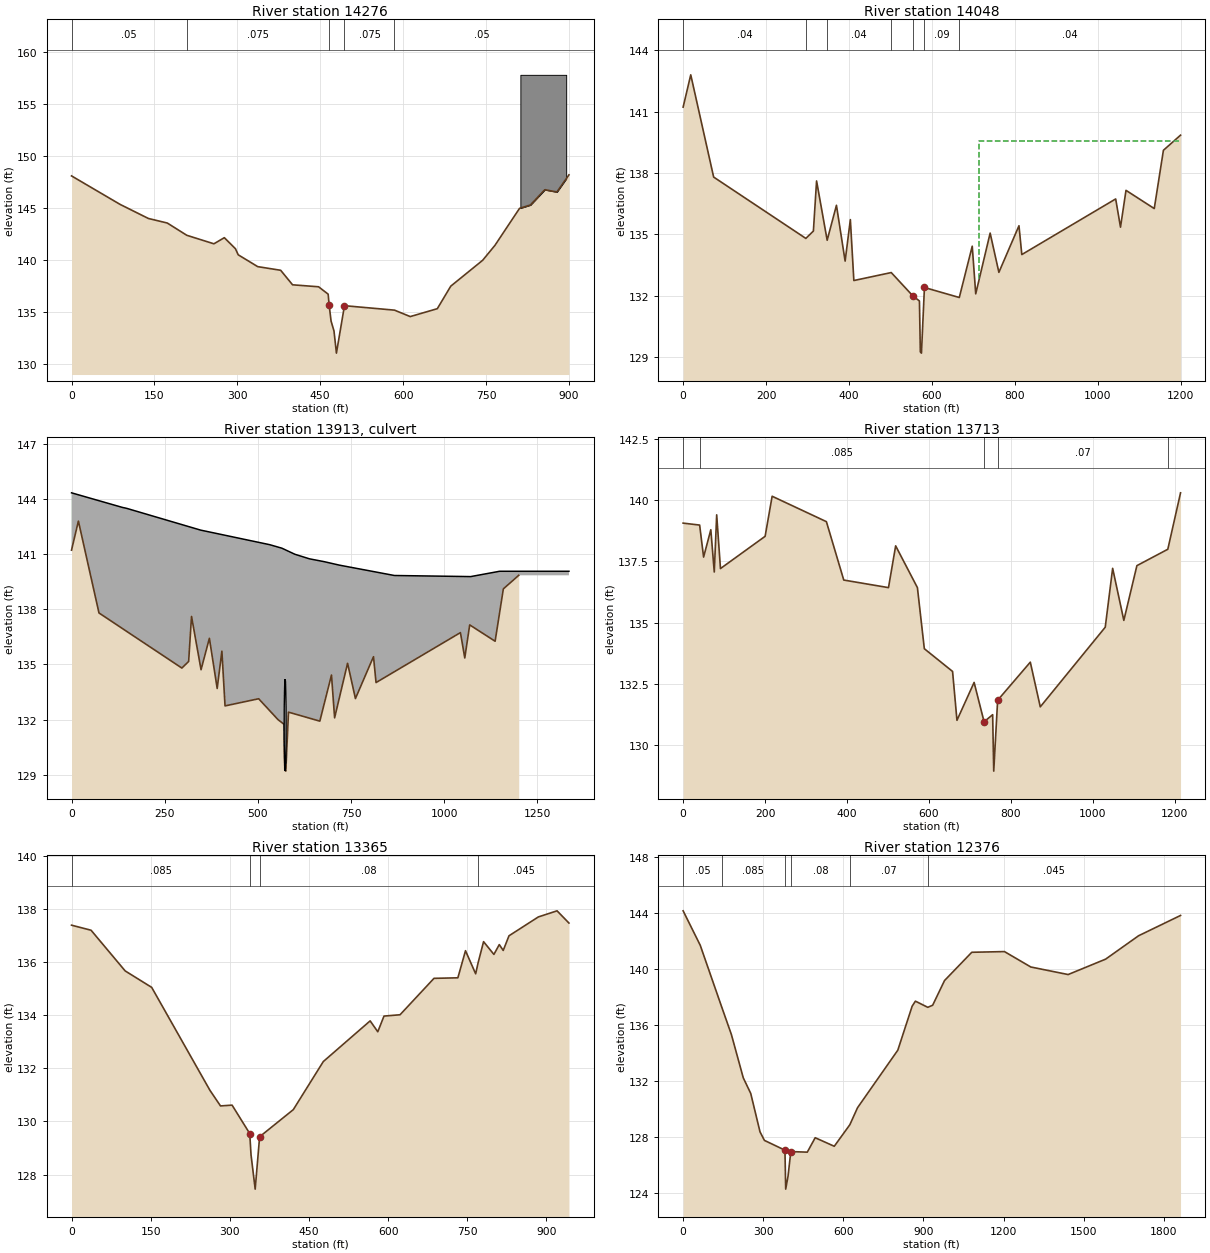
Type RM Length L Ch R = 1 ,14276   ,148.71,228.17,318.33
XS GIS Cut Line= 6
 2291032.8737264  721528.0310353 2290783.2044796  721245.2730932
 2290740.2946761  721241.3955407 2290692.1913022  721264.9572962
 2290598.0383634  721300.8514832 2290275.4350201  721342.3235789
#Sta/Elev= 30
       0  148.11   88.05  145.36  139.06  144.01   173.3  143.57  208.53  142.39
  257.64  141.57  276.46  142.16  296.51   141.1   301.6  140.51   336.9  139.37
   378.4  139.02  399.93  137.62  447.01  137.43  464.32  136.72  466.08  135.68
   469.6  134.13  474.89  133.17   479.3  131.04  493.84  135.61  584.35  135.18
  612.88  134.56  661.84  135.32  686.16  137.49  743.85  139.98   766.1  141.42
  810.56  144.98   830.4  145.31  856.37  146.78  878.26  146.56  900.02  148.21
#Mann= 5 ,-1 , 0
       0     .05       0  208.53    .075       0  466.08     .05       0
  493.84    .075       0  584.35     .05       0
#Block Obstruct= 1 ,-1
  812.14  895.01 157.846
Bank Sta=466.08,493.84
XS Rating Curve= 0 ,0
Exp/Cntr=0.5,0.3

Type RM Length L Ch R = 1 ,14048   ,319.04,334.43,299.81
XS GIS Cut Line= 6
 2291224.3890088  721564.4515144    2290671.9017     721109.2477
    2290642.3351     721081.1036    2290547.8549     721014.0263
 2289995.2551882   720530.736545 2289989.6477185  720441.2640212
#Sta/Elev= 30
       0  141.22  18.392   142.8  73.624   137.8 295.974   134.8 314.196  135.16
 321.882  137.61 347.444  134.71 369.796  136.42 390.733  133.69 403.348  135.72
 411.777  132.74 501.975  133.13 553.559     132 569.969  131.74 572.128  129.25
 574.818  129.19 582.035   132.4 666.095  131.91 697.327  134.42 705.735  132.09
  740.51  135.06 761.596  133.14 810.033  135.42 816.885  134.011043.294  136.73
 1054.94  135.351068.177  137.151136.349  136.261158.425  139.111199.741  139.85
#Mann= 7 ,-1 , 0
       0     .04       0 295.974    .075       0 347.444     .04       0
 501.975    .075       0 553.559     .05       0 582.035     .09       0
 666.095     .04       0
#XS Ineff= 3 ,-1
       0 552.958                                 714.1781202.082  139.58
Permanent Ineff=
       T       F       F
Bank Sta=553.559,582.035
XS Rating Curve= 0 ,0
Skew Angle= 45
Exp/Cntr=0.5,0.3

Type RM Length L Ch R = 2 ,13913   ,,,
BEGIN DESCRIPTION:
Interstate 95
END DESCRIPTION:
Bridge Culvert--1,0,-1,-1, 0
Deck Dist Width WeirC Skew NumUp NumDn MinLoCord MaxHiCord MaxSubmerge Is_Ogee
81,128,2.6,45, 15, 16, , , 0.95, 0, 0,0,,
       0 137.511 142.694 148.782 346.412 531.492 564.222 599.134 638.181 677.917
 718.226 866.1211070.6871148.4261334.395
  144.34  143.54  143.52  143.49  142.31 141.518 141.327 140.996 140.748 140.592
 140.405  139.84  139.78  140.07  140.07
                                                                                
                                        
       0 185.969 287.821 291.208 294.093 532.381 717.461 750.192 785.103  824.15
 863.886 904.1951137.5511156.3741158.7151334.395
 145.024  144.34  143.96  144.01  143.98  142.31 141.518 141.327 140.996 140.748
 140.592 140.405  139.85  139.72  139.72  140.07
                                                                                
                                                
BR Coef=-1 , 0 , 0 ,, 0 ,,,0.8,-1,,0,
WSPro=,,,, 1 ,,,, 0 ,,,, 0 ,,,,-1 ,-1 ,-1 , 0 , 0 , 0 , 0 , 0
Culvert=1,5,,186.22,0.011,0.5,1,1,1,129.2,573,128.92,759,Culvert #1  , 0 ,38.99
Culvert Bottom n=0.011
BC Design=,, 0 ,, 0 ,,,,,,
BC Use User HTab Curves=0
BC User HTab FreeFlow(D)= 0

Type RM Length L Ch R = 1 ,13713   ,329.06,348.32,286.74
XS GIS Cut Line= 6
 2291408.0229727   721379.818785    2290564.7925     720723.8565
    2290526.0652     720703.0466    2290487.2863     720667.2759
 2290117.9822919  720377.8794768  2290045.999025  720418.7234986
#Sta/Elev= 30
       0  139.07  40.319  138.99  49.985  137.68  67.614   138.8  76.028  137.07
  81.932  139.41  91.181  137.21 200.196  138.53 217.336  140.17  349.82  139.13
 392.204  136.74 501.409  136.43 518.882  138.14 572.021  136.43 588.907  133.93
 657.857     133 668.598     131 710.438  132.55 734.787  130.94 755.696  131.23
 758.366  128.92 767.895  131.82 847.658  133.38 871.997  131.551030.622  134.81
1048.703  137.221076.018  135.091107.909  137.331183.371     1381214.463  140.31
#Mann= 5 ,-1 , 0
       0     .04       0  40.319    .085       0 734.787     .05       0
 767.895     .07       01183.371     .04       0
#XS Ineff= 2 , 0
       0     725                       0
Permanent Ineff=
       F       F
Bank Sta=734.787,767.895
XS Rating Curve= 0 ,0
Skew Angle= 45
Exp/Cntr=0.5,0.3

Type RM Length L Ch R = 1 ,13365   ,880.84,988.74,972.23
XS GIS Cut Line= 3
 2291031.6085595  720590.3688542 2290946.0034575  720560.8534636
 2290154.5120707  720245.3264919
#Sta/Elev= 30
       0  137.38   37.02  137.19   101.6  135.66  151.89  135.04  262.21  131.17
   282.3  130.58  304.24  130.61  337.73  129.54  340.09  128.75  348.02  127.45
  356.42  129.42  420.24  130.44  477.14  132.25  565.88  133.78  580.35  133.37
  592.13  133.96  622.53  134.01  686.88  135.38  732.11   135.4  746.58  136.42
  765.84  135.55   770.4  135.96  780.82  136.76  800.41  136.28  810.59  136.65
  818.07  136.43  828.97  136.98   884.6  137.69  920.06  137.92  942.62  137.46
#Mann= 4 ,-1 , 0
       0    .085       0  337.73     .05       0  356.42     .08       0
   770.4    .045       0
Bank Sta=337.73,356.42
XS Rating Curve= 0 ,0
Exp/Cntr=0.3,0.1

Type RM Length L Ch R = 1 ,12376   ,522.58,699.82,453.24
XS GIS Cut Line= 6
 2291258.8564719  719903.0599462 2291004.8305201  719718.5568865
 2290889.8503524  719582.1850597 2290341.6890879  719330.8330652
 2290090.3370934  719191.7872811 2289659.4096834  718979.9120143
#Sta/Elev= 30
       0  144.16    64.1   141.7  144.93  137.27  180.75  135.33  225.18  132.24
  253.22  131.12  287.94  128.38   304.4  127.77  381.32  127.07  384.14  124.29
  392.95  125.22  403.25  126.97     465  126.93  494.56  127.96  566.03  127.35
  624.42  128.89  653.09   130.1  803.96  134.21  857.68  137.35  869.91  137.71
  916.32  137.27  934.55  137.42  978.89  139.18 1081.01   141.2 1203.39  141.25
 1302.07  140.15 1441.81  139.61 1582.24  140.71 1705.65  142.38 1862.82  143.83
#Mann= 6 ,-1 , 0
       0     .05       0  144.93    .085       0  381.32     .05       0
  403.25     .08       0  624.42     .07       0  916.32    .045       0
#XS Ineff= 2 , 0
       0                     500       0
Permanent Ineff=
       F       F
Bank Sta=381.32,403.25
XS Rating Curve= 0 ,0
Exp/Cntr=0.5,0.3

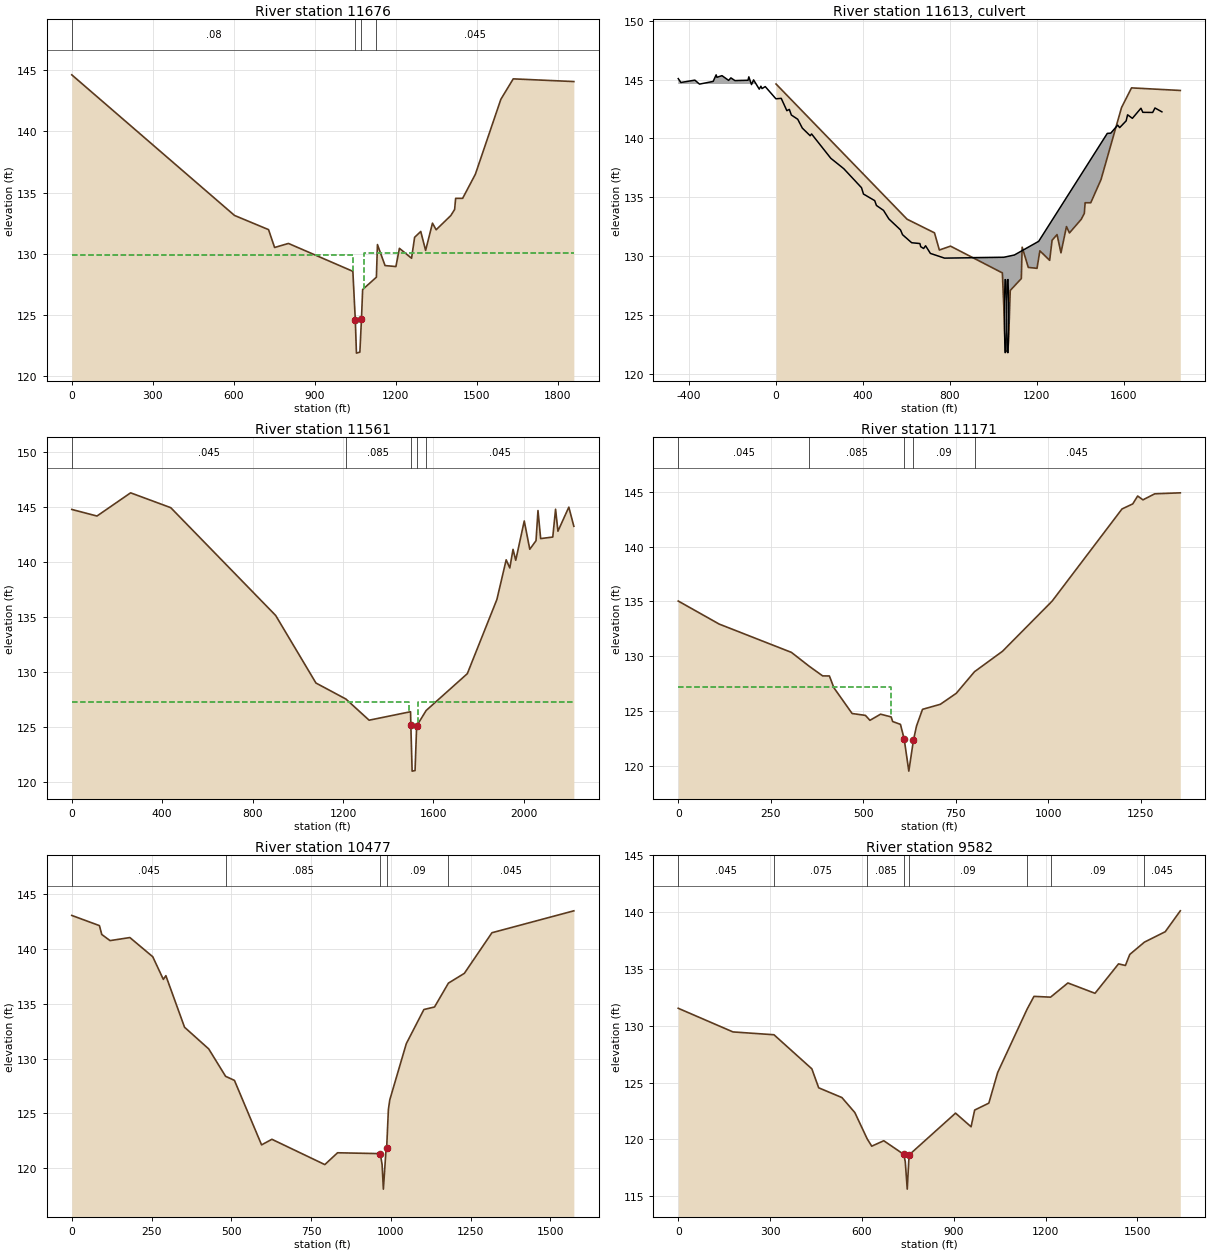
Type RM Length L Ch R = 1 ,11676   ,170.45,115.34,67.1
BEGIN DESCRIPTION:
Surveyed Section
END DESCRIPTION:
XS GIS Cut Line= 6
 2291742.1636033  719856.3841759 2291603.4247618  719524.4086742
 2291451.1726764  719335.6160883 2290691.9422774  719039.2320287
 2290505.1797193  718913.3703048 2290391.4981622   718734.727858
#Sta/Elev= 30
       0  144.63  602.84  133.13  728.98  131.97  751.37  130.51 802.679  130.84
 1041.29  128.56 1050.27  124.621054.576  121.87 1067.26  121.95 1073.22  124.68
1077.509  127.071128.458  128.081132.349  130.751160.509  129.031200.749  128.95
 1213.76  130.44 1258.78  129.63 1270.04  131.341292.769  131.82 1310.83  130.27
 1336.21   132.5 1349.86  131.96  1404.1  133.121418.291  133.62 1422.04  134.53
 1448.01  134.531495.109   136.51589.551  142.63 1635.44   144.3 1859.91  144.08
#Mann= 4 ,-1 , 0
       0     .08       0 1050.27     .05       0 1073.22     .08       0
1128.458    .045       0
#XS Ineff= 2 ,-1
       0    1040  129.891080.999    1860  130.09
Permanent Ineff=
       T       T
Bank Sta=1050.27,1073.22
XS Rating Curve= 0 ,0
Exp/Cntr=0.5,0.3

Type RM Length L Ch R = 2 ,11613   ,,,
BEGIN DESCRIPTION:
Ernest Rd
END DESCRIPTION:
Bridge Culvert--1,0,-1,-1, 0
Deck Dist Width WeirC Skew NumUp NumDn MinLoCord MaxHiCord MaxSubmerge Is_Ogee
48.6,22,2.6,0, 60, 60, , , 0.95, 0, 0,0,,
    -450 -437.74 -373.42-352.259 -289.34 -275.62 -272.03 -248.73 -218.34 -207.68
 -189.23 -129.14 -125.21 -112.99 -103.33  -77.25  -69.66 -64.521  -49.71   -.629
   23.82  49.761   61.04   70.47   99.77  120.87  156.92 163.451  252.02   311.4
  393.16  402.27   453.9  461.82  494.48   519.2  572.55  582.08  623.92  661.81
 665.629  678.93 687.999 710.241 775.2291047.5591096.291 1208.33 1523.89 1539.97
 1571.72 1580.88 1610.96 1617.22 1639.39 1678.85 1687.43 1732.84 1743.38  1775.2
  145.09  144.76  144.96  144.62  144.85  145.41   145.2  145.34  144.94  145.15
  144.92  144.95  145.24  144.58  144.98  144.19  144.44  144.24  144.41  143.37
  143.41  142.36  142.47  141.99  141.63  140.88  140.23  140.38  138.31  137.43
  135.81  135.27  134.71   134.3  133.88  133.15  132.22  131.81  131.13  131.06
  130.79  130.64  130.87  130.22  129.82 129.892 130.085  131.25  140.43  140.45
  141.13  140.92   141.5  142.01  141.71  142.57  142.22  142.21  142.59  142.26
                                                                                
                                                                                
                                                                                
                                                                                
                                                                                
                                                                                
       0   12.26   76.58  97.741  160.66  174.38  177.97  199.25 201.269 231.659
  242.32  260.77  320.86  324.79  337.01  346.67  372.75  380.34 385.481  400.29
 449.371 473.819  499.76  511.04  520.47  549.77  570.87  606.92  613.45  702.02
  751.97   761.4  775.48  792.36  813.61  843.16  852.27   903.9  911.82  944.48
   969.2 1022.55 1032.08 1073.921225.2291497.5591546.2911658.329 1973.891989.969
 2021.72 2030.88 2060.962067.219 2089.39 2128.85 2137.43 2182.84 2193.38  2225.2
  145.09  144.76  144.96  144.62  144.85  145.41   145.2  145.16  145.34  144.94
  145.15  144.92  144.95  145.24  144.58  144.98  144.19  144.44  144.24  144.41
  143.37  143.41  142.36  142.47  141.99  141.63  140.88  140.23  140.38  138.31
  137.37  137.43  136.88  136.81  136.18  135.81  135.27  134.71   134.3  133.88
  133.15  132.22  131.81  131.13  129.82 129.892 130.085  131.25  140.43  140.45
  141.13  140.92   141.5  142.01  141.71  142.57  142.22  142.21  142.59  142.26
                                                                                
                                                                                
                                                                                
                                                                                
                                                                                
                                                                                
BR Coef=-1 , 0 , 0 ,, 0 ,,,0.8,-1,,0,
WSPro=,,,, 1 ,,,, 0 ,,,, 0 ,,,,-1 ,-1 ,-1 , 0 , 0 , 0 , 0 , 0
Multiple Barrel Culv=4,6.3,8.3,60.2,0.024,0.5,1,29,1,121.74,120.92, 2,Culvert #1  , 0 ,31.9
    1055    1507    1066  1518.4
Culvert Bottom n=0.024
BC Design=,, 0 ,, 0 ,,,,,,
BC Use User HTab Curves=0
BC User HTab FreeFlow(D)= 0

Type RM Length L Ch R = 1 ,11561   ,324.83,389.87,423.52
BEGIN DESCRIPTION:
Surveyed Section
END DESCRIPTION:
XS GIS Cut Line= 6
 2292201.8286498  719749.2754539 2291987.7572753  719308.0795723
 2291807.6240455  719185.3801259 2291460.4107186  719073.1231856
 2290789.4431075    719013.63272 2290447.2457121  718711.8678698
#Sta/Elev= 30
       0  144.75  111.54  144.15  260.33  146.26 437.949  144.91   902.2  135.11
 1080.34  128.97 1213.08  127.51 1315.54  125.591498.894  126.36 1500.22  125.12
 1505.83  120.961518.771  121.01  1525.9  125.06 1567.82  126.47 1750.04  129.82
1880.822  136.561922.041  140.17 1937.96  139.431952.301  141.12 1964.32  140.13
2001.949   143.7  2026.4  141.13 2054.06  141.91 2062.66  144.652074.549   142.1
 2128.11  142.24  2140.5  144.772150.981  142.77 2199.12  144.962221.341  143.22
#Mann= 5 ,-1 , 0
       0    .045       0 1213.08    .085       01498.894     .05       0
  1525.9     .09       0 1567.82    .045       0
#XS Ineff= 2 ,-1
       0    1490  127.22    1534    2300  127.22
Permanent Ineff=
       F       F
Bank Sta=1500.22,1525.9
XS Rating Curve= 0 ,0
Exp/Cntr=0.5,0.3

Type RM Length L Ch R = 1 ,11171   ,613.22,694.01,654.79
XS GIS Cut Line= 5
 2291892.5843728  719034.0237952 2291793.6479495  718975.1967327
 2291384.5324691  718836.1509485 2291138.5283894  718705.1270365
 2290646.5202301  718504.5802324
#Sta/Elev= 30
       0  135.04  110.72  132.94  305.99  130.36  353.97   129.1  390.29  128.22
  408.69  128.21  420.74  127.14  470.07  124.79  505.97  124.62  518.24  124.17
  546.99  124.73  575.56  124.48   579.7  124.06   600.7   123.8  610.73  122.48
  623.34  119.54  635.76  122.35  644.13  123.65  660.31  125.17   708.5  125.63
  751.53  126.63   800.9   128.6  876.51  130.46 1010.67  135.03 1199.61  143.43
  1228.6  143.89 1241.96  144.61 1256.23  144.26  1288.1  144.81 1357.23   144.9
#Mann= 5 ,-1 , 0
       0    .045       0  353.97    .085       0  610.73     .05       0
  635.76     .09       0   800.9    .045       0
#XS Ineff= 2 , 0
       0     575  127.22               0
Permanent Ineff=
       F       F
Bank Sta=610.73,635.76
XS Rating Curve= 0 ,0
Exp/Cntr=0.3,0.1

Type RM Length L Ch R = 1 ,10477   ,774.25,895.46,889.86
XS GIS Cut Line= 4
 2292274.9602792   718729.192653 2291502.1865942  718213.1188771
   2291363.14081  718084.7689225 2290930.3354114   718225.640845
#Sta/Elev= 30
       0  143.07   86.72  142.14   94.01  141.33  120.01  140.77  182.11  141.05
  253.78   139.3  287.02  137.23  294.94  137.57  353.47  132.86  429.27  130.88
  482.16  128.38  509.84  128.01  594.91  122.12   627.3  122.63  793.15  120.32
  833.13   121.4  967.05  121.32  972.69  120.32  976.66  118.08  985.37  121.84
  986.99  121.85  992.42  125.36  996.74  126.23 1048.48  131.36 1103.67  134.48
 1136.97  134.71 1180.54  136.89 1230.42  137.78 1316.96  141.49 1573.64  143.49
#Mann= 5 ,-1 , 0
       0    .045       0  482.16    .085       0  967.05     .05       0
  986.99     .09       0 1180.54    .045       0
#XS Ineff= 2 , 0
       0     750                       0
Permanent Ineff=
       F       F
Bank Sta=967.05,986.99
XS Rating Curve= 0 ,0
Exp/Cntr=0.3,0.1

Type RM Length L Ch R = 1 ,9582    ,890.64,993.91,896.71
XS GIS Cut Line= 5
 2292539.1317077  718358.7426968 2292414.0060634  718194.4011754
 2292192.0676002  717782.6117377 2292087.7832621  717493.8243398
 2291688.4372633  716969.8538079
#Sta/Elev= 30
       0  131.54  178.82  129.46  312.78  129.21  436.49  126.21  458.83  124.54
  534.78  123.68  576.95  122.36   617.2  120.05  632.12   119.4  671.45  119.88
  736.77  118.68  741.65  118.04  748.11  115.62  754.16  118.63  905.94  122.31
  956.64  121.11  968.37  122.58 1014.69  123.19 1043.59  125.89  1139.6  131.46
 1162.18  132.59 1216.36  132.52    1273  133.77 1361.53  132.86 1438.33  135.45
 1460.84  135.31 1475.09  136.28 1522.75  137.36 1590.95  138.28 1640.19  140.12
#Mann= 8 ,-1 , 0
       0    .045       0  312.78    .075       0   617.2    .085       0
  736.77     .05       0  754.16     .09       0  1139.6    .045       0
 1216.36     .09       0 1522.75    .045       0
Bank Sta=736.77,754.16
XS Rating Curve= 0 ,0
Exp/Cntr=0.3,0.1

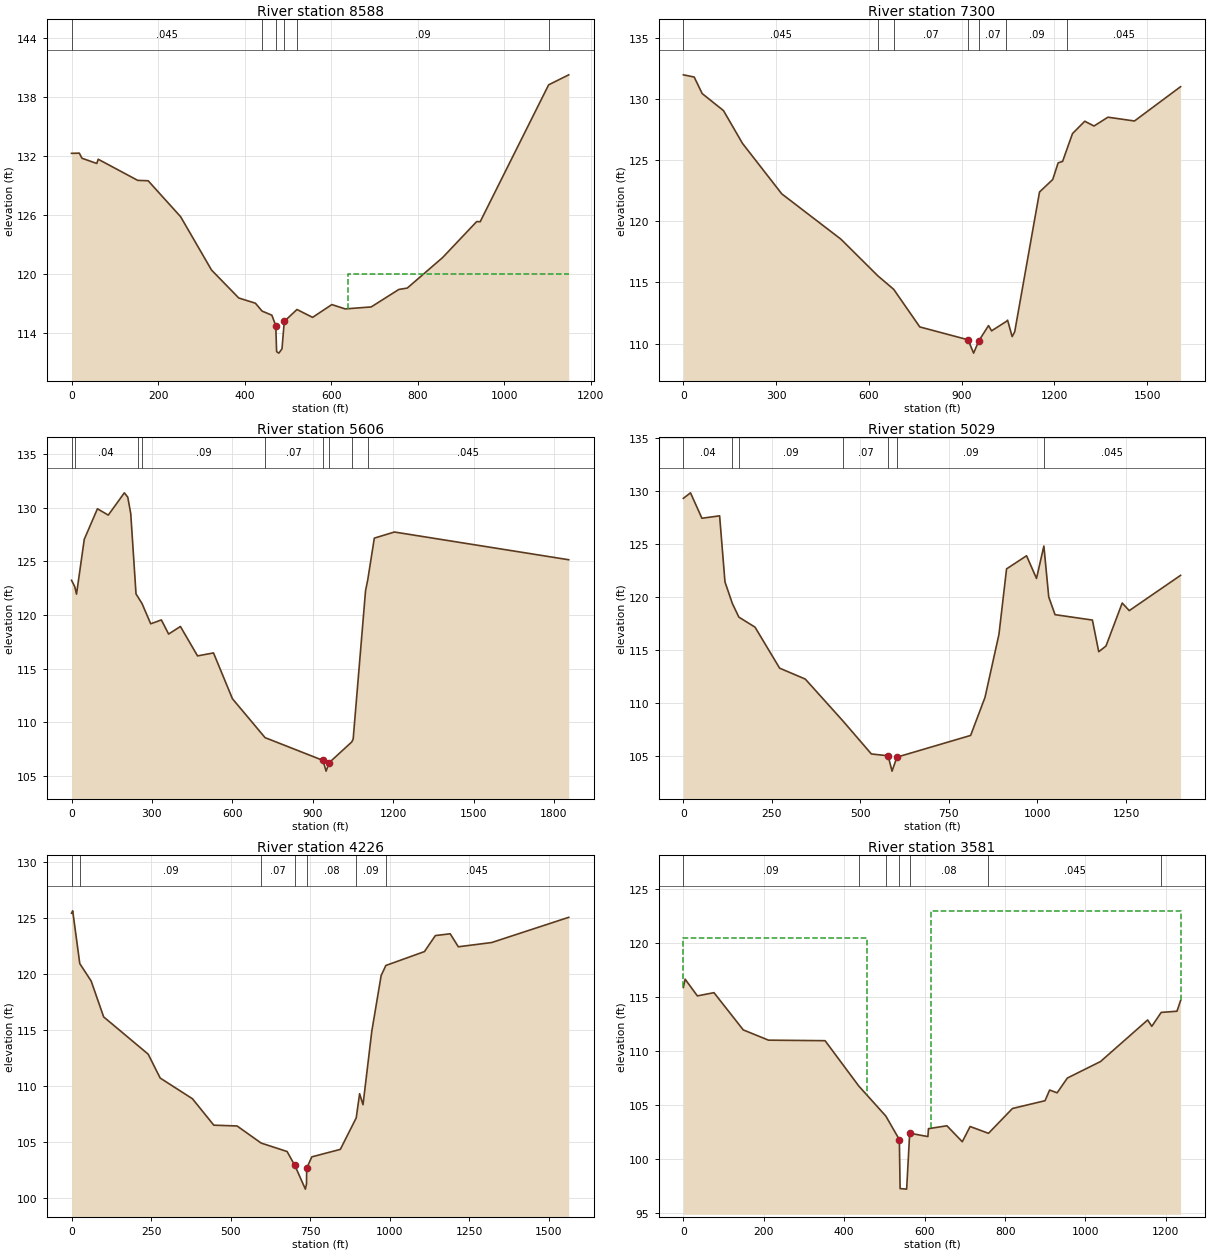
Type RM Length L Ch R = 1 ,8588    ,1275.57,1287.48,1338.33
BEGIN DESCRIPTION:
Surveyed Section
END DESCRIPTION:
XS GIS Cut Line= 6
 2293181.4928188  717884.2056598    2293038.3659       717483.81
    2293019.9686     717440.4589    2292996.9867     717397.3817
    2292976.5226     717367.6208 2292672.2335596  716859.9001042
#Sta/Elev= 30
       0  132.25   18.06  132.27   24.16  131.75   58.35  131.22   61.71  131.65
  153.01   129.5  177.17  129.46  252.24   125.8  323.74  120.37  386.62  117.53
 425.078     117  440.43   116.2 463.133  115.78 472.162  114.72 474.107  112.07
 479.271  111.92 486.516  112.36 491.824  115.15 521.153  116.36 557.259  115.56
  601.77  116.86  632.62  116.42  692.74  116.62  756.66   118.4  776.14  118.54
  857.97  121.65  936.66  125.31  944.66  125.29 1102.92  139.22 1149.35  140.24
#Mann= 6 ,-1 , 0
       0    .045       0  440.43    .085       0 472.162     .05       0
 491.824     .07       0 521.153     .09       0 1102.92    .045       0
#XS Ineff= 2 , 0
       0                     640       0     120
Permanent Ineff=
       F       F
Bank Sta=472.162,491.824
XS Rating Curve= 0 ,0
Exp/Cntr=0.3,0.1

Type RM Length L Ch R = 1 ,7300    ,1541.9,1694.18,1455.6
XS GIS Cut Line= 3
 2294437.2798559  717930.5019561 2294320.2405745  717329.7721023
 2294003.3271064  716385.3699671
#Sta/Elev= 30
       0  131.96   35.05  131.78   60.87  130.43  129.74  129.04  191.32  126.36
  318.25  122.24  509.52  118.54   629.6  115.53  680.42  114.44  764.75  111.37
  920.85  110.32  938.85  109.23   955.6  110.23  987.05  111.48  996.88  111.05
 1044.68  111.82 1048.75  111.92 1063.49  110.58 1071.74  110.97    1152  122.39
 1194.75  123.41 1212.22  124.77 1226.67  124.89 1239.43   125.8 1258.68  127.16
 1298.38  128.17  1328.3  127.78 1373.31   128.5 1459.11  128.19 1608.18  130.99
#Mann= 7 ,-1 , 0
       0    .045       0   629.6     .09       0  680.42     .07       0
  920.85     .05       0   955.6     .07       0 1044.68     .09       0
 1239.43    .045       0
Bank Sta=920.85,955.6
XS Rating Curve= 0 ,0
Exp/Cntr=0.3,0.1

Type RM Length L Ch R = 1 ,5606    ,363.12,576.92,418.07
XS GIS Cut Line= 5
 2295974.5288785  716600.8711255 2295860.4400299  716524.8118931
 2295442.1142519  716214.2366943 2295049.1415514  715916.3380342
 2294611.8009653  715364.9085996
#Sta/Elev= 30
       0  123.24   11.87  122.66   18.66  121.95   47.58  127.07   96.66  129.92
  137.12  129.33  197.11  131.41   209.9     131  220.95  129.48  240.63  121.97
  247.46   121.7  263.23  121.06  295.47  119.18  335.26  119.54  362.32  118.22
  406.24  118.93  470.24  116.18  529.75  116.46  600.39  112.18  721.99  108.55
  938.29  106.42  949.73  105.42  961.73  106.22 1045.33  108.14 1050.78   108.4
 1097.06  122.28 1105.43  123.31 1129.78  127.18  1204.8  127.75 1855.06  125.16
#Mann= 9 ,-1 , 0
       0     .08       0   11.87     .04       0  247.46    .045       0
  263.23     .09       0  721.99     .07       0  938.29     .05       0
  961.73     .07       0 1045.33     .09       0 1105.43    .045       0
Bank Sta=938.29,961.73
XS Rating Curve= 0 ,0
Exp/Cntr=0.3,0.1

Type RM Length L Ch R = 1 ,5029    ,457.12,803.79,476.41
XS GIS Cut Line= 5
 2296030.8800545  716160.4109224 2295701.9832958  715994.6255644
 2295493.4146196  715804.7745899 2295311.5855172  715577.4882119
 2295009.4283324  715227.1997941
#Sta/Elev= 30
       0  129.35   20.16  129.87   52.44  127.47   102.4   127.7  117.53  121.46
   138.3  119.43  156.69  118.14  202.41  117.19  271.86  113.32  344.31  112.29
  450.55  108.34  530.92  105.22  578.13  105.05  589.28   103.6  603.03  104.92
  811.22  106.97  851.88  110.57   891.2  116.51  912.68  122.69  969.18  123.93
  997.22  121.79 1018.06  124.85 1031.79  120.05 1049.56  118.37 1155.13  117.86
 1172.97  114.87 1193.43  115.41 1239.27  119.47 1259.16  118.75 1404.03  122.08
#Mann= 7 ,-1 , 0
       0     .04       0   138.3    .045       0  156.69     .09       0
  450.55     .07       0  578.13     .05       0  603.03     .09       0
 1018.06    .045       0
Bank Sta=578.13,603.03
XS Rating Curve= 0 ,0
Exp/Cntr=0.3,0.1

Type RM Length L Ch R = 1 ,4226    ,384.77,644.81,561.23
XS GIS Cut Line= 6
 2295977.4009068  715994.6255644 2295851.7249095  715628.2934023
 2295712.6791254  715443.7903425 2295592.3510429  715272.6570697
 2295290.1938581  715128.2633708  2294923.861696  714965.1519701
#Sta/Elev= 30
       0  125.45    3.71  125.66   25.95  120.95   61.78  119.39  101.03  116.19
   241.1  112.86  278.73  110.73  380.26  108.88   447.4  106.52  520.54  106.45
  596.44  104.92  677.78  104.17  701.97  102.94  735.37  100.81  738.87  101.28
  739.42  102.67  755.52  103.69  845.24  104.36  895.21  107.17  905.89  109.33
  916.61  108.35  944.14   114.9   973.6  119.88  988.39  120.78 1109.71  122.02
 1144.05  123.45 1190.75  123.61 1216.31  122.45 1321.29  122.83 1563.41  125.08
#Mann= 7 ,-1 , 0
       0     .04       0   25.95     .09       0  596.44     .07       0
  701.97     .05       0  739.42     .08       0  895.21     .09       0
  988.39    .045       0
Bank Sta=701.97,739.42
XS Rating Curve= 0 ,0
Exp/Cntr=0.5,0.3

Type RM Length L Ch R = 1 ,3581    ,405.86,370.45,301.6
BEGIN DESCRIPTION:
Surveyed Section
END DESCRIPTION:
XS GIS Cut Line= 6
 2295956.4127053  715828.0586352 2296088.9819442  715190.9348301
 2296090.9605896  715092.0025623 2296053.3663278  715026.7072655
 2295984.1137403  714981.1984223 2295667.5304831  714911.9458348
#Sta/Elev= 30
       0   115.9     4.4  116.67   34.83  115.12   76.15  115.42  148.96  111.97
   211.7  111.02  352.42  110.97  436.07  106.78  503.45  103.99  537.14  101.81
  538.97   97.27  555.24   97.22   562.8   102.4  608.08  102.09  609.46  102.82
  655.41  103.09  693.61  101.61  713.08  103.02  758.77  102.39  818.36  104.69
  899.34  105.41  910.83   106.4   929.4  106.14  954.92  107.51 1037.37  109.04
 1154.61  112.89 1164.83   112.3 1188.28  113.59 1227.44   113.7 1236.38  114.68
#Mann= 7 ,-1 , 0
       0     .09       0  436.07     .07       0  503.45     .07       0
  537.14     .05       0   562.8     .08       0  758.77    .045       0
 1188.28     .04       0
#XS Ineff= 2 , 0
       0  456.38   120.5   616.5       0     123
Permanent Ineff=
       F       F
Bank Sta=537.14,562.8
XS Rating Curve= 0 ,0
Exp/Cntr=0.5,0.3

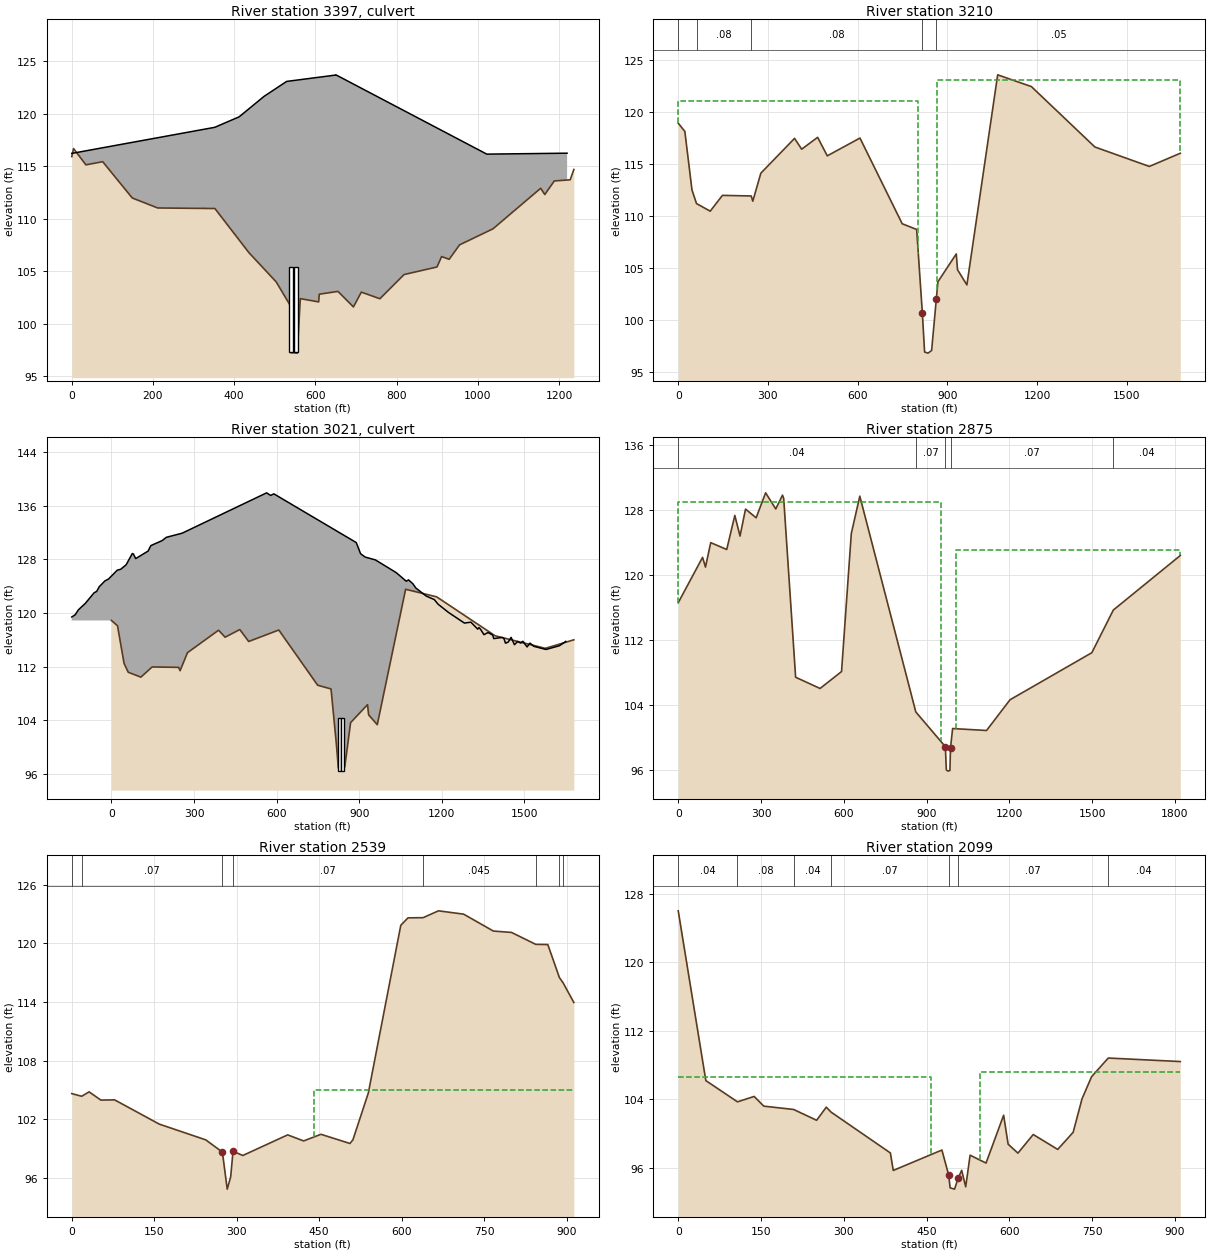
Type RM Length L Ch R = 2 ,3397    ,,,
BEGIN DESCRIPTION:
Ramps at HWY 264 to and from HWY 42
END DESCRIPTION:
Bridge Culvert--1,0,-1,-1, 0
Deck Dist Width WeirC Skew NumUp NumDn MinLoCord MaxHiCord MaxSubmerge Is_Ogee
72,115,2.6,0, 10, 106, , , 0.95, 0, 0,0,,
       0 352.187 412.096 473.616 529.131  650.26   650.3  650.39    1022 1219.77
  116.21  118.69 119.685 121.636 123.053  123.66  123.67  123.68  116.14  116.23
                                                                                
       0    3.44  179.03  278.45 597.187 657.096 718.616 774.131  895.26   895.3
  895.39  916.12  916.84     917  917.36  927.14  936.04  960.15  969.02   970.2
  981.63  982.77  991.28  995.61 1004.65 1008.93 1015.46  1025.6 1027.71 1037.03
 1042.41 1048.73 1054.87 1061.23  1062.8 1073.44 1082.76 1087.48 1095.87 1104.61
  1107.6  1119.7 1121.28 1129.77 1130.32 1130.42 1130.73  1143.6 1144.02 1152.28
 1162.94 1166.36 1167.93 1174.91 1177.63 1185.83 1190.77 1194.52 1203.31 1210.22
 1212.38 1214.45  1219.9 1222.55 1229.29 1234.08 1239.66 1252.97 1255.04 1256.82
 1258.44    1267 1271.92 1279.15 1281.71 1285.78 1293.88 1301.91 1303.19 1305.61
 1311.29 1314.54 1324.23 1325.01 1325.56 1341.34 1348.38 1354.89 1359.01 1361.84
 1373.36 1374.21 1385.43 1388.16 1395.33 1407.23 1410.24 1420.01 1424.47 1431.72
 1447.72 1448.62  1449.5 1450.25  1460.7 1464.77
  122.26   122.3  119.65  117.95  118.69 119.685 121.636 123.053  123.66  123.67
  123.68  122.72  122.65  122.63  122.68  122.58  122.22  121.77  121.68  121.66
   121.3  121.27  121.04  120.89  120.61  120.47  120.29  120.03  119.98  119.82
  119.61  119.49  119.36  119.25  119.22  118.76  118.54  118.44  118.22  117.96
  117.86  117.36  117.36  117.27  117.27  117.26  117.25  116.87  116.87  116.89
  116.47  116.37  116.35  116.36  116.43  116.28  116.16  116.25   116.1  116.07
  116.03  116.05  116.09  116.08  115.84  115.69  115.67  115.51   115.5   115.5
  115.68  116.14  116.21  115.46  115.43  115.33  115.46  115.23  115.26  115.32
  115.52  115.45  114.97  114.93  114.94  114.97  114.75  114.93  114.97  114.88
  114.81  114.83  115.11  115.09  115.64  116.23  116.16  115.12  115.27  115.72
  116.02  116.02  116.05  116.07  116.19  116.23
                                                                                
                                                                                
                                                                                
                                                                                
                                                                                
                                                                                
                                                                                
                                                                                
                                                                                
                                                                                
                                                
BR Coef=-1 , 0 , 0 ,, 0 ,,,0.8,-1,,0,
WSPro=,,,, 1 ,,,, 0 ,,,, 0 ,,,,-1 ,-1 ,-1 , 0 , 0 , 0 , 0 , 0
Multiple Barrel Culv=2,8,11,199.3,0.011,0.4,1,8,1,97.37,97.08, 2,Culvert #1  , 0 ,63
  540.28   831.5  552.28   843.5
Culvert Bottom n=0.011
BC Design=,, 0 ,, 0 ,,,,,,
BC Use User HTab Curves=0
BC User HTab FreeFlow(D)= 0

Type RM Length L Ch R = 1 ,3210    ,366.73,335.21,305.3
BEGIN DESCRIPTION:
Surveyed Section
END DESCRIPTION:
XS GIS Cut Line= 6
 2296801.2942729   715915.119031 2296569.7927661  715410.5644648
    2296431.1007     715211.5634 2296243.6946685  714991.8641879
 2296125.8588485  714921.7996463 2295679.9935839  714846.9579769
#Sta/Elev= 30
       0  118.88   22.09  118.09   45.98  112.46   61.13  111.15  107.02  110.42
  147.83  111.94  244.18  111.88   249.4  111.38  276.26  114.07  389.07  117.42
  412.86  116.38  466.31  117.52  498.53  115.74  607.88  117.45  749.14  109.21
 797.523  108.66  816.47  100.65  824.06   96.88  835.37   96.77  847.49   97.02
  863.44  102.02 868.548  103.63 930.033  106.31  934.15  104.79  965.53  103.33
 1068.48  123.53 1181.19   122.4 1393.63  116.59 1575.78  114.72 1679.36  115.99
#Mann= 5 ,-1 , 0
       0     .08       0   61.13     .08       0  244.18     .08       0
  816.47    .045       0  863.44     .05       0
#XS Ineff= 2 , 0
       0     803     121     866       0     123
Permanent Ineff=
       F       F
Bank Sta=816.47,863.44
XS Rating Curve= 0 ,0
Exp/Cntr=0.5,0.3

Type RM Length L Ch R = 2 ,3021    ,,,
BEGIN DESCRIPTION:
HWY 42
END DESCRIPTION:
Bridge Culvert--1,0,-1,-1, 0
Deck Dist Width WeirC Skew NumUp NumDn MinLoCord MaxHiCord MaxSubmerge Is_Ogee
145,110,2.6,0, 60, 60, , , 0.95, 0, 0,0,,
    -144 -131.77 -120.05  -94.82   -62.9  -53.73  -43.86  -23.33  -10.62   21.39
    33.5   53.34    75.8   79.79   88.15  133.18  143.33  183.98  199.24  256.89
  563.72   578.2  589.86 889.185  904.81  921.33  958.87 1034.14 1070.69 1078.95
 1094.52 1105.62 1143.12 1172.61 1186.15    1224 1281.79 1305.55 1330.02 1334.48
 1339.83 1352.99 1367.81 1384.88 1388.49 1418.83 1425.27 1431.16    1441 1451.55
 1463.66 1474.91 1486.41 1494.22 1509.41 1520.01    1534  1578.4 1627.06 1650.03
   119.4  119.72  120.46  121.43  123.01  123.21  123.93  124.79  125.06  126.39
  126.51  127.18  128.86   128.8  128.11  129.23  130.05  130.79  131.28   131.9
  137.92  137.53  137.77   130.5  128.84  128.34  127.91  126.02  124.73  124.93
  124.37  123.72  122.52  121.99  121.31  120.08  118.49  118.62  117.59   117.8
   117.6  116.76  117.08  116.68  116.17  116.35   116.2  115.49  115.66  116.35
  115.26  115.73  115.51  115.77  114.93   115.5  115.02  114.55  115.11  115.75
                                                                                
                                                                                
                                                                                
                                                                                
                                                                                
                                                                                
       0   12.23   23.95   49.18    81.1   90.27  100.14  120.67  133.38  165.39
   177.5  197.34   219.8  223.79  232.15  277.18  287.33  343.24  400.89  707.72
   722.2  733.86  767.29  772.751033.185 1048.81 1065.33 1102.87 1178.14 1214.69
 1222.95 1249.62 1287.12 1316.61 1330.15    1368 1425.79 1449.55 1474.02 1478.48
 1483.83 1496.99 1511.81 1528.88 1532.49 1562.83 1569.27 1575.16    1585 1595.55
 1607.66 1618.91 1630.41 1638.22 1653.41 1664.01    1678  1722.4 1771.06 1794.03
   119.4  119.72  120.46  121.43  123.01  123.21  123.93  124.79  125.06  126.39
  126.51  127.18  128.86   128.8  128.11  129.23  130.05  131.28   131.9  137.92
  137.53  137.77  136.71  136.88   130.5  128.84  128.34  127.91  126.02  124.73
  124.93  123.72  122.52  121.99  121.31  120.08  118.49  118.62  117.59   117.8
   117.6  116.76  117.08  116.68  116.17  116.35   116.2  115.49  115.66  116.35
  115.26  115.73  115.51  115.77  114.93   115.5  115.02  114.55  115.11  115.75
                                                                                
                                                                                
                                                                                
                                                                                
                                                                                
                                                                                
BR Coef=-1 , 0 , 0 ,, 0 ,,,0.8,-1,,0,
WSPro=,,,, 1 ,,,, 0 ,,,, 0 ,,,,-1 ,-1 ,-1 , 0 , 0 , 0 , 0 , 0
Multiple Barrel Culv=2,8,11,186.6,0.011,0.4,1,8,1,96.4,95.8, 2,Culvert #1  , 0 ,115
   828.5   972.5   840.5   984.5
Culvert Bottom n=0.011
BC Design=,, 0 ,, 0 ,,,,,,
BC Use User HTab Curves=0
BC User HTab FreeFlow(D)= 0

Type RM Length L Ch R = 1 ,2875    ,268.51,335.98,408.8
BEGIN DESCRIPTION:
Surveyed Section
END DESCRIPTION:
XS GIS Cut Line= 6
 2297431.9990923  715246.0257048 2296812.3208083  715052.7315611
 2296646.3003866  714957.1249037    2296584.3399      714901.852
    2296479.0304     714860.0816 2295701.8270026  714775.0895309
#Sta/Elev= 30
       0  116.57   88.19  122.15   98.74  120.95  117.73  123.96  175.74  123.12
  205.08  127.31  223.91  124.77  243.89  128.09  282.35  127.02   316.7  130.09
  353.45  128.11  377.93   129.8  382.19   129.4  425.46   107.4  514.01  106.02
  591.82   108.1  627.29   125.1  658.04  129.68  861.01  103.13  968.09   98.86
  971.58      96  977.59   95.85  984.61   95.93  986.77   98.74  994.39  101.09
 1117.33  100.85 1202.43  104.63 1498.89  110.42 1576.82  115.67 1819.55  122.38
#Mann= 5 ,-1 , 0
       0     .04       0  861.01     .07       0  968.09     .05       0
  986.77     .07       0 1576.82     .04       0
#XS Ineff= 2 , 0
       0     951     129    1008       0     123
Permanent Ineff=
       F       F
Bank Sta=968.09,986.77
XS Rating Curve= 0 ,0
Exp/Cntr=0.5,0.3

Type RM Length L Ch R = 1 ,2539    ,239.25,440.31,515.71
XS GIS Cut Line= 4
 2296846.4370578  714999.9134161 2296857.1328874  714887.6072059
 2296776.9141657  714569.4062767 2296608.4548503  714128.2033077
#Sta/Elev= 30
       0  104.62   18.08  104.35   31.52   104.8    52.9  103.96   77.97  103.98
  159.19   101.5  243.71   99.89  273.97   98.64  282.76   94.85  289.05    96.1
  293.32   98.73   311.1   98.29   392.7   100.4  421.79   99.78  453.24  100.46
  505.99   99.52  511.36   99.89  539.45  104.69  598.47  121.84  611.58   122.6
  639.09  122.62     667  123.32  712.72  122.98   766.9  121.25  799.84  121.11
  843.93  119.89   865.9  119.87  886.94   116.5  893.88  115.94  913.24  113.94
#Mann= 8 ,-1 , 0
       0     .04       0   18.08     .07       0  273.97     .05       0
  293.32     .07       0  639.09    .045       0  843.93     .09       0
  886.94    .045       0  893.88     .09       0
#XS Ineff= 2 , 0
       0                     440       0     105
Permanent Ineff=
       F       F
Bank Sta=273.97,293.32
XS Rating Curve= 0 ,0
Exp/Cntr=0.5,0.3

Type RM Length L Ch R = 1 ,2099    ,240.51,227.53,209.87
BEGIN DESCRIPTION:
Surveyed Section
END DESCRIPTION:
XS GIS Cut Line= 6
 2296819.2692906  715045.7830788    2297162.5744     714765.9263
    2297208.3201     714730.7092    2297219.4637      714724.756
    2297277.1369     714675.5261 2297535.1660081   714485.879662
#Sta/Elev= 30
       0     126   50.03   106.2  107.39  103.72  137.64  104.35  155.07  103.22
  209.22  102.83  250.85  101.57  268.37   103.1  277.11  102.52  384.53   97.76
 389.786   95.72 477.916    98.1 490.259   95.17  492.82   93.69   500.9   93.54
 507.037   94.78 513.756   95.73 521.048   93.81 529.031    97.5 557.887   96.58
  589.79  102.16  597.95   98.78  615.74   97.74  643.44   99.91  687.83   98.17
  715.85  100.17  731.87  104.07  749.19  106.65  779.45  108.83  910.04  108.42
#Mann= 7 ,-1 , 0
       0     .04       0  107.39     .08       0  209.22     .04       0
  277.11     .07       0 490.259     .05       0 507.037     .07       0
  779.45     .04       0
#XS Ineff= 2 , 0
       0     458  106.57   546.5       0  107.15
Permanent Ineff=
       F       F
Bank Sta=490.259,507.037
XS Rating Curve= 0 ,0
Exp/Cntr=0.5,0.3