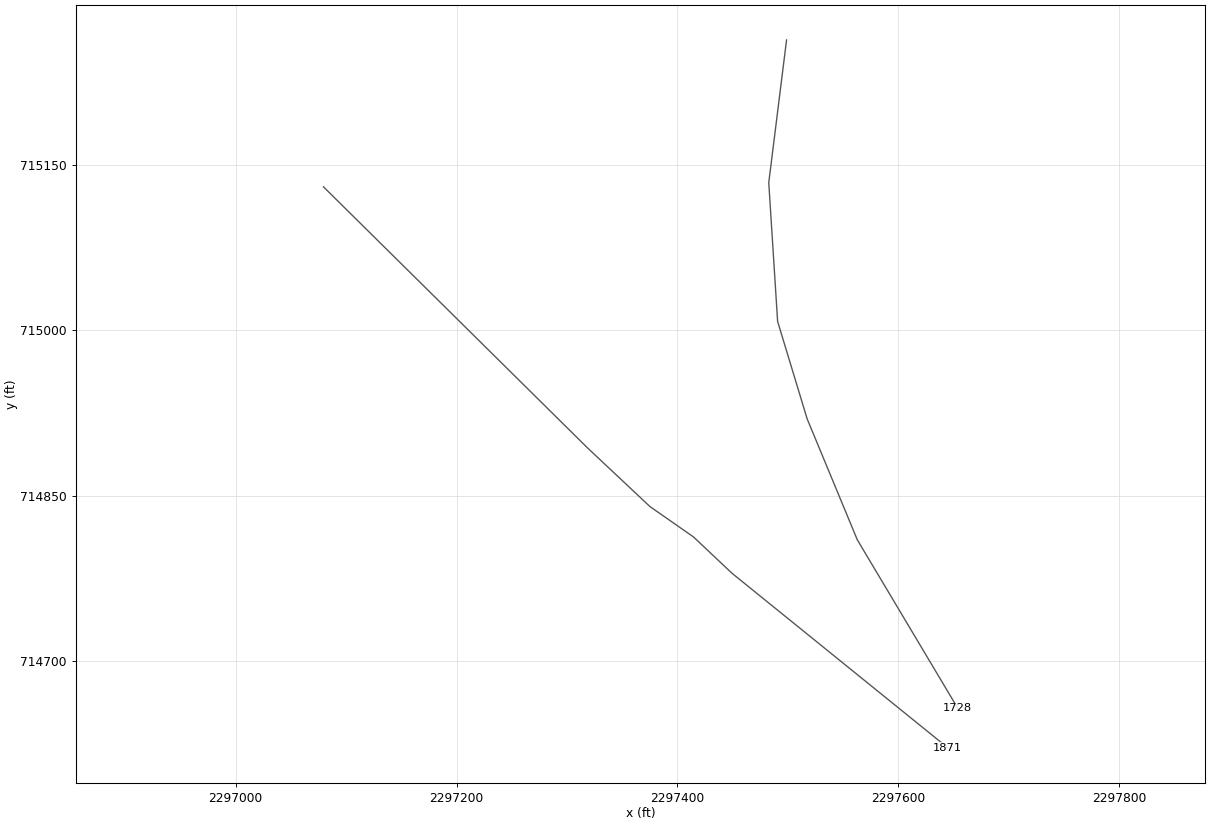
HEC-RAS study DTL_Mill_Branch_into_Contentnea.prj: DTL_Mill_Branch_into_Contentnea

--- DTL_Mill_Branch_into_Contentnea.g01 (geometry) --- (continued)

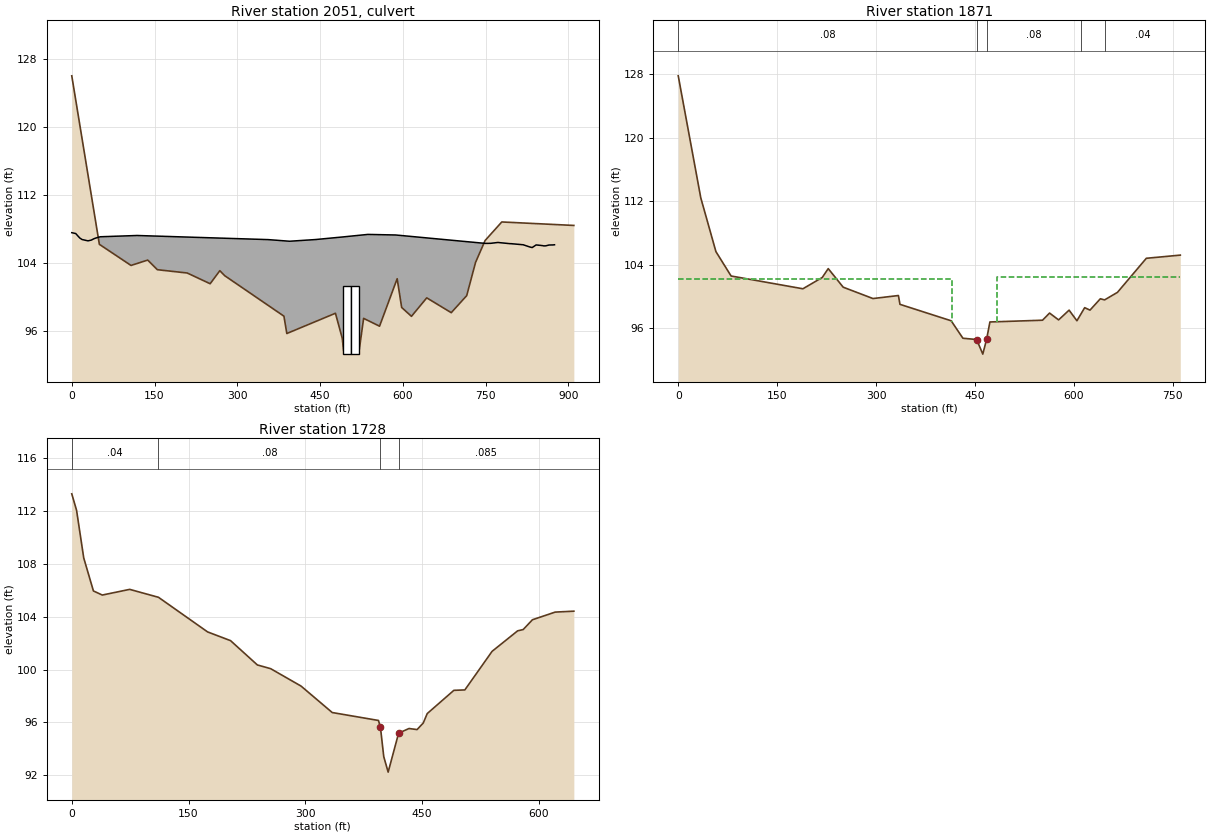
Type RM Length L Ch R = 2 ,2051    ,,,
BEGIN DESCRIPTION:
HWY 264
END DESCRIPTION:
Bridge Culvert--1,0,-1,-1, 0
Deck Dist Width WeirC Skew NumUp NumDn MinLoCord MaxHiCord MaxSubmerge Is_Ogee
45,132,2.6,0, 35, 35, , , 0.95, 0, 0,0,,
       0    7.14    14.4   16.48   18.49   29.38   35.36   39.58   43.58    51.6
  118.62 356.038   394.8  442.05  490.35 536.725 587.038  749.86  759.42  772.39
  793.77  794.98  795.18  795.84  814.69  818.26  829.72  834.45  841.67  853.36
  855.09  858.88  865.06  872.09     875
  107.57  107.47  106.95  106.86  106.77  106.61   106.7  106.84  106.94  107.09
  107.24 106.756 106.565 106.765 107.064 107.367   107.3  106.31  106.32  106.42
  106.28  106.28  106.28  106.28  106.17  106.15   105.9  105.82  106.13  106.05
  106.02  106.02  106.12  106.13  106.15
                                                                                
                                                                                
                                                                                
                                        
       0    3.49    9.14   18.82   29.52   29.87   42.15   51.08   56.04   65.66
   88.84  135.22   135.9 369.532 422.118 471.214 508.572 551.085     662  664.06
  664.79  681.15  687.91  698.36  711.14  715.37  726.97  732.73  734.52   750.8
  758.22  769.05  782.21  787.46  793.16
  106.04  105.78  105.61  106.19  105.55  105.55  105.38  105.12  105.06  105.06
   105.7  105.62  105.59 103.863 103.944 104.222 104.536 104.811  104.83  104.94
  104.96   105.1  105.13   105.2  105.35  105.35  105.33  105.38  105.37  105.59
  105.57  105.61  105.71  105.77  105.81
                                                                                
                                                                                
                                                                                
                                        
BR Coef=-1 , 0 , 0 ,, 0 ,,,0.8,-1,,0,
WSPro=,,,, 1 ,,,, 0 ,,,, 0 ,,,,-1 ,-1 ,-1 , 0 , 0 , 0 , 0 , 0
Multiple Barrel Culv=2,8,14,172.053,0.011,0.4,1,8,1,93.3,92.8, 2,Culvert #1  , 0 ,27.5
   498.5  444.16   513.5  459.16
Culvert Bottom n=0.011
BC Design=,, 0 ,, 0 ,,,,,,
BC Use User HTab Curves=0
BC User HTab FreeFlow(D)= 0

Type RM Length L Ch R = 1 ,1871    ,216.58,143.36,98.78
BEGIN DESCRIPTION:
Surveyed Section
END DESCRIPTION:
XS GIS Cut Line= 6
 2297079.5215363  715129.7965465    2297318.6423      714893.369
    2297375.2003      714840.217     2297414.672     714812.6946
    2297449.5207      714779.811 2297644.7875096   714621.891525
#Sta/Elev= 30
       0  127.77    34.2   112.4   57.14  105.63   80.15  102.56  188.99  100.95
  218.32  102.37  227.42  103.49   250.1  101.15  295.25   99.72  333.82   100.1
 336.178   98.99 413.775   96.92 431.615   94.72   452.4   94.56  461.76   92.72
   467.7   94.65 472.539   96.77 552.298   96.99  562.99   97.89  576.68   97.03
  592.59   98.26  604.45   96.92  609.95   97.69  616.21   98.57  624.29   98.26
  639.93   99.69  646.42   99.55  665.94   100.5  709.68  104.79  761.21  105.19
#Mann= 5 ,-1 , 0
       0     .08       0   452.4     .05       0   467.7     .08       0
  609.95    .085       0  646.42     .04       0
#XS Ineff= 2 , 0
       0  414.56  102.23  482.63       0  102.45
Permanent Ineff=
       F       F
Bank Sta=452.4,467.7
XS Rating Curve= 0 ,0
Exp/Cntr=0.5,0.3

Type RM Length L Ch R = 1 ,1728    ,195.27,155.62,124.03
XS GIS Cut Line= 6
 2297498.9636762  715262.8796213 2297482.8389161  715133.6112855
 2297490.8607882  715007.9352883 2297517.6003622  714919.6946945
 2297563.0576377  714810.0624416 2297653.9721889  714657.6468705
#Sta/Elev= 30
       0   113.3    6.18  112.05   15.37  108.45   27.83  105.95   39.24  105.64
   74.42  106.07  111.42  105.47  174.54  102.85  204.03  102.19   238.5  100.35
  255.54  100.07  294.67   98.75  334.67   96.75  394.05   96.15  396.56   95.68
  400.88   93.42  406.55   92.24     420   95.19  433.32   95.54  443.73   95.46
  451.67   95.96  456.75   96.67  491.01   98.43  505.09   98.46  540.11  101.38
   572.9  102.93  580.07  103.03  591.94  103.77  621.17  104.35  645.16  104.42
#Mann= 4 ,-1 , 0
       0     .04       0  111.42     .08       0  396.56     .05       0
     420    .085       0
Bank Sta=396.56,420
XS Rating Curve= 0 ,0
Exp/Cntr=0.3,0.1