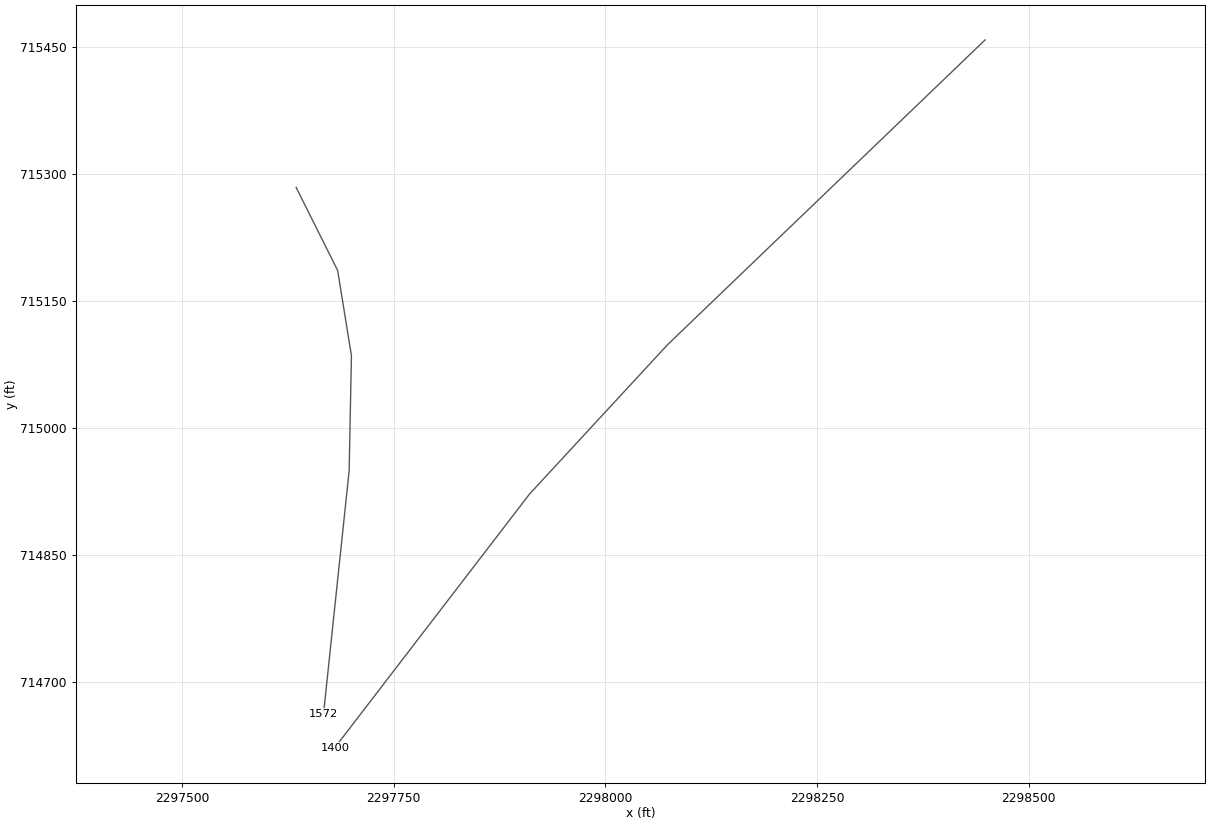
HEC-RAS study DTL_Mill_Branch_into_Contentnea.prj: DTL_Mill_Branch_into_Contentnea

--- DTL_Mill_Branch_into_Contentnea.g01 (geometry) --- (continued)

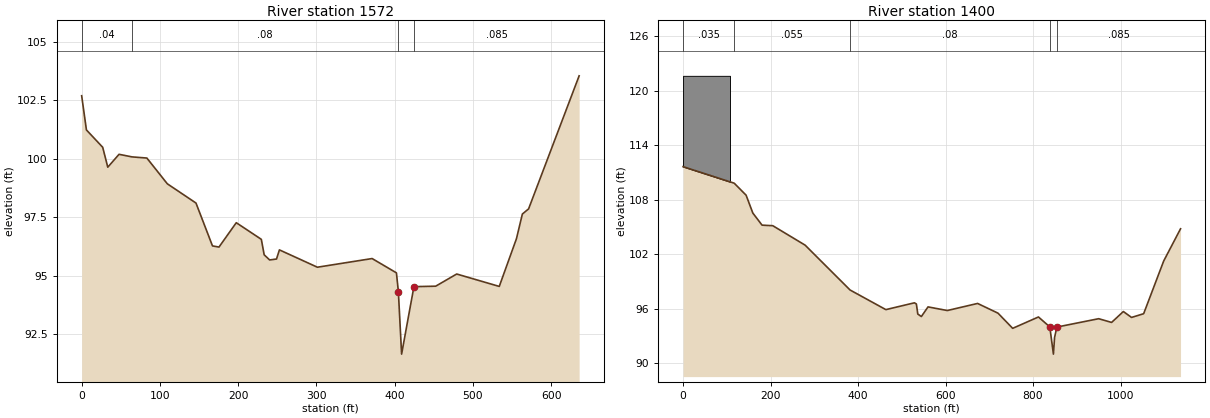
Type RM Length L Ch R = 1 ,1572    ,244.09,172.64,130.31
XS GIS Cut Line= 5
 2297634.9936304  715284.3043391 2297683.9644139  715186.3627721
 2297700.2880084  715085.7006059 2297697.5674094  714949.6706517
 2297667.3419759  714662.9947853
#Sta/Elev= 30
       0  102.69    6.09  101.23   26.88  100.49   33.38   99.64   47.79  100.19
   64.28  100.08   83.35  100.03   109.5   98.93  146.09   98.11   167.2   96.28
   175.5   96.23   197.6   97.27  229.64   96.56  233.26    95.9  240.27   95.68
  249.04   95.72  252.74   96.11  301.27   95.37  371.22   95.74  402.27   95.13
  404.77   94.33   408.9   91.66  424.64   94.54  452.48   94.56  479.31   95.08
  533.71   94.55  555.72   96.59  563.24   97.64   571.2   97.86   635.8  103.54
#Mann= 4 ,-1 , 0
       0     .04       0   64.28     .08       0  404.77     .05       0
  424.64    .085       0
#XS Ineff= 2 , 0
       0     250             500       0
Permanent Ineff=
       F       F
Bank Sta=404.77,424.64
XS Rating Curve= 0 ,0
Exp/Cntr=0.3,0.1

Type RM Length L Ch R = 1 ,1400    ,1096.37,1399.63,1381.23
XS GIS Cut Line= 4
 2298448.4527568  715458.4226806 2298073.7834989  715098.8498395
 2297910.6720982  714922.3686519 2297680.7117628  714622.8854244
#Sta/Elev= 30
       0  111.65   116.9  109.83  144.07  108.51  159.52  106.54  180.58  105.21
  205.06  105.15  278.97  103.01  381.76   98.07  463.58   95.91  528.96   96.66
  533.36   96.53  536.61   95.42  544.76   95.15  559.98   96.21     604   95.81
  673.29   96.59  719.92   95.52  753.48   93.85  812.36    95.1  838.34   94.01
  846.61   91.01  849.26   92.85  854.56   93.99  950.09   94.91   979.6    94.5
 1006.48    95.7 1025.14   95.05 1052.89   95.46 1098.66  101.26  1137.2  104.81
#Mann= 5 ,-1 , 0
       0    .035       0   116.9    .055       0  381.76     .08       0
  838.34     .05       0  854.56    .085       0
#XS Ineff= 2 , 0
       0     670             975       0
Permanent Ineff=
       F       F
#Block Obstruct= 1 ,-1
       0  107.21 121.651
Bank Sta=838.34,854.56
XS Rating Curve= 0 ,0
Exp/Cntr=0.3,0.1

Chan Stop Cuts=-1
Use User Specified Reach Order=0
User Specified Reach Order=Mill Branch     ,Trib