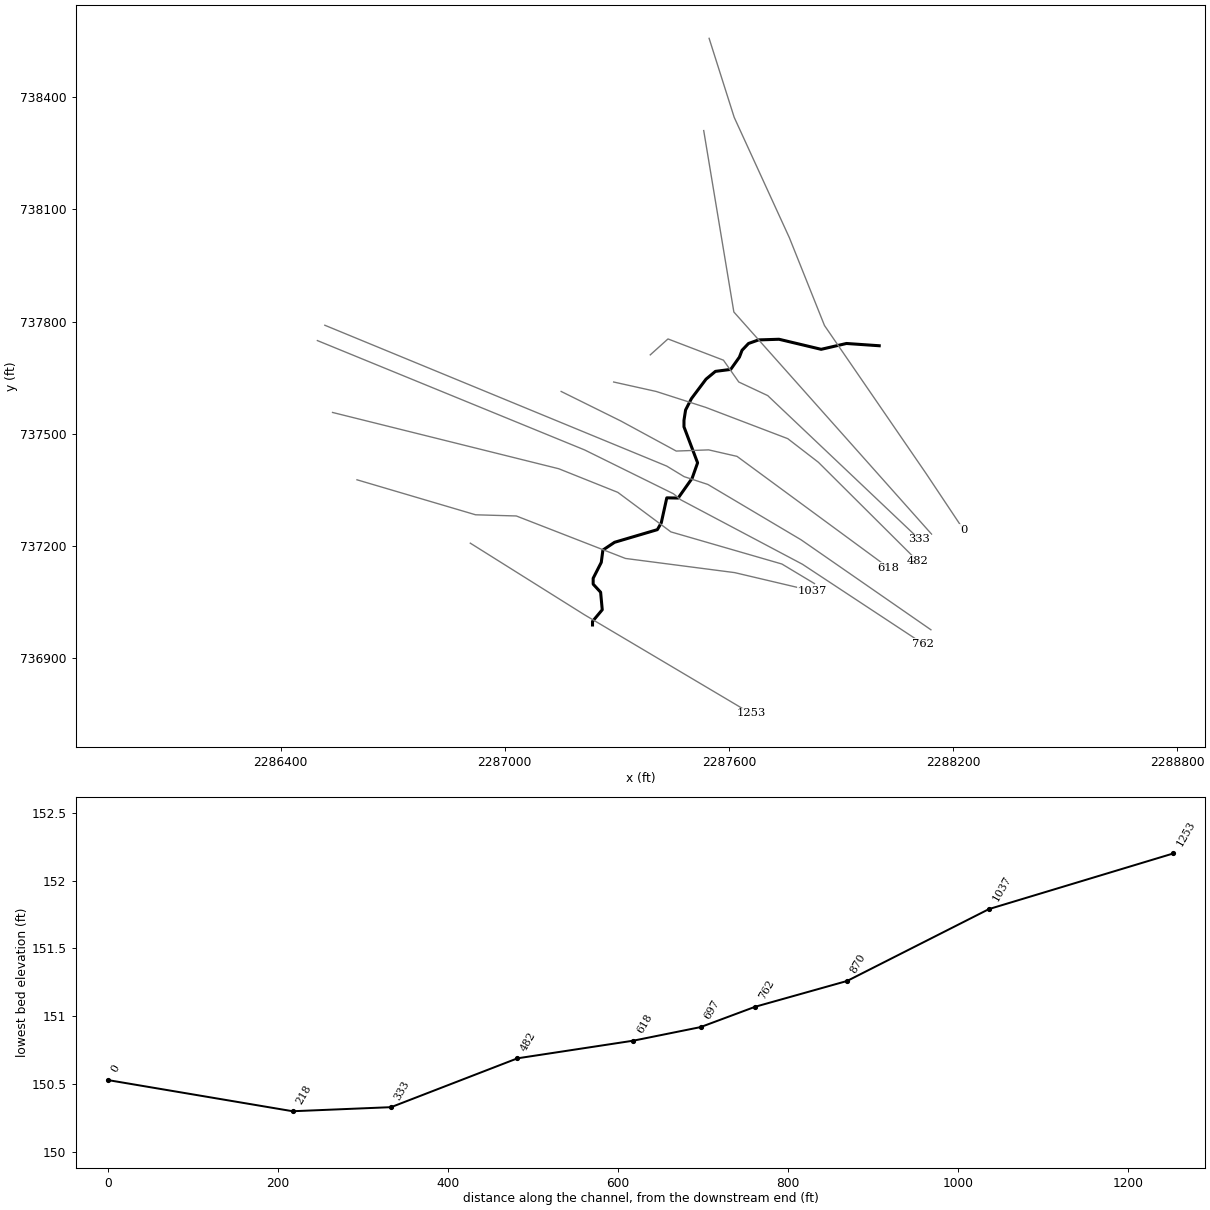
--- DTL_Millstone_Creek.prj (project) ---

Proj Title=DTL_Millstone_Creek
Current Plan=p01
Default Exp/Contr=0.3,0.1
English Units
Geom File=g01
Flow File=f01
Flow File=f02
Plan File=p01
Plan File=p02
Y Axis Title=Elevation
X Axis Title(PF)=Main Channel Distance
X Axis Title(XS)=Station
BEGIN DESCRIPTION:
END DESCRIPTION:
DSS File=dss
DSS Export Rating Curves= 0
DSS Export Rating Curve Sorted= 0
DSS Export Volume Flow Curves= 0
DXF OffsetX= 0
DXF OffsetY= 0
DXF ScaleX= 1
DXF ScaleY= 10

--- DTL_Millstone_Creek.p01 (plan) ---

Plan Title=DTL_Millstone_Creek
Program Version=4.00
Short Identifier=Multi Profile
Geom File=g01
Flow File=f01
Subcritical Flow
K Sum by GR= 0
Std Step Tol= 0.01
Critical Tol= 0.01
Num of Std Step Trials= 20
Max Error Tol= 0.3
Flow Tol Ratio= 0.001
Split Flow NTrial= 30
Split Flow Tol= 0.02
Split Flow Ratio= 0.02
Log Output Level= 0
Friction Slope Method= 1
Unsteady Friction Slope Method= 2
Unsteady Bridges Friction Slope Method= 1
Parabolic Critical Depth
Global Vel Dist= 0 , 0 , 0
Global Log Level= 0
CheckData=True
Encroach Param=-1 ,10,10, 2
Encroach River=Milltone
Encroach Reach=Creek
Encroach Node=1253
       1     310     430
Encroach Node=1037
       1     650     770
Encroach Node=870
       1     850     970
Encroach Node=762
       1    1017    1092
Encroach Node=697
       1    1025    1100
Encroach Node=618
       1     367     510
Encroach Node=482
       1     188     356
Encroach Node=333
       1     195     380
Encroach Node=218
       1     480     700
Encroach Node=0
       1     811     944
Computation Interval=1HOUR
Output Interval=1HOUR
Run HTab= 0
Run UNet= 0
Run PostProcess= 0
Run WQNet= 0
UNET Theta= 1
UNET Theta Warmup= 1
UNET ZTol= 0.02
UNET ZSATol= 0.05
UNET MxIter= 20
UNET MaxInSteps= 0
UNET DtIC= 0
UNET DtMin= 0
UNET MaxCRTS= 20
UNET WFStab= 2
UNET SFStab= 1
UNET WFX= 1
UNET SFX= 1
UNET DSS MLevel= 4
UNET DZMax Abort= 100
UNET Convert EG Bridges=-1
UNET Use Existing IB Tables=-1
UNET Froude Reduction=False
UNET Froude Limit= 1
UNET Froude Power= 10
UNET Time Slicing=0,0, 5
Instantaneous Interval=1HOUR
DSS File=dss
Write IC File= 0
Echo Input=False
Echo Output=False
Write Detailed= 0
Detailed Automatic Start=False, 10
WQ ULTIMATE=-1
WQ Max Comp Step=1HOUR
WQ Output Interval=15MIN
WQ Output Selected Increments= 0
WQ Output face flow=0
WQ Output face velocity=0
WQ Output face area=0
WQ Output face dispersion=0
WQ Output cell volume=0
WQ Output cell surface area=0
WQ Output cell continuity=0
WQ Output face conc=0
WQ Output face dconc_dx=0
WQ Output face courant=0
WQ Output face peclet=0
WQ Output face adv mass=0
WQ Output face disp mass=0
WQ Output cell mass=0
WQ Output cell source sink temp=0
WQ Output cell source sink nsm=0
WQ Output MaxMinRange=-1
WQ Daily Max Min Mean=-1
WQ Daily Range=0
WQ Daily Time=0
WQ Create Restart=0
WQ Fixed Restart=0
WQ System Summary=False
Sorting and Armoring Iterations= 10
XS Update Threshold= 0.02
Hydraulics Update Threshold= 0.02
Energy Slope Method= 1
Volume Change Method= 0
XS Weighting Method= 0
Number of US Weighted Cross Sections= 1
Number of DS Weighted Cross Sections= 1
Upstream XS Weight=0.25
Main XS Weight=0.5
Downstream XS Weight=0.25
Number of DS XS's Weighted with US Boundary= 1
Upstream Boundary Weight= 1
Weight of XSs Associated with US Boundary= 0
Number of US XS's Weighted with DS Boundary= 1
Downstream Boundary Weight= 0.5
Weight of XSs Associated with DS Boundary= 0.5
Sediment Output Level= 4
Mass or Volume Output= 0
Output Increment Type= 1
Profile and TS Output Increment= 10
XS Output Flag= 0
XS Output Increment= 10
Disregard all LS=0
Disregard all Conn=0
Disregard all Breaches=0
Disregard all Pumps=0

--- DTL_Millstone_Creek.p02 (plan) ---

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Plan Title=DTL_Millstone_Creek_Future
Short Identifier=Future
Geom File=g01
Flow File=f02
Encroach Param=-1 ,0,0, 2

--- DTL_Millstone_Creek.f01 (steady flow) ---

Flow Title=DTL_Millstone_Creek
Program Version=4.00
Number of Profiles= 6
Profile Names=100-yr,FW,10-yr,25-yr,50-yr,500-yr
River Rch & RM=Milltone,Creek           ,1253
    1927    1927     914    1270    1581    2911
River Rch & RM=Milltone,Creek           ,1037
    1930    1930     910    1270    1580    2910
Boundary for River Rch & Prof#=Milltone,Creek           , 1
Up Type= 0
Dn Type= 1
Dn Known WS=155.06
Boundary for River Rch & Prof#=Milltone,Creek           , 2
Up Type= 0
Dn Type= 1
Dn Known WS=156
Boundary for River Rch & Prof#=Milltone,Creek           , 3
Up Type= 0
Dn Type= 1
Dn Known WS=153.89
Boundary for River Rch & Prof#=Milltone,Creek           , 4
Up Type= 0
Dn Type= 1
Dn Known WS=154.38
Boundary for River Rch & Prof#=Milltone,Creek           , 5
Up Type= 0
Dn Type= 1
Dn Known WS=154.73
Boundary for River Rch & Prof#=Milltone,Creek           , 6
Up Type= 0
Dn Type= 1
Dn Known WS=155.88
DSS Import GetInterval= 0
DSS Import GetPeak= 0
DSS Import FillOption= 0

--- DTL_Millstone_Creek.f02 (steady flow) ---

Flow Title=DTL_Millstone_Creek_Future
Program Version=4.00
Number of Profiles= 3
Profile Names=100-yr-10%,100-yr-20%,100-yr-35%
River Rch & RM=Milltone,Creek           ,1253
    2102    2694    3291
River Rch & RM=Milltone,Creek           ,1037
    2100    2690    3290
Boundary for River Rch & Prof#=Milltone,Creek           , 1
Up Type= 0
Dn Type= 1
Dn Known WS=156.11
Boundary for River Rch & Prof#=Milltone,Creek           , 2
Up Type= 0
Dn Type= 1
Dn Known WS=156.59
Boundary for River Rch & Prof#=Milltone,Creek           , 3
Up Type= 0
Dn Type= 1
Dn Known WS=157.01
DSS Import GetInterval= 0
DSS Import GetPeak= 0
DSS Import FillOption= 0

--- DTL_Millstone_Creek.g01 (geometry) ---

Geom Title=DTL_Millstone_Creek
Program Version=4.00

River Reach=Milltone        ,Creek
Reach XY= 30
2287235.07287408736987.8023426092287235.07287408736997.350953713
2287261.11454071737028.6009537132287256.77426293737075.475953728
2287236.80898516737097.1773425942287236.80898516737112.802342594
2287258.51037407737155.3370648182287262.85065183737188.323175937
2287294.10065186737209.1565092652287408.68398519737243.010675967
2287419.10065186737261.2398425942287433.85759631  737328.0801204
2287464.29640047737327.5850187842287501.72898056737380.579457998
2287516.32287407  737421.83012042287479.86454071737518.184287056
2287479.86454071737535.5453981762287484.20481855737563.323175952
2287499.82981849737593.7051203852287538.89231855737645.788453713
2287564.06592961737666.6217870562287604.86454073  737671.8301204
2287628.30204071737704.8162314892287635.24648517737723.045398161
2287652.60759632737741.2745648182287679.51731852737750.823175952
2287734.20481852737752.5592870412287847.05204073737725.649564832
2287914.76000001737741.2699999962288002.43000001737735.200000018

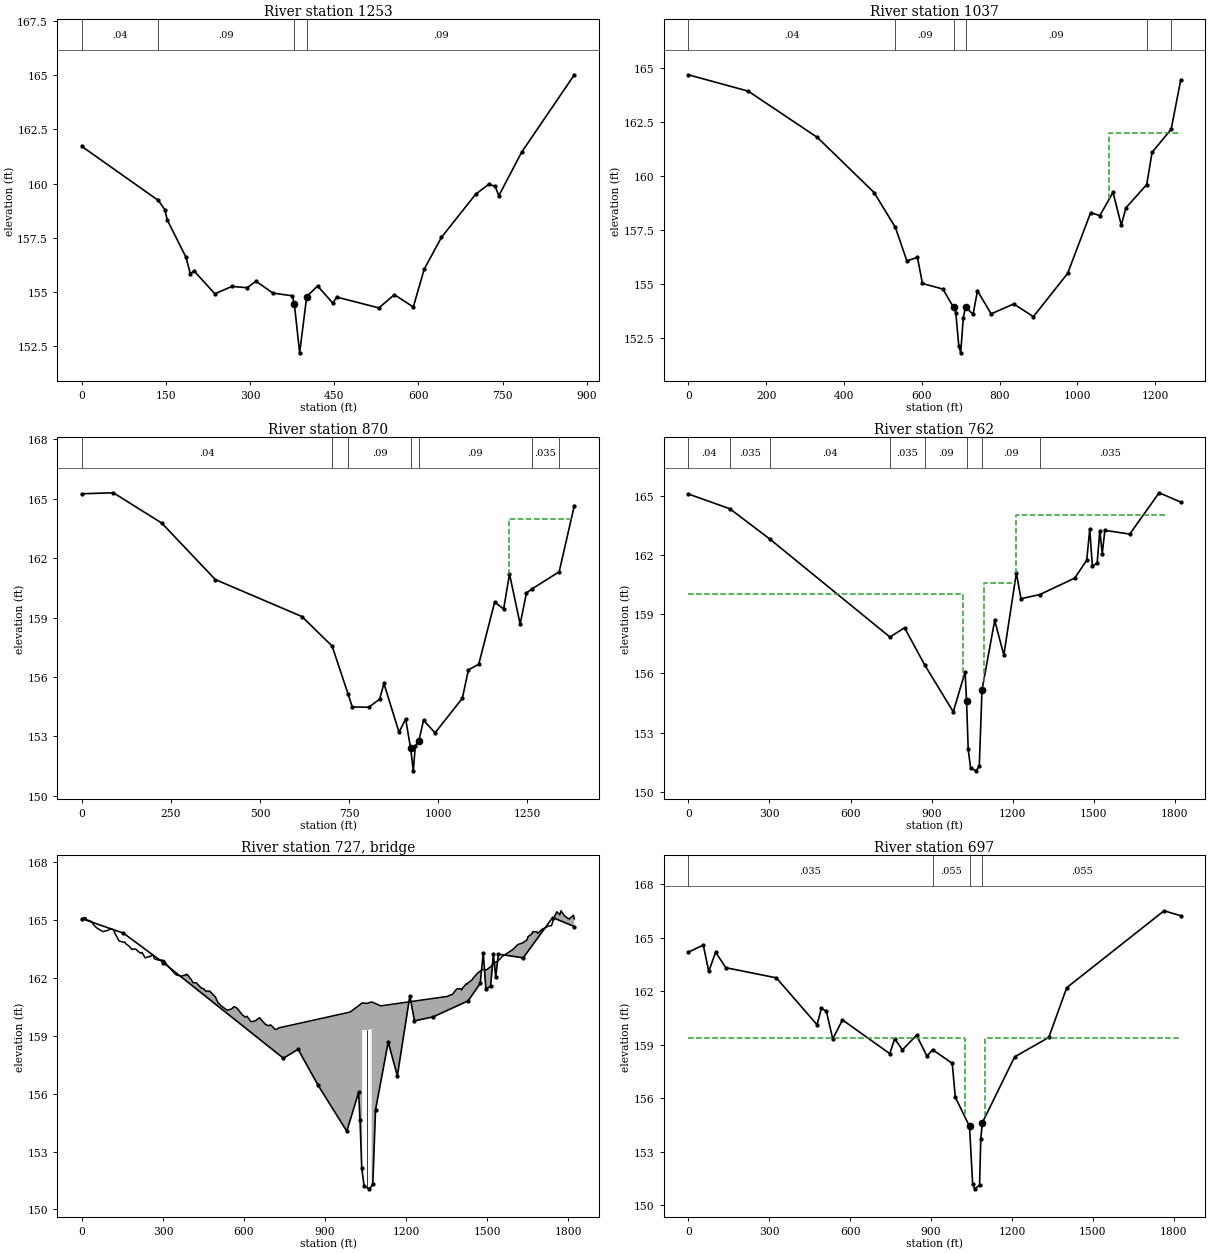
Type RM Length L Ch R = 1 ,1253    ,176.68,216.86,239.64
XS GIS Cut Line= 3
2286907.99999402737206.812538937 2287212.7500373737015.625032723
2287658.50002609736751.250020206
#Sta/Elev= 30
       0  161.71  136.36  159.22  148.11  158.79  152.14  158.33  185.73   156.6
  193.45  155.83  199.87  155.98   237.1  154.92  267.65  155.26  294.68   155.2
  310.48   155.5  340.72  154.95  375.05  154.83  378.77154.4667  388.29   152.2
   400.9  154.79  420.28  155.28  447.49  154.49  454.23  154.77  529.63  154.27
  557.29  154.88  590.89  154.31  610.42  156.06  641.12  157.52  702.17  159.51
  725.25  159.96  736.66  159.88  743.42  159.44  783.99  161.44  878.01  165.01
#Mann= 4 ,-1 , 0
       0     .04       0  136.36     .09       0  378.77     .05       0
   400.9     .09       0
Bank Sta=378.77,400.9
XS Rating Curve= 0 ,0
Exp/Cntr=0.3,0.1

Type RM Length L Ch R = 1 ,1037    ,92.41,166.95,151.08
XS GIS Cut Line= 6
 2286604.6499063  737376.4483152 2286922.1549807  737282.7637632
 2287031.1348868  737279.6049253 2287323.3273885  737165.8867624
 2287615.5198904  737127.9807082  2287824.372459  737078.8004873
#Sta/Elev= 30
       0   164.7  153.92  163.94  331.76  161.79  477.55  159.23  532.15  157.61
  561.56  156.06   588.8  156.22  601.61  155.01  654.25  154.75  681.61   153.9
  687.35  153.66  695.11  152.09  700.01  151.79  706.59  153.43  712.33  153.91
  731.79  153.58  743.07  154.67  778.17   153.6  836.21  154.06  886.75  153.47
  974.82  155.48 1033.89   158.3 1057.45  158.16 1091.32  159.24 1112.64  157.72
 1124.36  158.52 1177.95   159.6 1191.76   161.1 1240.72  162.17 1265.52  164.47
#Mann= 6 ,-1 , 0
       0     .04       0  532.15     .09       0  681.61     .05       0
  712.33     .09       0 1177.95    .035       0 1240.72    .055       0
#XS Ineff= 2 , 0
       0                    1082       0     162
Permanent Ineff=
       F       F
Bank Sta=681.61,712.33
XS Rating Curve= 0 ,0
Exp/Cntr=0.3,0.1

Type RM Length L Ch R = 1 ,870     ,79.16,108.05,87.09
XS GIS Cut Line= 6
 2286539.2778855  737556.6630751 2287144.8530496  737405.9584396
 2287302.7949425  737342.7816825  2287444.942646  737236.9606142
 2287741.9888515  737150.9972023 2287829.1374191  737098.6544875
#Sta/Elev= 30
       0  165.25   88.45   165.3  224.36  163.77  374.58  160.92  617.88  159.05
  702.62  157.56  747.55  155.13  759.15  154.49  805.33  154.47  836.05  154.88
  848.03  155.67  890.46  153.21     909  153.88  923.04  152.39  930.46  151.26
  936.24  152.53  946.09  152.77  959.16  153.81  991.67  153.18 1068.09  154.92
 1085.31  156.36 1114.17  156.64 1158.91  159.78 1184.18  159.43 1200.55   161.2
 1230.47  158.67 1248.13  160.24 1263.25  160.44 1339.98  161.31 1382.56  164.65
#Mann= 7 ,-1 , 0
       0     .04       0  702.62    .035       0  747.55     .09       0
  923.04     .05       0  946.09     .09       0 1263.25    .035       0
 1339.98    .055       0
#XS Ineff= 2 , 0
       0                    1200       0     164
Permanent Ineff=
       F       F
Bank Sta=923.04,946.09
XS Rating Curve= 0 ,0
Exp/Cntr=0.5,0.3

Type RM Length L Ch R = 1 ,762     ,58.92,64.28,69.59
XS GIS Cut Line= 6
 2286498.7077181  737749.0486916 2287213.9735352  737456.3167475
    2287451.8174     737338.9379    2287471.7946     737322.5675
 2287797.0008484   737150.346303 2288120.6308801  736937.0171435
#Sta/Elev= 30
       0  165.08  153.76  164.33  301.32   162.8  745.83  157.84  799.76  158.31
  874.45  156.43 980.113 154.056 1023.86  156.07 1029.18  154.62 1035.39  152.15
 1044.26  151.21 1063.97  151.07 1076.31   151.3  1086.4  155.16 1133.32  158.68
 1167.17  156.93 1213.51  161.08 1230.44  159.78  1300.2  159.99 1429.09  160.82
 1473.69  161.72 1484.98  163.29 1494.68  161.44  1512.3  161.57 1522.28  163.23
 1531.13  162.05 1540.88  163.24 1632.93  163.05 1741.57  165.14 1821.77  164.67
#Mann= 8 ,-1 , 0
       0     .04       0  153.76    .035       0  301.32     .04       0
  745.83    .035       0  874.45     .09       0 1029.18     .05       0
  1086.4     .09       0  1300.2    .035       0
#XS Ineff= 3 ,-1
       0    1017     160    1092    1213   160.6    1213    1770     164
Permanent Ineff=
       F       F       F
Bank Sta=1029.18,1086.4
XS Rating Curve= 0 ,0
Exp/Cntr=0.5,0.3

Type RM Length L Ch R = 3 ,727     ,,,
BEGIN DESCRIPTION:
Countryside Rd
END DESCRIPTION:
Bridge Culvert--1,0,-1,-1, 0
Deck Dist Width WeirC Skew NumUp NumDn MinLoCord MaxHiCord MaxSubmerge Is_Ogee
21.7,27,2.6,0, 157, 157, , , 0.95, 0, 0,0,,
       0    1.96    9.51   15.03   17.86   25.42   36.33   43.43   56.99   78.06
   78.08   78.12    97.4  105.33  117.28  123.63  137.48  154.58  157.91  164.38
  173.14  180.54  185.67  191.58   200.2   204.3  206.99  216.87  222.85   228.2
   234.1  249.41  251.12  252.51   263.7  267.97  282.46  283.74  284.29  286.54
  304.77  314.19  326.05  345.91  347.19  347.83  349.75  368.17   381.9  387.84
  389.03  390.17  397.36  405.34  410.05  415.07  423.01  440.01  440.49  452.42
  457.39  472.13  473.34  473.85  475.65  494.06  503.48  514.47  534.29  535.01
  536.42  553.99  562.93  572.73  577.19  592.05  604.97  611.29  625.73  629.45
  632.58  643.69  656.49  658.16  659.06  678.41  690.23  698.76  714.91  719.33
  729.15 992.771    1037  1054.5    1072 1105.88 1352.14 1362.28 1370.78 1382.43
 1389.34 1402.44 1405.26 1407.96  1422.5 1424.56 1426.48 1442.57 1443.89  1445.1
 1462.43 1463.48 1477.07 1481.33 1482.04 1497.54 1500.94 1513.64 1519.79 1529.67
 1538.45 1550.78 1555.85 1557.48 1575.05 1575.71 1587.93 1593.99 1594.29 1611.72
 1612.93 1629.54 1631.63 1647.33 1650.24 1651.11 1665.24 1668.49 1683.39 1686.81
 1701.49 1705.06  1719.6  1723.3 1737.52 1745.52 1750.36 1757.13 1767.94 1772.39
 1785.58 1787.52  1799.7 1803.02  1803.6 1818.75 1821.88
  164.99  165.01  165.14  165.12  165.02  164.99  164.93  164.76  164.58  164.41
  164.41  164.41  164.48  164.56  164.51  164.28  163.93  163.85  163.87  163.76
  163.67  163.57  163.48  163.51   163.5  163.43   163.4  163.29  163.33  163.19
  163.05  163.11  163.13  163.12   163.2     163  162.94  162.95  162.93  162.95
  162.91  162.69  162.51   162.2  162.19  162.18  162.16   162.1  162.16   162.2
  162.14  162.19  162.06  161.91  161.77  161.76  161.76  161.51   161.5  161.43
  161.33  161.32   161.3  161.31  161.29  161.02  160.74  160.57  160.37  160.36
  160.33   160.4  160.52  160.46  160.39  160.12  159.97  160.02  159.74  159.74
  159.75   159.8  159.94  159.94  159.91  159.61  159.53  159.57  159.34  159.34
  159.42  160.24 160.712 160.686 160.765  160.56  161.05  161.12  161.15  161.37
  161.45  161.44  161.38  161.47  161.71  161.67  161.73   161.9  161.91  161.95
  162.23  162.25   162.4  162.44  162.45  162.43  162.47  162.61  162.71  162.82
  162.87  163.06  163.13  163.14   163.3   163.3  163.42  163.48  163.48  163.73
  163.74  163.82  163.83  163.99  164.14  164.15   164.3  164.41   164.4  164.32
  164.52  164.55  164.64  164.69  164.72  165.08  165.25  165.44  165.28  165.49
  165.23  165.21  165.08  165.09  165.07  165.26  165.07
                                                                                
                                                                                
                                                                                
                                                                                
                                                                                
                                                                                
                                                                                
                                                                                
                                                                                
                 159.312 159.286 159.365
                                                                                
                                                                                
                                                                                
                                                                                
                                                                                
                                                        
       0    1.96    9.51   15.03   17.86   25.42   36.33   43.43   56.99   78.06
   78.08   78.12    97.4  105.33  117.28  123.63  137.48  154.58  157.91  164.38
  173.14  180.54  185.67  191.58   200.2   204.3  206.99  216.87  222.85   228.2
   234.1  249.41  251.12  252.51   263.7  267.97  282.46  283.74  284.29  286.54
  304.77  314.19  326.05  345.91  347.19  347.83  349.75  368.17   381.9  387.84
  389.03  390.17  397.36  405.34  410.05  415.07  423.01  440.01  440.49  452.42
  457.39  472.13  473.34  473.85  475.65  494.06  503.48  514.47  534.29  535.01
  536.42  553.99  562.93  572.73  577.19  592.05  604.97  611.29  625.73  629.45
  632.58  643.69  656.49  658.16  659.06  678.41  690.23  698.76  714.91  719.33
  729.15 992.771    1045  1062.5    1080 1105.88 1352.14 1362.28 1370.78 1382.43
 1389.34 1402.44 1405.26 1407.96  1422.5 1424.56 1426.48 1442.57 1443.89  1445.1
 1462.43 1463.48 1477.07 1481.33 1482.04 1497.54 1500.94 1513.64 1519.79 1529.67
 1538.45 1550.78 1555.85 1557.48 1575.05 1575.71 1587.93 1593.99 1594.29 1611.72
 1612.93 1629.54 1631.63 1647.33 1650.24 1651.11 1665.24 1668.49 1683.39 1686.81
 1701.49 1705.06  1719.6  1723.3 1737.52 1745.52 1750.36 1757.13 1767.94 1772.39
 1785.58 1787.52  1799.7 1803.02  1803.6 1818.75 1821.88
  164.99  165.01  165.14  165.12  165.02  164.99  164.93  164.76  164.58  164.41
  164.41  164.41  164.48  164.56  164.51  164.28  163.93  163.85  163.87  163.76
  163.67  163.57  163.48  163.51   163.5  163.43   163.4  163.29  163.33  163.19
  163.05  163.11  163.13  163.12   163.2     163  162.94  162.95  162.93  162.95
  162.91  162.69  162.51   162.2  162.19  162.18  162.16   162.1  162.16   162.2
  162.14  162.19  162.06  161.91  161.77  161.76  161.76  161.51   161.5  161.43
  161.33  161.32   161.3  161.31  161.29  161.02  160.74  160.57  160.37  160.36
  160.33   160.4  160.52  160.46  160.39  160.12  159.97  160.02  159.74  159.74
  159.75   159.8  159.94  159.94  159.91  159.61  159.53  159.57  159.34  159.34
  159.42  160.24 160.712 160.686 160.765  160.56  161.05  161.12  161.15  161.37
  161.45  161.44  161.38  161.47  161.71  161.67  161.73   161.9  161.91  161.95
  162.23  162.25   162.4  162.44  162.45  162.43  162.47  162.61  162.71  162.82
  162.87  163.06  163.13  163.14   163.3   163.3  163.42  163.48  163.48  163.73
  163.74  163.82  163.83  163.99  164.14  164.15   164.3  164.41   164.4  164.32
  164.52  164.55  164.64  164.69  164.72  165.08  165.25  165.44  165.28  165.49
  165.23  165.21  165.08  165.09  165.07  165.26  165.07
                                                                                
                                                                                
                                                                                
                                                                                
                                                                                
                                                                                
                                                                                
                                                                                
                                                                                
                 159.312 159.286 159.365
                                                                                
                                                                                
                                                                                
                                                                                
                                                                                
                                                        
Pier Skew, UpSta & Num, DnSta & Num=  ,1054.5, 2 ,1062.5, 2 , 0 , 0 , 0 ,,
      .8      .8
     150 159.365
      .8      .8
     150 159.365
BR Coef=-1 , 0 , 0 ,, 0 ,,2,0.8,0,,0,
WSPro=,,,, 1 ,,,, 0 ,,,, 0 ,,,,-1 ,-1 ,-1 , 0 , 0 , 0 , 0 , 0
BC Design=,, 0 ,, 0 ,,,,,,
BC Use User HTab Curves=0
BC User HTab FreeFlow(D)= 0

Type RM Length L Ch R = 1 ,697     ,54.03,79.06,97.65
XS GIS Cut Line= 6
 2286518.6066689  737790.0726651    2287433.7123     737413.1151
    2287480.2467      737384.868    2287543.7294     737363.9837
 2287793.3561386  737215.7827331 2288140.8240877  736974.9793637
#Sta/Elev= 30
       0  164.19   55.53  164.59    75.7  163.11  101.29  164.19     139  163.32
  326.23  162.75  477.25  160.12  493.46  161.04  511.71  160.88  535.36  159.33
  571.51  160.39   746.8   158.5  765.17  159.34  793.62  158.71  846.06  159.53
  884.74  158.36  905.58  158.72   978.4  157.96 989.745156.0615 1042.48  154.42
 1054.11   151.2  1061.8  150.92  1079.7  151.12 1084.28  153.72 1089.81  154.62
 1209.75  158.32 1336.39  159.41 1402.94   162.2 1763.72  166.51 1825.76  166.23
#Mann= 4 ,-1 , 0
       0    .035       0  905.58    .055       0 1042.48     .05       0
 1089.81    .055       0
#XS Ineff= 2 , 0
       0    1025  159.37    1100       0  159.37
Permanent Ineff=
       F       F
Bank Sta=1042.48,1089.81
XS Rating Curve= 0 ,0
Exp/Cntr=0.5,0.3

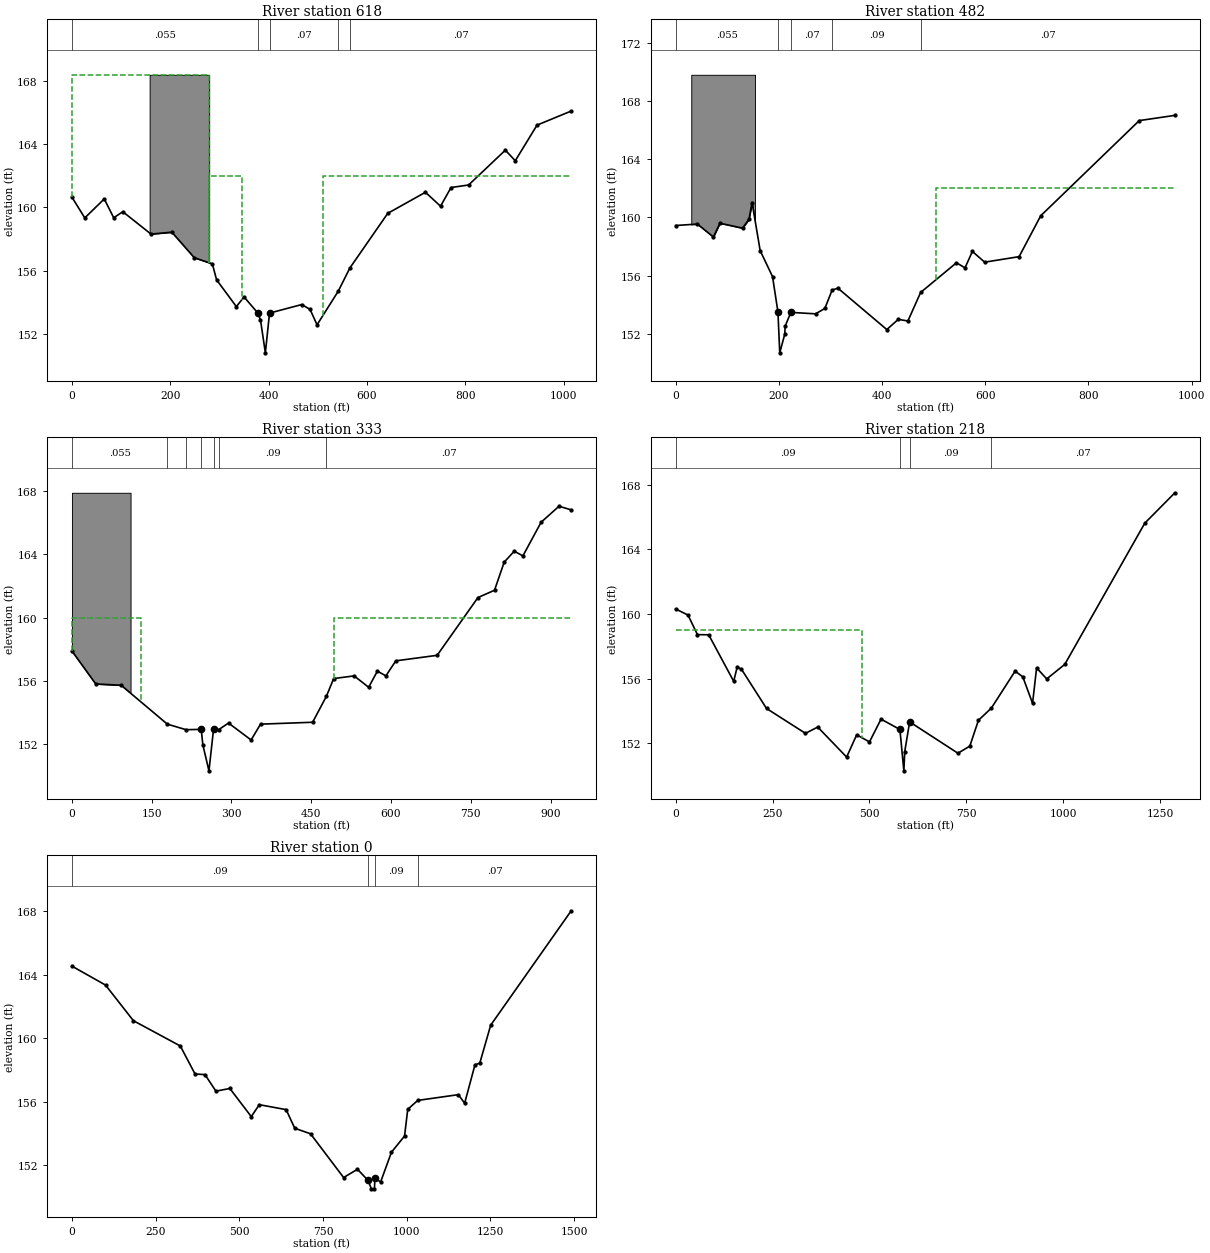
Type RM Length L Ch R = 1 ,618     ,151.26,136.26,98.63
XS GIS Cut Line= 6
 2287151.1707253  737612.8623193 2287310.6920371  737533.8913728
 2287459.1574164  737453.3410075 2287546.0254575  737456.4998453
 2287621.8375661  737439.1262371 2288027.5975906  737140.8431321
#Sta/Elev= 30
       0  160.65   26.11  159.34   65.74  160.54    84.9  159.35  103.47  159.73
  160.76  158.32  203.17  158.44  248.67  156.83  285.48  156.44  294.14  155.43
  334.32  153.74  349.97  154.35  377.57  153.35  383.38   152.9   393.3  150.82
  401.76  153.33  467.28  153.87  484.25  153.56  498.42  152.59  541.62  154.72
  565.17  156.18   642.2  159.63   718.8  160.96  749.49  160.08  770.82  161.26
  806.58  161.42   881.3  163.62  901.45  162.95  945.67   165.2 1015.21  166.09
#Mann= 5 ,-1 , 0
       0    .055       0  377.57     .05       0  401.76     .07       0
  541.62     .09       0  565.17     .07       0
#XS Ineff= 3 ,-1
       0  279.07  168.38  279.07     345     162     510    1100     162
Permanent Ineff=
       F       F       F
#Block Obstruct= 1 ,-1
  157.96  279.07 168.379
Bank Sta=377.57,401.76
XS Rating Curve= 0 ,0
Exp/Cntr=0.3,0.1

Type RM Length L Ch R = 1 ,482     ,152.44,148.67,100.08
XS GIS Cut Line= 6
   2287291.73901  737638.1330222 2287405.4571729  737612.8623193
 2287538.1283629  737570.2180082  2287757.667594   737486.508805
 2287839.5890664  737423.3122406 2288104.1555197  737159.9826144
#Sta/Elev= 30
       0  159.44    42.1  159.54   73.17  158.65   85.81   159.6  129.67  159.26
  142.27  159.88  148.09  161.02  163.85  157.71  187.78  155.93  198.25   153.5
  201.76  150.69  211.45  151.97  212.33  152.53  223.31  153.47  271.23  153.37
  289.16  153.74  303.33  155.01  314.59  155.13  409.25  152.29   431.4  152.99
  450.13  152.88  474.78  154.84  544.24  156.88  560.78  156.53  575.08  157.66
  598.87  156.92  665.62   157.3  707.53  160.11  898.46  166.65  967.55  167.01
#Mann= 5 ,-1 , 0
       0    .055       0  198.25     .05       0  223.31     .07       0
  303.33     .09       0  474.78     .07       0
#XS Ineff= 2 , 0
       0                  504.41       0     162
Permanent Ineff=
       F       T
#Block Obstruct= 1 ,-1
   30.29  153.88 169.799
Bank Sta=198.25,223.31
XS Rating Curve= 0 ,0
Exp/Cntr=0.3,0.1

Type RM Length L Ch R = 1 ,333     ,145.39,115.77,85.38
XS GIS Cut Line= 6
 2287389.6629836  737710.7862929 2287437.0455514   737753.430604
 2287585.5109307  737696.5715225 2287626.5758229  737638.1330222
 2287703.9673504  737601.8063868 2288109.6239432  737217.4010612
#Sta/Elev= 30
       0   157.9   44.69  155.82   92.51  155.74   179.4  153.28  214.55  152.93
  243.14  152.95  246.14  151.97  257.61  150.33  266.23  152.95  276.28  152.94
   294.4  153.35  336.85  152.28  354.62  153.28  452.53   153.4  478.58  155.05
  492.11  156.16  530.61  156.33  557.84  155.61  574.34  156.63   590.3  156.33
  608.91  157.28  686.67  157.63  763.42  161.28  794.53  161.74  812.75  163.52
   831.7  164.21  847.85  163.91  882.21  166.04  915.83  167.05  938.75  166.82
#Mann= 7 ,-1 , 0
       0    .055       0   179.4     .09       0  214.55     .07       0
  243.14     .05       0  266.23     .07       0  276.28     .09       0
  478.58     .07       0
#XS Ineff= 2 , 0
       0     130     160  492.11       0     160
Permanent Ineff=
       F       F
#Block Obstruct= 1 ,-1
       0   110.2   167.9
Bank Sta=243.14,266.23
XS Rating Curve= 0 ,0
Exp/Cntr=0.3,0.1

Type RM Length L Ch R = 1 ,218     ,230.59,217.58,171.92
XS GIS Cut Line= 3
2287532.70526294738311.0857631562287613.36673301737825.549857393
 2288142.4344843737231.072119981
#Sta/Elev= 30
       0  160.32   31.98  159.94   56.25  158.73   85.28  158.72  149.79  155.84
   158.7  156.72   169.8  156.59  234.48  154.16  334.93  152.62  366.58  153.01
  441.17  151.15  467.01  152.53  500.08  152.09  529.89   153.5  578.57  152.86
  588.77   150.3  591.01  151.49  603.69  153.33  728.29  151.39  758.91  151.83
  781.16  153.43   814.4  154.18  875.76  156.47  895.55  156.12  920.79  154.48
  931.18  156.67  957.36  155.99  1003.9  156.89 1210.32  165.63    1288  167.51
#Mann= 4 ,-1 , 0
       0     .09       0  578.57     .05       0  603.69     .09       0
   814.4     .07       0
#XS Ineff= 2 , 0
       0     480     159               0
Permanent Ineff=
       F       F
Bank Sta=578.57,603.69
XS Rating Curve= 0 ,0
Exp/Cntr=0.3,0.1

Type RM Length L Ch R = 1 ,0       ,156.61,111.95,74.5
BEGIN DESCRIPTION:
24.73	164.59
28.5	164.5
29.96	164.43
47.56	163.78
51.09	163.79
77.33	163.41
80.29	163.31
83.88	163.24
END DESCRIPTION:
XS GIS Cut Line= 6
2287547.15617043738557.979615122 2287614.2870716738346.517276496
2287761.97505412738024.2889510992287855.95831572737789.330797002
2288127.83846532737393.2584802962288228.53481701 737242.21395281
#Sta/Elev= 30
       0  164.53  100.32  163.34  183.57   161.1  323.71  159.51  367.69  157.75
  397.44  157.71  430.08  156.67  471.62  156.84  535.67  155.07  559.59  155.82
  639.77  155.51  665.45  154.34  712.62  153.99  811.46  151.24  852.86  151.76
   884.5  151.06  894.32  150.53  903.52  150.53  905.08  151.23  921.83  150.95
  954.32  152.83  993.52  153.85 1003.04  155.53 1033.04  156.09 1154.18  156.45
    1173  155.91 1203.84  158.33 1218.21  158.43 1250.82  160.82 1491.32  168.01
#Mann= 4 ,-1 , 0
       0     .09       0   884.5     .05       0  905.08     .09       0
 1033.04     .07       0
Bank Sta=884.5,905.08
XS Rating Curve= 0 ,0
Exp/Cntr=0.3,0.1
Stream Node=Milltone        ,Creek           , 0 , 0 ,Upstream end
Stream Node=Milltone        ,Creek           , 0 , 1 ,Downstream end

Chan Stop Cuts=-1
Use User Specified Reach Order=0
User Specified Reach Order=Milltone        ,Creek