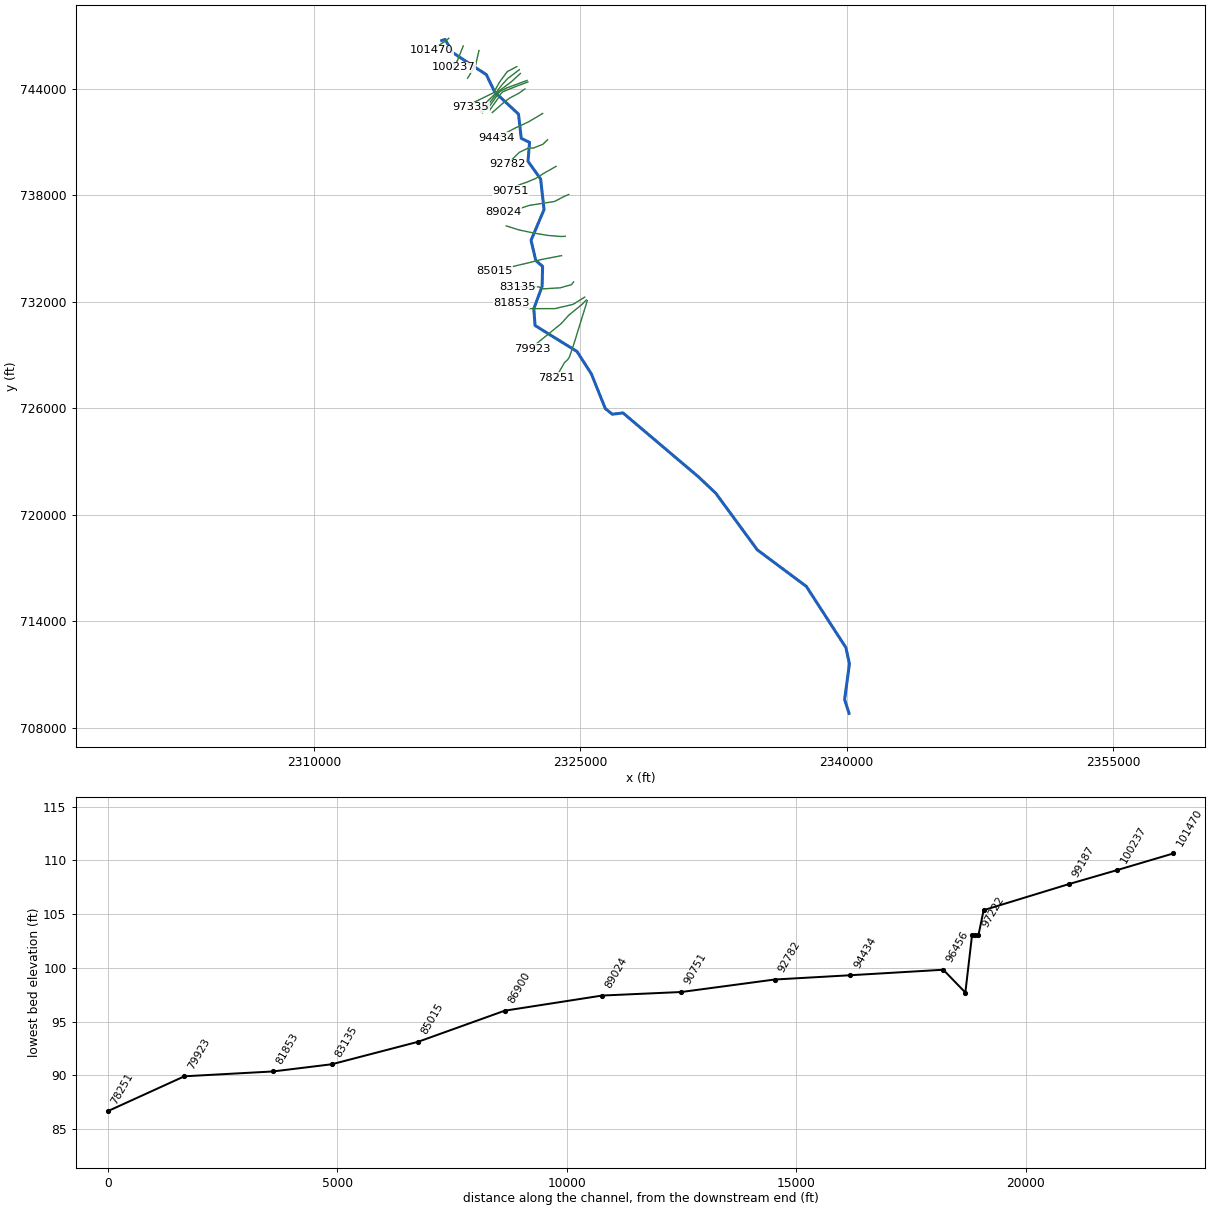
--- DTL_Toisnot_Swamp_Upstream.prj (project) ---

Proj Title=DTL_Toisnot_Swamp_Upstream
Current Plan=p02
Default Exp/Contr=0.3,0.1
English Units
Geom File=g01
Flow File=f01
Flow File=f02
Plan File=p02
Plan File=p03
Y Axis Title=Elevation
X Axis Title(PF)=Main Channel Distance
X Axis Title(XS)=Station
BEGIN DESCRIPTION:
END DESCRIPTION:
DSS Export Rating Curves= 0
DSS Export Rating Curve Sorted= 0
DSS Export Volume Flow Curves= 0
DXF Filename=..\backup\DTL_Toisnot_Swamp_Upstream.
DXF OffsetX= 0
DXF OffsetY= 0
DXF ScaleX= 1
DXF ScaleY= 10

--- DTL_Toisnot_Swamp_Upstream.p02 (plan) ---

Plan Title=DTL_Toisnot_Swamp_Upstream
Program Version=4.00
Short Identifier=Multiple
Geom File=g01
Flow File=f01
Subcritical Flow
K Sum by GR= 0
Std Step Tol= 0.01
Critical Tol= 0.01
Num of Std Step Trials= 20
Max Error Tol= 0.3
Flow Tol Ratio= 0.001
Split Flow NTrial= 30
Split Flow Tol= 0.02
Split Flow Ratio= 0.02
Log Output Level= 0
Friction Slope Method= 1
Unsteady Friction Slope Method= 2
Unsteady Bridges Friction Slope Method= 1
Parabolic Critical Depth
Global Vel Dist= 0 , 0 , 0
Global Log Level= 0
CheckData=True
Encroach Param=-1 ,10,10, 2
Encroach River=Toisnot Swamp
Encroach Reach=Upstream
Encroach Node=101470
       1   231.4  780.79
Encroach Node=100237
       1  342.29  971.67
Encroach Node=99187
       1  172.66 1561.24
Encroach Node=97335
       1    1530    2216
Encroach Node=97222
       1    1610    2013
Encroach Node=97146
       1    1500    1839
Encroach Node=97082
       1    1660    1950
Encroach Node=96937
       1    1605    1831
Encroach Node=96456
       1    1048    1365
Encroach Node=94434
       1    1300    1750
Encroach Node=92782
       1     950    1318
Encroach Node=90751
       1    1010    1760
Encroach Node=89024
       1    1335    2185
Encroach Node=86900
       1    1185    2095
Encroach Node=85015
       1     910    1820
Encroach Node=83135
       1    1360    2230
Encroach Node=81853
       1    2380    3250
Encroach Node=79923
       1    2270    3140
Encroach Node=78251
       1    2315    3150
Encroach Node=78136
       1    2335    3165
Encroach Node=77456
       1    1300    2060
Encroach Node=76870
       1    1340    1930
Encroach Node=76021
       1    1830    2740
Encroach Node=75931
       1    2000    2880
Encroach Node=75051
       1    2126    2832
Encroach Node=73893
       1    3092    3208
Encroach Node=73739
       1    3080    3180
Encroach Node=73030
       1    2500    3030
Encroach Node=71597
       1    2050    2841
Encroach Node=70449
       1    1080    2000
Encroach Node=70310
       1    1080    2000
Encroach Node=69434
       1    1350    2129
Encroach Node=68311
       1    1838    2048
Encroach Node=68151
       1    1935    2125
Encroach Node=67245
       1    1172    1725
Encroach Node=66158
       1     976    1900
Encroach Node=65169
       1     954    2470
Encroach Node=63929
       1     608    2487
Encroach Node=62829
       1 1338.02 2902.11
Encroach Node=61918
       1  1392.4 2805.24
Encroach Node=60953
       1    1335    3209
Encroach Node=58703
       1    1500    2800
Encroach Node=57775
       1     800    1700
Encroach Node=56704
       1    1038    1959
Encroach Node=55622
       1     905    1476
Encroach Node=54627
       1    1476    2358
Encroach Node=53745
       1     900    1700
Encroach Node=52970
       1    1353    1529
Encroach Node=52827
       1    1385    1562
Encroach Node=52086
       1     650    1450
Encroach Node=50870
       1     640    1734
Computation Interval=1HOUR
Output Interval=1HOUR
Run HTab= 0
Run UNet= 0
Run PostProcess= 0
Run WQNet= 0
UNET Theta= 1
UNET Theta Warmup= 1
UNET ZTol= 0.02
UNET ZSATol= 0.05
UNET MxIter= 20
UNET MaxInSteps= 0
UNET DtIC= 0
UNET DtMin= 0
UNET MaxCRTS= 20
UNET WFStab= 2
UNET SFStab= 1
UNET WFX= 1
UNET SFX= 1
UNET DSS MLevel= 4
UNET DZMax Abort= 100
UNET Convert EG Bridges=-1
UNET Use Existing IB Tables=-1
UNET Froude Reduction=False
UNET Froude Limit= 1
UNET Froude Power= 10
UNET Time Slicing=0,0, 5
Instantaneous Interval=1HOUR
DSS File=dss
Write IC File= 0
Echo Input=False
Echo Output=False
Write Detailed= 0
Detailed Automatic Start=False, 10
WQ ULTIMATE=-1
WQ Max Comp Step=1HOUR
WQ Output Interval=15MIN
WQ Output Selected Increments= 0
WQ Output face flow=0
WQ Output face velocity=0
WQ Output face area=0
WQ Output face dispersion=0
WQ Output cell volume=0
WQ Output cell surface area=0
WQ Output cell continuity=0
WQ Output face conc=0
WQ Output face dconc_dx=0
WQ Output face courant=0
WQ Output face peclet=0
WQ Output face adv mass=0
WQ Output face disp mass=0
WQ Output cell mass=0
WQ Output cell source sink temp=0
WQ Output cell source sink nsm=0
WQ Output MaxMinRange=-1
WQ Daily Max Min Mean=-1
WQ Daily Range=0
WQ Daily Time=0
WQ Create Restart=0
WQ Fixed Restart=0
WQ System Summary=False
Sorting and Armoring Iterations= 10
XS Update Threshold= 0.02
Hydraulics Update Threshold= 0.02
Energy Slope Method= 1
Volume Change Method= 0
XS Weighting Method= 0
Number of US Weighted Cross Sections= 1
Number of DS Weighted Cross Sections= 1
Upstream XS Weight=0.25
Main XS Weight=0.5
Downstream XS Weight=0.25
Number of DS XS's Weighted with US Boundary= 1
Upstream Boundary Weight= 1
Weight of XSs Associated with US Boundary= 0
Number of US XS's Weighted with DS Boundary= 1
Downstream Boundary Weight= 0.5
Weight of XSs Associated with DS Boundary= 0.5
Sediment Output Level= 4
Mass or Volume Output= 0
Output Increment Type= 1
Profile and TS Output Increment= 10
XS Output Flag= 0
XS Output Increment= 10
Disregard all LS=0
Disregard all Conn=0
Disregard all Breaches=0
Disregard all Pumps=0

--- DTL_Toisnot_Swamp_Upstream.p03 (plan) ---

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Plan Title=DTL_Toisnot_Swamp_Upstream_Future
Short Identifier=Future
Geom File=g01
Flow File=f02
Encroach Node=99188.5
       1     330  1736.6
Encroach Node=97335.5
       1    1130    2216
Encroach Node=97222.5
       4       1
Encroach Node=97146.5
Encroach Node=97082.5
       1    1206    2027
Encroach Node=96937.5
       1    1712    1831
Encroach Node=96456.5
Encroach Node=94434.5
       1    1300    2039
Encroach Node=92782.5
       1    1038    1332
Encroach Node=90751.5
       4       1
Encroach Node=89024.5
       4       1
Encroach Node=86900.5
       4       1
Encroach Node=85015.5
       4       1
Encroach Node=83135.5
       4       1
Encroach Node=81853.5
       1    2302    3400
Encroach Node=79923.5
       1    1668    3162
Encroach Node=78251.5
       4       1
Encroach Node=78136.5
       1    1958    3755
Encroach Node=77456.5
       1    1207    2359
Encroach Node=76870.5
       1    1221    2157
Encroach Node=76021.5
       1    1111    2808
Encroach Node=75931.5
       1    2047    3202
Encroach Node=75051.5
Encroach Node=73893.5
       1    2700    3500
Encroach Node=73739.5
Encroach Node=73030.5
       1    2275    3450
Encroach Node=71597.5
       1    1440    2910
Encroach Node=70449.5
       1    1000    2500
Encroach Node=70310.5
       1    1000    2500
Encroach Node=69434.5
       1    1506    2054
Encroach Node=68311.5
       1    1881    2008
Encroach Node=68151.5
       1    1965    2095
Encroach Node=67245.5
       1    1172    2000
Encroach Node=66158.5
       1     753    1900
Encroach Node=65169.5
Encroach Node=63929.5
Encroach Node=62829.5
       4       1
Encroach Node=61918.5
       4       1
Encroach Node=60953.5
Encroach Node=58703.5
Encroach Node=57775.5
Encroach Node=56704.5
Encroach Node=55622.5
Encroach Node=54627.5
Encroach Node=53745.5
Encroach Node=52970.5
Encroach Node=52827.5
Encroach Node=52086.5
       1     532    1850
Encroach Node=50870.5

--- DTL_Toisnot_Swamp_Upstream.f01 (steady flow) ---

Flow Title=DTL_Toisnot_Swamp_Upstream
Program Version=4.00
Number of Profiles= 6
Profile Names=100-yr,FW,10-yr,25-yr,50-yr,500-yr
River Rch & RM=Toisnot Swamp,Upstream        ,101470
    7132    7132    3655    4898    5975   10331
River Rch & RM=Toisnot Swamp,Upstream        ,97335
    7470    7470    3840    5140    6260   10810
River Rch & RM=Toisnot Swamp,Upstream        ,96456
    7540    7540    3880    5190    6320   10900
River Rch & RM=Toisnot Swamp,Upstream        ,94434
    7650    7650    3940    5270    6420   11060
River Rch & RM=Toisnot Swamp,Upstream        ,86900
    7740    7740    3980    5330    6490   11180
River Rch & RM=Toisnot Swamp,Upstream        ,83135
    8490    8490    4400    5870    7140   12240
River Rch & RM=Toisnot Swamp,Upstream        ,79923
    8600    8600    4460    5940    7230   12380
River Rch & RM=Toisnot Swamp,Upstream        ,77456
    8630    8630    4470    5960    7250   12420
River Rch & RM=Toisnot Swamp,Upstream        ,73893
    9100    9100    4730    6300    7650   13070
River Rch & RM=Toisnot Swamp,Upstream        ,69434
    9250    9250    4810    6410    7780   13290
River Rch & RM=Toisnot Swamp,Upstream        ,66158
    9340    9340    4860    6470    7860   13420
River Rch & RM=Toisnot Swamp,Upstream        ,61918
    9490    9490    4940    6580    7980   13620
River Rch & RM=Toisnot Swamp,Upstream        ,57775
    9880    9880    5160    6860    8320   14170
River Rch & RM=Toisnot Swamp,Upstream        ,56704
   10080   10080    5270    7000    8490   14440
River Rch & RM=Toisnot Swamp,Upstream        ,52086
   10280   10280    5390    7150    8670   14720
River Rch & RM=Toisnot Swamp,Upstream        ,50870
   10283   10283    5385    7146    8666   14721
Boundary for River Rch & Prof#=Toisnot Swamp,Upstream        , 1
Up Type= 0
Dn Type= 1
Dn Known WS=82.28
Boundary for River Rch & Prof#=Toisnot Swamp,Upstream        , 2
Up Type= 0
Dn Type= 1
Dn Known WS=83.16
Boundary for River Rch & Prof#=Toisnot Swamp,Upstream        , 3
Up Type= 0
Dn Type= 1
Dn Known WS=79.38
Boundary for River Rch & Prof#=Toisnot Swamp,Upstream        , 4
Up Type= 0
Dn Type= 1
Dn Known WS=80.76
Boundary for River Rch & Prof#=Toisnot Swamp,Upstream        , 5
Up Type= 0
Dn Type= 1
Dn Known WS=81.67
Boundary for River Rch & Prof#=Toisnot Swamp,Upstream        , 6
Up Type= 0
Dn Type= 1
Dn Known WS=83.4
DSS Import GetInterval= 0
DSS Import GetPeak= 0
DSS Import FillOption= 0

--- DTL_Toisnot_Swamp_Upstream.f02 (steady flow) ---

Flow Title=DTL_Toisnot_Swamp_Upstream_Future
Program Version=4.00
Number of Profiles= 3
Profile Names=100-yr-10%,100-yr-20%,100-yr-35%
River Rch & RM=Toisnot Swamp,Upstream        ,101470
    7273    9321   11389
River Rch & RM=Toisnot Swamp,Upstream        ,97335
    7600    9740   11900
River Rch & RM=Toisnot Swamp,Upstream        ,96456
    7670    9820   12000
River Rch & RM=Toisnot Swamp,Upstream        ,94434
    7780    9970   12200
River Rch & RM=Toisnot Swamp,Upstream        ,86900
    7860   10100   12300
River Rch & RM=Toisnot Swamp,Upstream        ,83135
    8590   11000   13400
River Rch & RM=Toisnot Swamp,Upstream        ,79923
    8690   11100   13600
River Rch & RM=Toisnot Swamp,Upstream        ,77456
    8710   11200   13600
River Rch & RM=Toisnot Swamp,Upstream        ,73893
    9160   11700   14300
River Rch & RM=Toisnot Swamp,Upstream        ,69434
    9310   11900   14600
River Rch & RM=Toisnot Swamp,Upstream        ,66158
    9400   12000   14700
River Rch & RM=Toisnot Swamp,Upstream        ,61918
    9530   12200   14900
River Rch & RM=Toisnot Swamp,Upstream        ,57775
    9910   12700   15500
River Rch & RM=Toisnot Swamp,Upstream        ,56704
   10100   12900   15800
River Rch & RM=Toisnot Swamp,Upstream        ,52086
   10300   13200   16100
River Rch & RM=Toisnot Swamp,Upstream        ,50870
   10291   13190   16116
Boundary for River Rch & Prof#=Toisnot Swamp,Upstream        , 1
Up Type= 0
Dn Type= 1
Dn Known WS=82.28
Boundary for River Rch & Prof#=Toisnot Swamp,Upstream        , 2
Up Type= 0
Dn Type= 1
Dn Known WS=83.07
Boundary for River Rch & Prof#=Toisnot Swamp,Upstream        , 3
Up Type= 0
Dn Type= 1
Dn Known WS=83.67
DSS Import GetInterval= 0
DSS Import GetPeak= 0
DSS Import FillOption= 0

--- DTL_Toisnot_Swamp_Upstream.g01 (geometry) ---

Geom Title=DTL_Toisnot_Swamp_Upstream
Program Version=4.00

River Reach=Toisnot Swamp   ,Upstream
Reach XY= 30
2317197.03595054746731.4934555592317384.45825458746795.752491623
2317827.57523094746043.0171331472319712.23356766744807.645563439
2320184.67992814743824.9333708732321519.94264999742586.301433146
2321678.06591421741216.9981352542322143.65093887740990.794102907
2322055.80479476 739924.560373442322767.35922773738928.603764027
  2322960.621052737203.5231856262322228.20300299735474.050415203
2322496.13401136734326.5589576072322878.26508389734001.527917162
2322850.81317988732871.6056115782322383.03193121731615.404521808
2322454.40703529730667.7631765012324818.56895861729199.632998452
2325624.55807973727942.3336686942326410.78195284 725984.46064195
2326806.08998537725667.1161295032327407.83667421725739.589345619
2331665.08493616 722129.108956562332630.29556151721214.410075307
2334969.20154877718023.3954148292337735.25992064715956.812755942
2339959.96597175712511.0440471322340159.81608403711593.050957859
2339888.59086765709584.6663150342340137.85448399708802.834761962

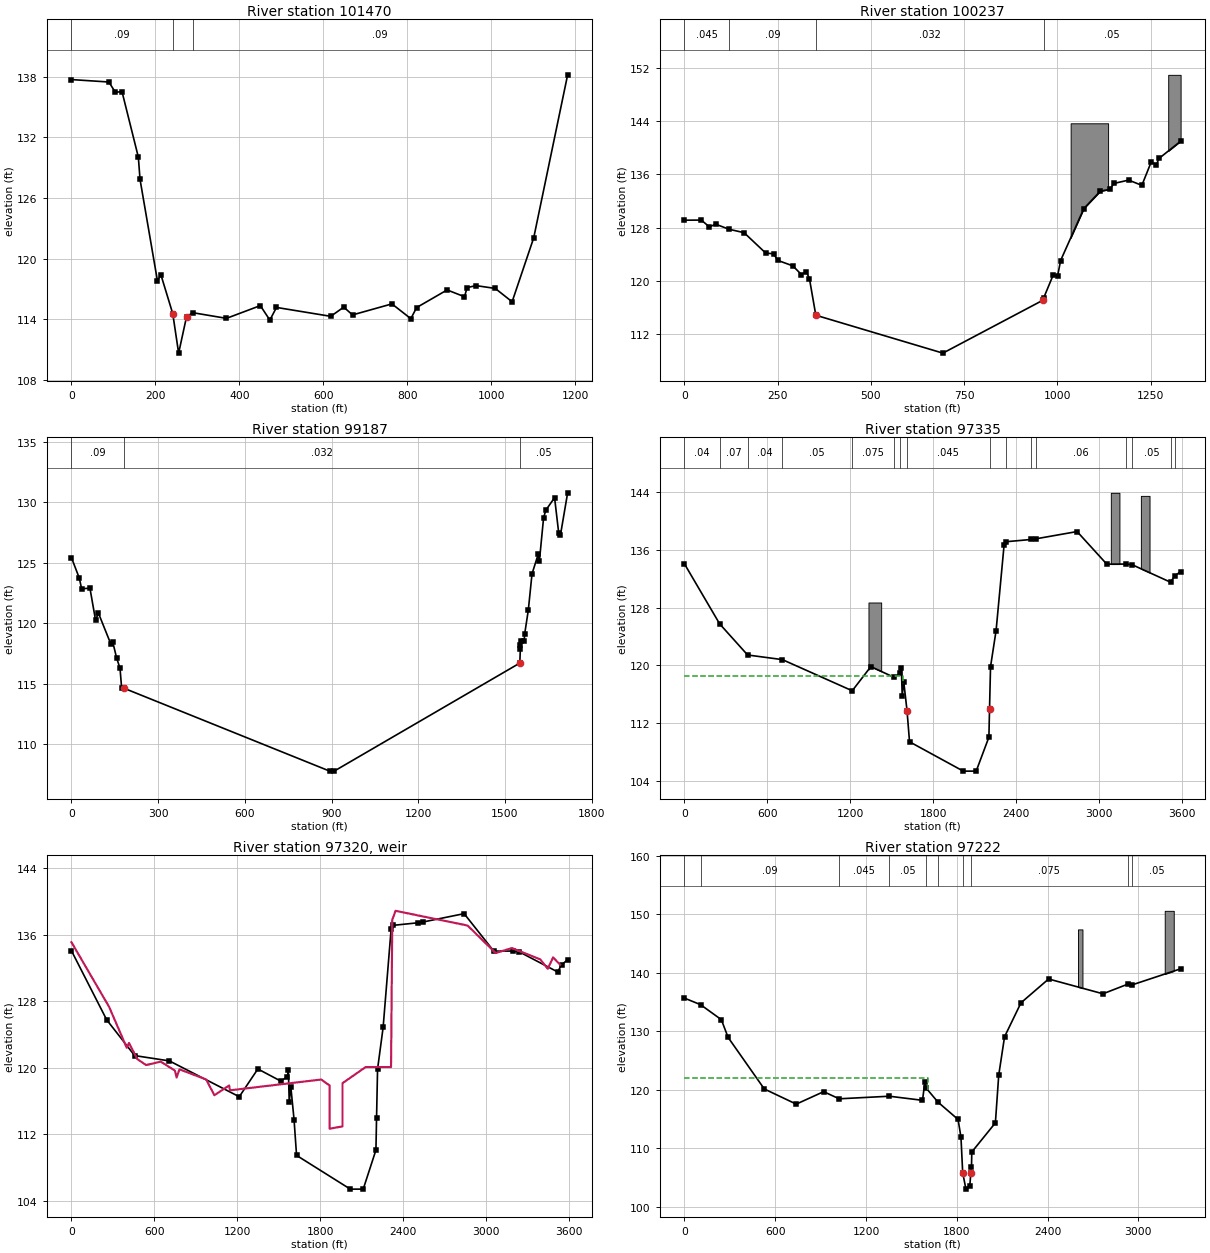
Type RM Length L Ch R = 1 ,101470  ,1006.66,1233.36,1420.12
BEGIN DESCRIPTION:
LDS tie in
END DESCRIPTION:
XS GIS Cut Line= 3
2317597.49999836746855.9999908062317378.75003417746686.499983117
2316629.74998523746177.250045016
#Sta/Elev= 30
       0  137.71   89.13  137.47  104.27  136.47  120.54   136.5  159.36  130.04
  163.37  127.84  204.85  117.81  213.14   118.4   241.4  114.55  255.39  110.65
  274.28  114.26  289.11  114.65  369.35  114.09  450.06  115.35  472.76  113.92
  488.59  115.17  617.87  114.29  648.87   115.2  669.81  114.43  763.69  115.52
  808.73  114.06  822.65  115.16  895.22   116.9  936.65  116.23  942.87  117.13
     964  117.33  1009.9  117.05 1050.15  115.73 1101.63  122.06 1182.46  138.18
#Mann= 3 ,-1 , 0
       0     .09       0   241.4     .05       0  289.11     .09       0
Bank Sta=241.4,274.28
XS Rating Curve= 0 ,0
Exp/Cntr=0.3,0.1

Type RM Length L Ch R = 1 ,100237  ,1019.38,1049.62,1149.87
XS GIS Cut Line= 3
2318411.36263706 746429.579064222318087.91285798745617.010107085
2317859.13130695745222.559157014
#Sta/Elev= 30
       0  129.11   45.26  129.13   66.83   128.1   83.73  128.51  119.49  127.75
  159.93  127.23  217.92  124.16  239.15  124.05  250.19  123.06  290.83  122.23
  313.83  120.91  326.96  121.37   335.3  120.27  352.29   114.8  693.07  109.09
  961.67  117.07  962.91  117.34  989.18   120.9 1000.46  120.65 1008.81  123.04
 1071.12  130.87 1115.16  133.48 1140.64  133.76 1151.87  134.65 1191.22  135.15
 1226.66  134.36 1252.24  137.95 1265.25  137.42 1272.63  138.41 1330.58  141.01
#Mann= 4 ,-1 , 0
       0    .045       0  119.49     .09       0  352.29    .032       0
  962.91     .05       0
#Block Obstruct= 2 ,-1
 1035.67 1136.13 143.706 1297.33 1330.58 151.006
Bank Sta=352.29,961.67
XS Rating Curve= 0 ,0
Exp/Cntr=0.3,0.1

Type RM Length L Ch R = 1 ,99187   ,2074.46,1852.2,1705.24
XS GIS Cut Line= 3
2319296.25003313746170.1875351222319102.25002025745340.499987721
2318649.75003089744603.687493116
#Sta/Elev= 30
       0  125.43   26.94  123.75   35.22  122.86   63.92  122.91   83.17  120.28
    93.4  120.84   135.9  118.31  142.68  118.47  156.23  117.14  168.02  116.28
  173.62  114.63  182.66114.6305  893.64  107.79  908.91  107.79 1551.24  116.72
 1553.04  117.85 1553.19   118.2 1555.04  118.53 1566.33  118.51 1567.84  119.09
 1580.64  121.09 1593.46  124.09 1614.74   125.7 1619.09  125.17 1633.47  128.72
 1641.13  129.35 1671.53  130.39 1685.65  127.51 1692.01  127.32 1716.73  130.79
#Mann= 3 ,-1 , 0
       0     .09       0  182.66    .032       0 1551.24     .05       0
Bank Sta=182.66,1551.24
XS Rating Curve= 0 ,0
Exp/Cntr=0.5,0.3

Type RM Length L Ch R = 1 ,97335   ,217,113,146
XS GIS Cut Line= 6
 2321426.1330966  745262.2917902  2320887.204849  744979.3544602
 2320442.5890447  744373.0601816 2320120.1441929   743792.191388
 2319041.3756009  743261.5206709 2318832.8044635  742974.2264747
#Sta/Elev= 30
       0  134.05  254.79125.7395  456.82  121.44  708.02   120.8 1213.29  116.49
 1347.89  119.83 1513.65  118.37 1560.66  118.89 1568.56  119.65 1574.77  115.83
 1586.05  117.71 1609.59  113.74 1627.72  109.43 2016.38  105.37 2109.76  105.37
 2201.68  110.07 2206.17  113.91 2213.51  119.82 2253.68  124.82 2311.89  136.72
 2324.31  137.11 2505.17  137.42 2543.57  137.52 2839.42  138.52 3054.07  134.01
 3192.02  134.02 3237.59  133.93 3515.35  131.51 3544.05  132.35 3588.04  132.99
#Mann= 16 ,-1 , 0
       0     .04       0  254.79     .07       0  456.82     .04       0
  708.02     .05       0 1213.29    .075       0 1513.65     .09       0
 1560.66     .05       0 1609.59    .045       0 2206.17     .05       0
 2324.31     .05       0 2505.17    .035       0 2543.57     .06       0
 3192.02    .035       0 3237.59     .05       0 3515.35    .035       0
 3544.05     .05       0
#XS Ineff= 2 , 0
       0    1584  118.47    2231       0     119
Permanent Ineff=
       F       F
#Block Obstruct= 3 ,-1
 1330.85 1422.66 128.703 3083.34 3145.63 143.878 3300.66 3363.34 143.456
Bank Sta=1609.59,2206.17
XS Rating Curve= 0 ,0
Exp/Cntr=0.5,0.3

Type RM Length L Ch R = 5 ,97320   ,,,
BEGIN DESCRIPTION:
Lake Wilson Dam
END DESCRIPTION:
IW Pilot Flow=0
#Inline Weir SE= 30
       0  135.08  272.29   127.3   399.9  122.37  416.13  122.96  475.91  121.02
  539.58   120.3  645.44  120.71   747.6  119.64  760.05  118.79  780.76  119.79
  974.49  118.56 1033.35  116.67 1139.95  117.84  1145.8  117.261806.279  118.56
1866.602  117.841866.603  112.641959.917  112.921959.918  118.122127.459  120.06
    2311  120.06 2319.83  137.77  2343.4  138.86 2864.66  137.09 3067.35  133.78
    3185  134.38 3389.99  133.02 3443.86  131.89 3483.09  133.26 3533.29  132.38
IW Dist,WD,Coef,Skew,MaxSub,Min_El,Is_Ogee,SpillHt,DesHd
6,80,2.6,0,0.98,, 0 ,,,0,0,

Type RM Length L Ch R = 1 ,97222   ,215,76,72.92
BEGIN DESCRIPTION:
Surveyed Section
END DESCRIPTION:
XS GIS Cut Line= 6
 2321567.6017616  745087.1401097 2320916.5605851  744592.2018161
 2320616.2545558  744267.3810089    2320173.7022      743692.162
 2319739.9542772  743280.0829731 2319378.2057556  742695.6460109
#Sta/Elev= 30
       0   135.7  106.58  134.58  243.79  132.02  288.67  128.98  527.78  120.17
  738.97  117.58  920.15  119.71 1022.48  118.49 1354.34  118.93 1573.36  118.23
 1589.41   121.4 1597.01  120.34 1675.38  117.931808.434  114.961827.565  111.94
1839.063  105.861860.397  103.051886.153  103.641892.711  105.811897.221   106.9
1899.238   109.4 2055.13  114.38 2077.19  122.54 2115.68  129.09 2224.29   134.9
 2406.95  138.97  2766.2  136.44 2930.36  138.09 2959.55  137.97 3279.28  140.71
#Mann= 10 ,-1 , 0
       0     .04       0  106.58     .09       0 1022.48    .045       0
 1354.34     .05       0 1597.01    .045       0 1675.38     .04       0
1839.063    .045       01892.711    .075       0 2930.36    .035       0
 2959.55     .05       0
#XS Ineff= 2 , 0
       0    1610     122               0
Permanent Ineff=
       F       F
#Block Obstruct= 2 ,-1
 2600.83 2630.61 147.445 3174.29 3233.89 150.621
Bank Sta=1839.063,1892.711
XS Rating Curve= 0 ,0
Exp/Cntr=0.5,0.3

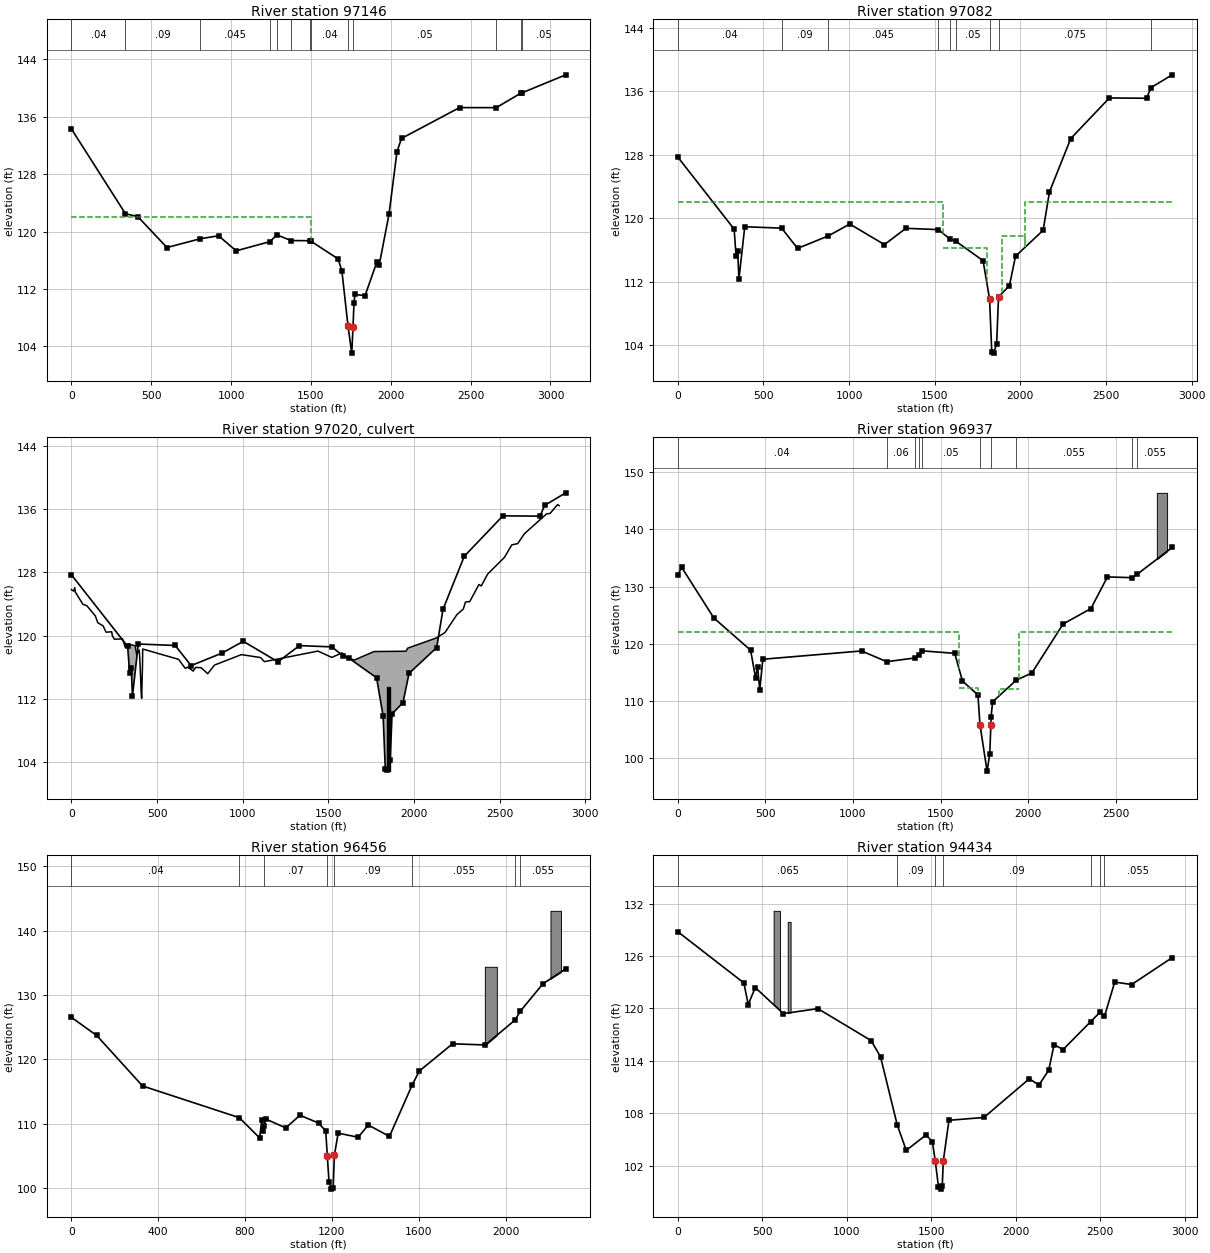
Type RM Length L Ch R = 1 ,97146   ,169.27,64.44,84.04
XS GIS Cut Line= 6
 2321626.5108968  744872.7961326  2321107.026014  744398.9416787
 2320394.4893165  743861.9066309  2320169.847205  743577.5939585
 2319629.3021242   742893.137525 2319499.4309035  742661.4753475
#Sta/Elev= 30
       0  134.32  338.34  122.49  415.99  122.08  598.37  117.77  806.37  118.99
  921.26  119.41 1032.19  117.31 1242.84  118.59  1287.1  119.53 1375.63118.7442
 1495.43  118.72 1498.22  118.68 1670.36  116.18 1693.91   114.5 1732.15  106.83
 1755.62  103.04 1763.44  106.62 1769.59  110.05  1775.9  111.23 1838.76  111.05
 1912.23  115.71 1927.78  115.36 1989.07  122.42  2038.9  131.15 2067.29  132.99
 2430.73  137.29 2660.26  137.28  2813.8  139.29 2818.75139.3173 3095.49  141.86
#Mann= 13 ,-1 , 0
       0     .04       0  338.34     .09       0  806.37    .045       0
 1242.84     .09       0  1287.1    .045       0 1375.63     .09       0
 1495.43    .045       0 1498.22     .04       0 1732.15    .045       0
 1763.44     .05       0 2660.26     .05       0  2813.8    .035       0
 2818.75     .05       0
#XS Ineff= 2 , 0
       0    1500     122               0
Permanent Ineff=
       F       F
Bank Sta=1732.15,1763.44
XS Rating Curve= 0 ,0
Exp/Cntr=0.5,0.3

Type RM Length L Ch R = 1 ,97082   ,125.53,144.84,133.72
BEGIN DESCRIPTION:
Surveyed Section
END DESCRIPTION:
XS GIS Cut Line= 6
 2321999.3478706  744482.5728627 2320851.4618004  744055.8994057
 2320479.3447023  743866.2628077     2320363.554     743723.0144
    2320312.4894     743628.4974 2319761.9032983  742854.2719648
#Sta/Elev= 30
       0  127.69  328.59  118.63  340.06  115.25  349.19   115.9  356.67  112.37
  390.68  118.93  606.12  118.75  699.03   116.2  878.88  117.78 1003.81  119.27
 1206.21  116.68  1331.6  118.73  1520.5  118.57 1588.04   117.4 1621.52  117.13
1782.015  114.661820.063  109.841832.827  103.171844.028  103.021861.435  104.22
1872.368  110.091936.063  111.52 1971.55  115.22 2132.94  118.48  2169.7  123.31
 2294.09  130.03 2519.58  135.14 2736.56   135.1 2762.77  136.45  2886.3  138.05
#Mann= 9 ,-1 , 0
       0     .04       0  606.12     .09       0  878.88    .045       0
  1520.5     .09       0 1588.04    .045       0 1621.52     .05       0
1820.063    .045       01872.368    .075       0 2762.77     .05       0
#XS Ineff= 4 ,-1
       0    1550     122    1550 1804.89   116.2 1895.29    2027   117.8
    2027    2883     122
Permanent Ineff=
       F       F       F       F
Bank Sta=1820.063,1872.368
XS Rating Curve= 0 ,0
Exp/Cntr=0.5,0.3

Type RM Length L Ch R = 2 ,97020   ,,,
BEGIN DESCRIPTION:
Lake Wilson Dr
END DESCRIPTION:
Bridge Culvert--1,0,-1,-1, 0
Deck Dist Width WeirC Skew NumUp NumDn MinLoCord MaxHiCord MaxSubmerge Is_Ogee
43,25,2.6,0, 60, 60, , , 0.95, 0, 1,1,,
       0   13.37   19.28   23.21   67.17   90.62  139.45  154.26  185.02  202.34
  235.42     239  251.08  298.39  314.92  330.97  372.63  381.22  396.31  400.91
  407.49  410.15  415.16  416.33  626.11  664.96  679.87  711.18  726.07  757.69
  796.06  835.58  992.58 1104.34 1126.88 1439.78 1520.09 1580.49 1612.981654.244
1767.244 1953.96 1963.74 2131.21 2181.23 2250.67 2288.64 2301.07 2325.67 2379.64
 2393.12 2430.86 2528.22 2571.56 2605.93 2645.21 2775.27  2794.8 2838.62 2847.85
  125.81  125.62  126.07  125.49  123.96  123.77   122.5  121.62  121.23  120.43
  120.48  119.98  119.54  119.58  118.49  118.93  118.71  117.59  118.17  116.37
  112.87  112.06  116.07   118.3  116.99  115.85  116.01  115.51  115.98  115.93
  115.18  116.27  117.59  117.22   116.7  118.04  117.24  117.81  117.08  116.93
  117.98  118.02  118.41   119.7  120.38  122.64  123.37  124.24  124.29  126.46
  126.27  127.79  129.88  131.47  131.63  132.88   135.4  135.44  136.56  136.43
                                                                                
                                                                                
                                                                                
                                                                                
                                                                                
                                                                                
       0   13.37   19.28   23.21   67.17   90.62  139.45  154.26  185.02  202.34
  235.42     239  251.08  298.39  314.92  330.97  372.63  381.22  396.31  400.91
  407.49  410.15  415.16  416.33  626.11  664.96  679.87  711.18  726.07  757.69
  796.06  835.58  992.58 1104.34 1126.88 1439.78 1520.09 1580.49 1612.981654.244
1767.244 1953.96 1963.74 2131.21 2181.23 2250.67 2288.64 2301.07 2325.67 2379.64
 2393.12 2430.86 2528.22 2571.56 2605.93 2645.21 2775.27  2794.8 2838.62 2847.85
  125.81  125.62  126.07  125.49  123.96  123.77   122.5  121.62  121.23  120.43
  120.48  119.98  119.54  119.58  118.49  118.93  118.71  117.59  118.17  116.37
  112.87  112.06  116.07   118.3  116.99  115.85  116.01  115.51  115.98  115.93
  115.18  116.27  117.59  117.22   116.7  118.04  117.24  117.81  117.08  116.93
  117.98  118.02  118.41   119.7  120.38  122.64  123.37  124.24  124.29  126.46
  126.27  127.79  129.88  131.47  131.63  132.88   135.4  135.44  136.56  136.43
                                                                                
                                                                                
                                                                                
                                                                                
                                                                                
                                                                                
BR Coef=-1 , 1 , 0 ,1.25, 0 ,,,0.8,0,2,0,
WSPro=,,,, 1 ,,,, 0 ,,,, 0 ,,,,-1 ,-1 ,-1 , 0 , 0 , 0 , 0 , 0
Multiple Barrel Culv=2,10.6,10,50,0.011,0.4,1,8,1,102.8586,101.5771, 2,Culvert #1  , 0 ,33
 1845.38 1761.02 1856.88 1772.52
Culvert Bottom n=0.011
BC Design=,, 0 ,, 0 ,,,,,,
BC Use User HTab Curves=0
BC User HTab FreeFlow(D)= 0

Type RM Length L Ch R = 1 ,96937   ,453.58,481.11,398.54
BEGIN DESCRIPTION:
Surveyed Section
END DESCRIPTION:
XS GIS Cut Line= 6
 2322048.1336426  744395.8426014 2321384.5911045  744145.3506313
 2320640.3569082  743844.7945136    2320528.1547     743736.1343
    2320438.8739     743570.5666 2319880.4280119  742784.0350975
#Sta/Elev= 30
       0     132    21.7  133.36  205.39   124.5  415.45  118.86  443.57  114.03
  455.29  115.92  467.63  111.91  485.11  117.28 1048.86  118.73 1192.37  116.85
 1356.62  117.52 1377.22  118.01 1394.15  118.75 1580.72  118.31 1624.69  113.48
1713.174  111.041724.812  105.841765.408   97.711780.665  100.721787.177  105.82
1788.021  107.191797.142  109.83 1932.34  113.63 2020.66  114.86 2199.52  123.45
 2357.89  126.13 2452.49  131.68 2592.44  131.55 2620.95  132.11 2822.17  136.83
#Mann= 10 ,-1 , 0
       0     .04       0 1192.37     .06       0 1356.62    .045       0
 1377.22     .06       0 1394.15     .05       01724.812    .045       0
1788.021     .09       0 1932.34    .055       0 2592.44    .035       0
 2620.95    .055       0
#XS Ineff= 4 ,-1
       0    1605     122    1605 1712.78  112.18 1831.36    1945     112
    1945    2822     122
Permanent Ineff=
       F       F       F       F
#Block Obstruct= 1 ,-1
 2734.51 2793.18 146.388
Bank Sta=1724.812,1787.177
XS Rating Curve= 0 ,0
Exp/Cntr=0.5,0.3

Type RM Length L Ch R = 1 ,96456   ,1768.52,2021.78,1595.45
XS GIS Cut Line= 5
  2321884.222107  744002.5470114 2321539.2981591  743761.4635493
 2321032.6520502  743493.2391387 2320744.5591647  743284.6201527
 2320045.1294621  742675.4362016
#Sta/Elev= 30
       0  126.52  116.77   123.7  327.85  115.86   773.6  110.93  867.26  107.79
  877.27  110.57  883.21  108.93  887.92  109.64  895.07  110.72   987.4  109.35
 1053.14   111.3 1138.66   110.1 1171.81  108.87 1179.07  104.93    1187   100.9
 1197.95   99.83 1205.91   99.98 1211.67  105.12 1229.07  108.53  1321.2  107.89
 1367.83  109.79 1465.24  108.02 1569.98  116.01 1602.86  118.18 1755.81  122.41
  1907.1  122.23 2043.66   126.1 2068.48  127.49 2172.03  131.73 2277.31  134.05
#Mann= 8 ,-1 , 0
       0     .04       0   773.6     .09       0  887.92     .07       0
 1179.07    .045       0 1211.67     .09       0 1569.98    .055       0
 2043.66    .035       0 2068.48    .055       0
#XS Ineff= 2 , 0
       0    1048            1460       0
Permanent Ineff=
       F       F
#Block Obstruct= 2 ,-1
 1904.65 1960.02 134.376 2207.08 2255.48 143.071
Bank Sta=1179.07,1211.67
XS Rating Curve= 0 ,0
Exp/Cntr=0.3,0.1

Type RM Length L Ch R = 1 ,94434   ,1493.74,1652.61,1492.72
XS GIS Cut Line= 5
 2322881.2393651  742621.5433769 2322602.2615642  742450.1442085
 2322055.8785055  742132.2486108 2321380.3503602  741824.2872504
 2320301.1203797  741247.2763455
#Sta/Elev= 30
       0  128.78  390.84  122.92  416.44  120.45  458.17  122.39  624.69  119.41
  828.81  119.98 1144.13  116.32  1199.7  114.46 1298.16  106.69  1351.7  103.76
 1469.68  105.53 1506.55  104.73 1523.79  102.51 1542.52   99.59 1555.26   99.32
    1565   99.69    1571  102.53 1604.65   107.2 1811.49  107.52    2080  111.95
 2137.16  111.24 2194.75  112.92 2226.91  115.87 2279.76  115.29 2442.72  118.48
 2498.61  119.56 2524.65  119.08  2585.7  123.02 2686.09  122.74 2925.77  125.82
#Mann= 7 ,-1 , 0
       0    .065       0 1298.16     .09       0 1523.79     .05       0
    1571     .09       0 2442.72    .055       0 2498.61    .035       0
 2524.65    .055       0
#Block Obstruct= 2 ,-1
  566.91  604.13 131.175  650.34   667.3 129.908
Bank Sta=1523.79,1571
XS Rating Curve= 0 ,0
Exp/Cntr=0.3,0.1

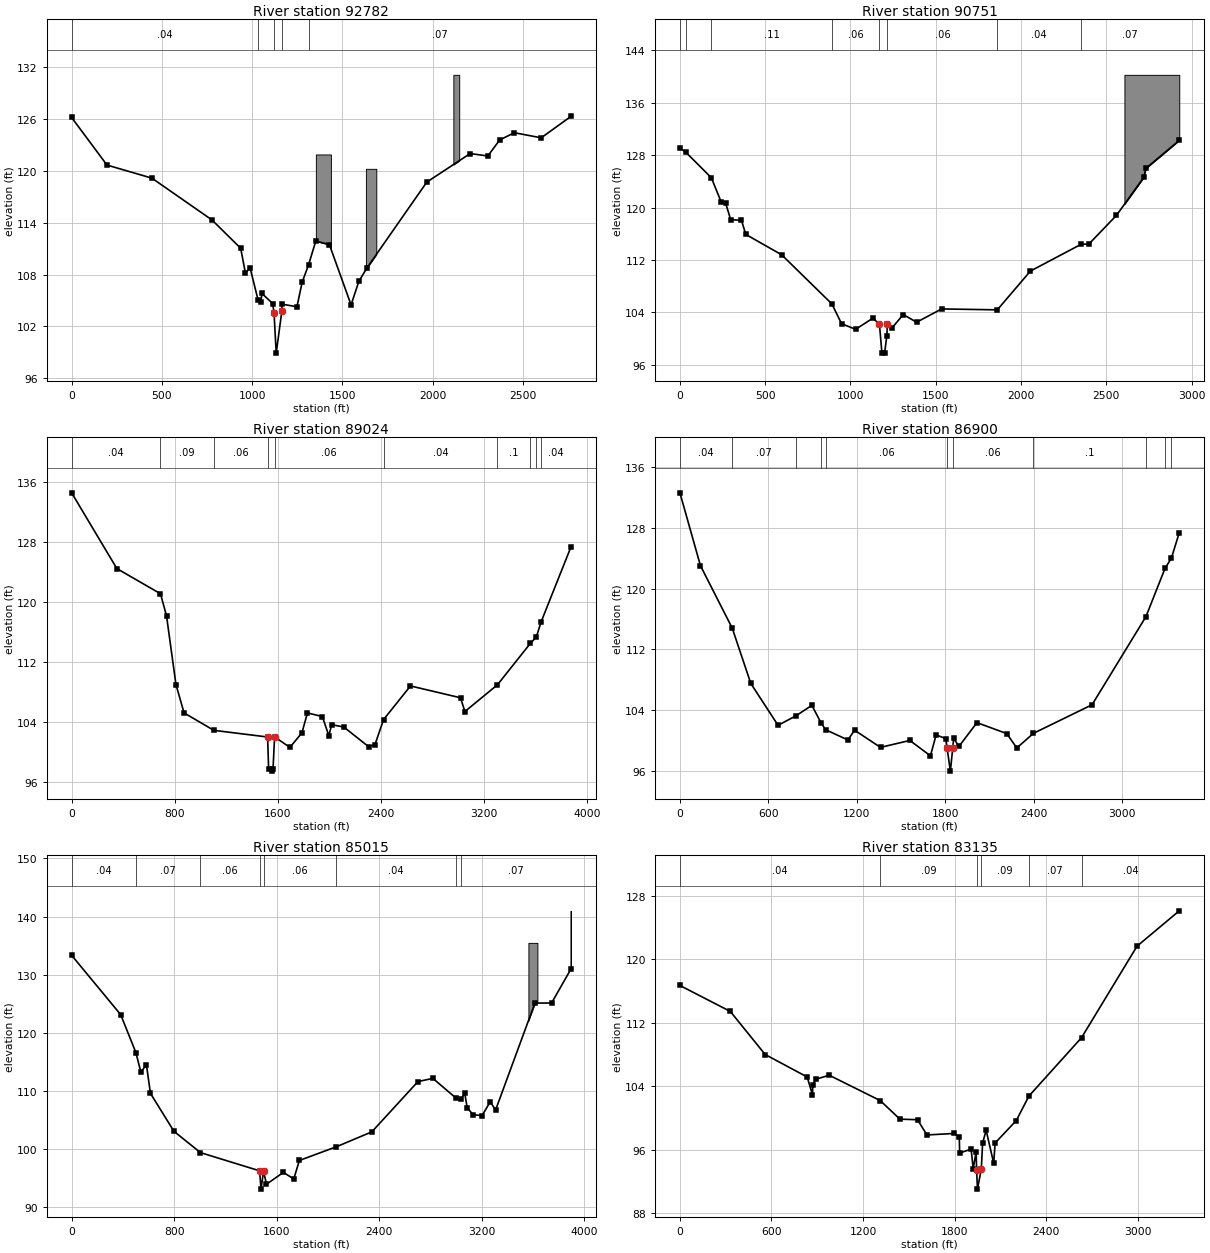
Type RM Length L Ch R = 1 ,92782   ,1639.43,2030.53,1701.64
BEGIN DESCRIPTION:
Surveyed Section
END DESCRIPTION:
XS GIS Cut Line= 6
 2323159.3034186  741139.7894541 2322890.9497421  740882.1699246
 2322372.1326341  740674.6430814    2322063.2563     740667.3871
 2321570.6496535   740431.335748 2320878.1241711  739753.4775647
#Sta/Elev= 30
       0  126.16  195.85  120.66  444.55  119.15  777.31  114.32  936.72  111.04
  963.26  108.13  988.24  108.81 1032.65  105.09 1048.37   104.81054.133  105.82
1113.952  104.651121.435  103.55  1133.5   98.921164.455  103.751165.738  104.58
 1248.44  104.28 1277.04  107.11 1312.78  109.13 1352.74  111.88 1428.18  111.46
 1548.23   104.5 1591.36  107.21  1635.9  108.76 1967.81  118.69 2208.11  121.99
 2305.95  121.71  2371.6  123.56 2452.78   124.4 2601.71  123.81 2766.67  126.29
#Mann= 5 ,-1 , 0
       0     .04       0 1032.65     .09       01121.435     .05       0
1164.455     .09       0 1312.78     .07       0
#Block Obstruct= 3 ,-1
 1353.16 1436.51 121.888 1630.46 1687.95 120.227 2114.98 2147.47 131.092
Bank Sta=1121.435,1164.455
XS Rating Curve= 0 ,0
Exp/Cntr=0.3,0.1

Type RM Length L Ch R = 1 ,90751   ,1731.64,1727.03,1380.62
XS GIS Cut Line= 6
 2323635.7389118  739637.2282057 2322969.8283491  739261.2539934
  2322483.050715  738953.2926331 2321986.3388435  738744.6736471
 2321549.2323965  738595.6600856 2321062.3565294  738269.6977774
#Sta/Elev= 30
       0  129.09   35.42  128.42  184.44  124.54  241.27  120.88  268.18  120.66
   297.8  118.13  360.85  118.05  386.16  115.89  596.45  112.78  890.87  105.28
  947.69  102.25 1030.21   101.4 1131.02  103.09 1169.78   102.2 1184.29   97.76
 1200.37   97.82 1213.12  100.43 1216.71  102.27  1242.3  101.57 1309.37  103.65
 1387.61  102.48 1534.67  104.51 1860.78  104.37 2054.85  110.29 2351.16  114.37
 2398.46  114.44 2559.45   118.8  2720.4  124.64 2731.22  125.96  2927.6  130.26
#Mann= 8 ,-1 , 0
       0     .04       0   35.42     .09       0  184.44     .11       0
  890.87     .06       0 1169.78     .05       0 1216.71     .06       0
 1860.78     .04       0 2351.16     .07       0
#Block Obstruct= 1 ,-1
 2606.05  2927.6 140.264
Bank Sta=1169.78,1216.71
XS Rating Curve= 0 ,0
Exp/Cntr=0.3,0.1

Type RM Length L Ch R = 1 ,89024   ,1865.23,2123.92,1671.4
XS GIS Cut Line= 6
 2324349.8188399  738054.1264784 2324123.4296951  737957.9510496
 2323543.6322668  737658.0558281 2322124.1282181  737438.1326656
 2321034.5089131  737068.2618923 2320644.6871375  737057.1092203
#Sta/Elev= 30
       0  134.61  350.99  124.49  689.51  121.13  736.59  118.17  809.64     109
  872.66  105.21 1103.45  102.88 1520.87  101.99 1529.11   97.73  1556.5   97.43
 1563.14   97.71 1575.35  102.01 1694.02   100.6 1787.39  102.54 1830.35  105.21
 1946.06  104.72 1996.11  102.17 2018.71  103.64 2112.64  103.32 2304.89   100.7
 2354.28  100.96 2421.24  104.32 2630.08  108.81 3018.37  107.23 3052.36  105.39
 3305.32  108.97 3561.12  114.51 3606.86  115.35 3644.45  117.39 3875.84  127.39
#Mann= 10 ,-1 , 0
       0     .04       0  689.51     .09       0 1103.45     .06       0
 1520.87     .05       0 1575.35     .06       0 2421.24     .04       0
 3305.32      .1       0 3561.12     .04       0 3606.86    .035       0
 3644.45     .04       0
Bank Sta=1520.87,1575.35
XS Rating Curve= 0 ,0
Exp/Cntr=0.3,0.1

Type RM Length L Ch R = 1 ,86900   ,1403.7,1885.02,2005.76
XS GIS Cut Line= 6
 2324154.4573501   735696.315395 2323933.4493798  735684.9285185
 2323178.4473351  735744.5339431 2322423.4452904  735873.6790297
  2321559.166634  736052.4953035 2320833.3120242  736282.3998643
#Sta/Elev= 30
       0  132.58  139.32  123.01  355.12   114.8  480.93  107.54  665.94  102.04
  787.85  103.29  895.46  104.66  957.28  102.37  988.79  101.46 1140.38  100.11
 1184.79   101.4 1361.28   99.14 1560.27  100.05 1700.05   98.03 1738.72  100.78
  1804.2  100.29 1813.37   99.01 1835.31   96.02 1851.73   99.11 1857.41  100.35
 1893.16   99.26 2015.85  102.39 2218.17  100.95 2286.27   99.06 2398.45  100.98
 2796.86  104.74 3162.58  116.32  3292.7  122.69 3334.72  123.97  3388.6  127.34
#Mann= 11 ,-1 , 0
       0     .04       0  355.12     .07       0  787.85     .04       0
  957.28     .07       0  988.79     .06       0 1813.37     .05       0
 1851.73     .06       0 2398.45      .1       0 3162.58     .04       0
  3292.7    .035       0 3334.72     .04       0
Bank Sta=1813.37,1851.73
XS Rating Curve= 0 ,0
Exp/Cntr=0.3,0.1

Type RM Length L Ch R = 1 ,85015   ,1725.18,1880.23,1539.58
XS GIS Cut Line= 6
 2323945.6226542  734604.9856936 2322763.9046907  734379.2014058
 2322114.1317107  734209.2607802 2321434.3692085  734049.3166621
 2320864.5682876  733899.3690513 2320143.5074213  733766.5420496
#Sta/Elev= 30
       0  133.35  382.42  123.15  501.35  116.61  540.36  113.24  583.25  114.55
  615.03  109.59  798.44  103.07 1005.03   99.41 1466.21   96.28 1477.52   93.13
 1497.06   96.22    1520   93.97 1651.85   96.01  1732.9   94.88 1776.67   98.06
 2064.21  100.41 2341.94  102.98 2701.78  111.63 2818.14  112.18 2996.78  108.82
 3036.91  108.59 3066.71  109.62  3085.6  107.15 3130.35  105.95 3201.07  105.76
 3265.49  108.15 3307.37  106.74 3614.12  125.13 3744.12  125.14 3895.47     131
#Mann= 8 ,-1 , 0
       0     .04       0  501.35     .07       0 1005.03     .06       0
 1466.21     .05       0 1497.06     .06       0 2064.21     .04       0
 2996.78    .035       0 3036.91     .07       0
#XS Ineff= 2 , 0
       0                    2800       0
Permanent Ineff=
       F       F
#Block Obstruct= 2 ,-1
 3563.35 3633.56 135.487  3891.2 3895.47 140.998
Bank Sta=1466.21,1497.06
XS Rating Curve= 0 ,0
Exp/Cntr=0.3,0.1

Type RM Length L Ch R = 1 ,83135   ,1138.19,1282.47,1375.14
BEGIN DESCRIPTION:
Surveyed Section
END DESCRIPTION:
XS GIS Cut Line= 6
 2324622.1382496  733125.5600006 2324501.7696627  732969.0808377
 2323867.8284387  732792.5402436    2322892.7346     732732.9709
    2322652.2478     732847.5676 2321481.7947695  732844.0828002
#Sta/Elev= 30
       0  116.68  330.34  113.41  558.52  107.99  833.75  105.16  867.99  102.95
  871.24  104.18  889.61  104.87  978.16  105.38 1312.18  102.19  1441.4   99.85
  1556.9   99.78  1618.2   97.86 1798.44   98.05 1830.36   97.551832.692   95.58
1907.728   96.081921.384   93.621940.598   95.72 1943.73   93.491949.342   91.04
 1974.54   93.561983.037   96.832006.145   98.462055.769    94.32064.991   96.85
 2204.03   99.68  2286.1  102.75 2631.24  110.11 2994.88  121.63 3271.46  126.08
#Mann= 6 ,-1 , 0
       0     .04       0 1312.18     .09       0 1943.73     .05       0
 1974.54     .09       0  2286.1     .07       0 2631.24     .04       0
Bank Sta=1943.73,1974.54
XS Rating Curve= 0 ,0
Exp/Cntr=0.3,0.1

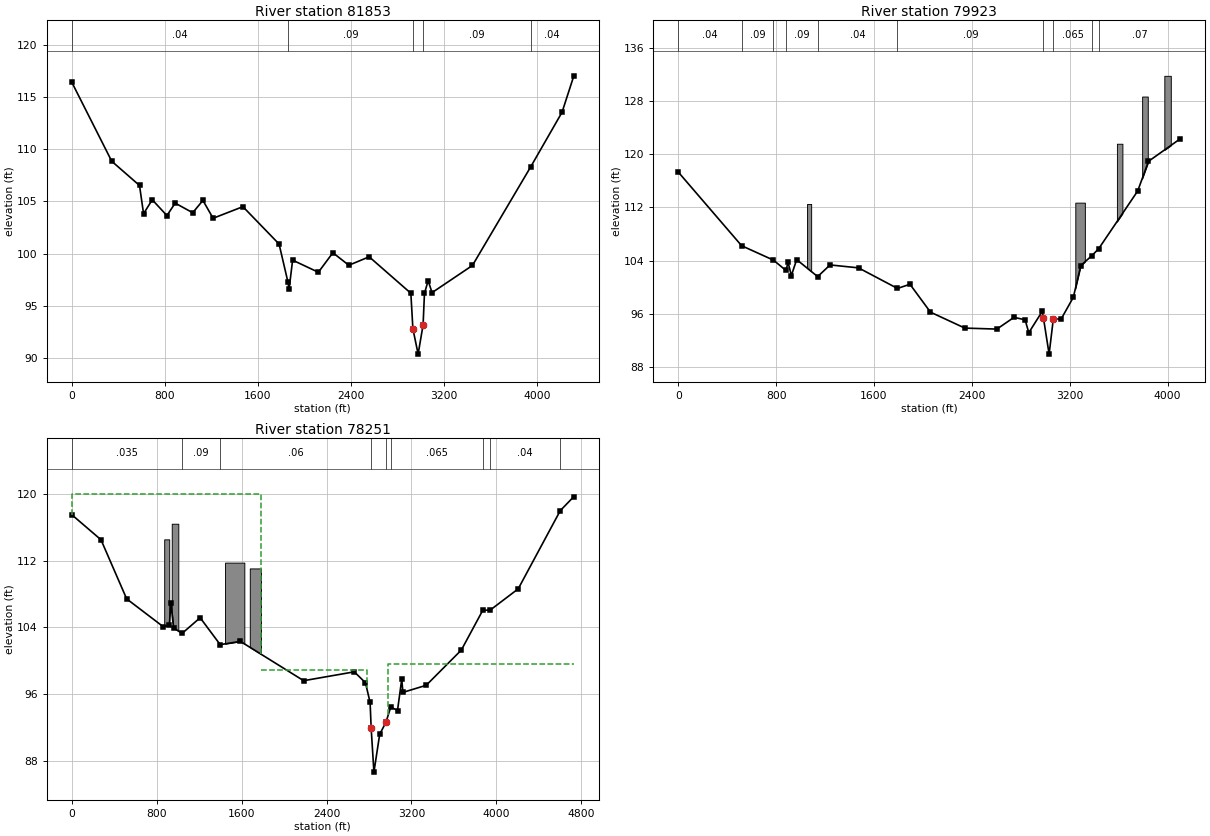
Type RM Length L Ch R = 1 ,81853   ,1279.74,1929.9,2132.97
XS GIS Cut Line= 5
 2325252.5236546  732267.3844196 2324593.2655422  731860.0815448
 2323573.6217889  731620.1653675 2322134.1247255  731620.1653675
 2321122.9859573  731923.8176617
#Sta/Elev= 30
       0  116.41  343.74  108.84  582.62  106.52  617.38  103.82  692.12  105.15
  818.25  103.64  889.29  104.83 1040.11  103.91 1127.76  105.09 1215.45  103.38
 1471.66  104.49 1782.84  100.91 1859.19   97.26 1868.59   96.57 1899.18   99.37
 2120.54   98.21 2245.43  100.08 2382.72   98.88 2557.44   99.69 2915.99    96.2
 2933.51    92.8 2978.58   90.37 3021.23   93.17 3033.03   96.19 3064.63    97.4
 3098.37   96.26 3445.53   98.86 3945.91  108.29 4216.09  113.53 4317.67  117.02
#Mann= 5 ,-1 , 0
       0     .04       0 1859.19     .09       0 2933.51     .05       0
 3021.23     .09       0 3945.91     .04       0
Bank Sta=2933.51,3021.23
XS Rating Curve= 0 ,0
Exp/Cntr=0.3,0.1

Type RM Length L Ch R = 1 ,79923   ,1404.84,1671.93,1984.35
XS GIS Cut Line= 6
 2325340.0994949  732105.7059453 2325113.0839262  731870.0780521
 2324343.3528576  731240.2980869 2323933.4960548  730780.4587472
  2322434.019947  729560.8848462 2322322.1013082  729357.1718825
#Sta/Elev= 30
       0  117.34  518.29  106.24  778.46  104.07  880.23  102.52   897.8  103.73
  924.61  101.75  968.02  104.15 1139.58  101.59 1240.86  103.35 1473.38  102.91
 1792.06   99.81 1893.93  100.44 2061.54   96.24 2342.55   93.84 2604.38   93.69
  2744.5   95.46 2834.78   95.09 2865.28   93.15 2975.12   96.36  2985.4   95.32
 3031.27   89.92 3065.49   95.18  3130.4   95.23 3229.34   98.48 3290.04  103.26
 3379.34  104.72 3436.38  105.79 3755.26  114.48 3843.57  118.95 4103.63  122.35
#Mann= 10 ,-1 , 0
       0     .04       0  518.29     .09       0  778.46     .04       0
  880.23     .09       0 1139.58     .04       0 1792.06     .09       0
  2985.4     .05       0 3065.49    .065       0 3379.34    .035       0
 3436.38     .07       0
#XS Ineff= 2 , 0
       0     800                       0
Permanent Ineff=
       F       F
#Block Obstruct= 5 ,-1
 1052.89 1086.43 112.532 3245.34 3323.48 112.729 3585.48 3630.41 121.599
 3791.61 3837.65 128.704 3972.97 4025.88 131.823
Bank Sta=2985.4,3065.49
XS Rating Curve= 0 ,0
Exp/Cntr=0.5,0.3

Type RM Length L Ch R = 1 ,78251   ,99.67,114.7,133.38
BEGIN DESCRIPTION:
Surveyed Section
END DESCRIPTION:
XS GIS Cut Line= 6
 2325394.9227942  732066.1951583 2324659.6610138   729690.404022
 2324396.5530633  728913.7600718 2324291.9438781  728739.4114299
 2324114.4252609  728580.9126645  2323627.147682  727731.9231263
#Sta/Elev= 30
       0   117.5  275.18   114.5  517.08  107.42  861.34  104.09  919.37  104.26
  933.66  106.97  958.34  103.96 1038.59  103.28 1209.35  105.16 1398.03  101.94
 1588.62  102.33 2184.35   97.62 2661.14   98.682766.457   97.382810.292   95.01
2820.372    91.92846.212   86.672900.465    91.22959.329   92.643004.728   94.47
3068.325   94.05 3108.23   97.79 3119.25   96.22  3338.8   97.07 3669.56  101.29
 3871.53  106.05    3942  106.08 4205.32  108.62 4601.76  117.99 4729.46  119.67
#Mann= 9 ,-1 , 0
       0    .035       0 1038.59     .09       0 1398.03     .06       0
2820.372     .05       02959.329     .09       03004.728    .065       0
 3871.53    .035       0    3942     .04       0 4601.76     .07       0
#XS Ineff= 3 ,-1
       0 1782.89     120 1782.89    2778   98.85 2982.22 4729.46    99.6
Permanent Ineff=
       F       F       F
#Block Obstruct= 4 ,-1
  870.58  917.97 114.548  941.75 1003.64 116.419 1443.82 1625.55 111.762
 1676.82 1782.89 111.067
Bank Sta=2820.372,2959.329
XS Rating Curve= 0 ,0
Exp/Cntr=0.5,0.3