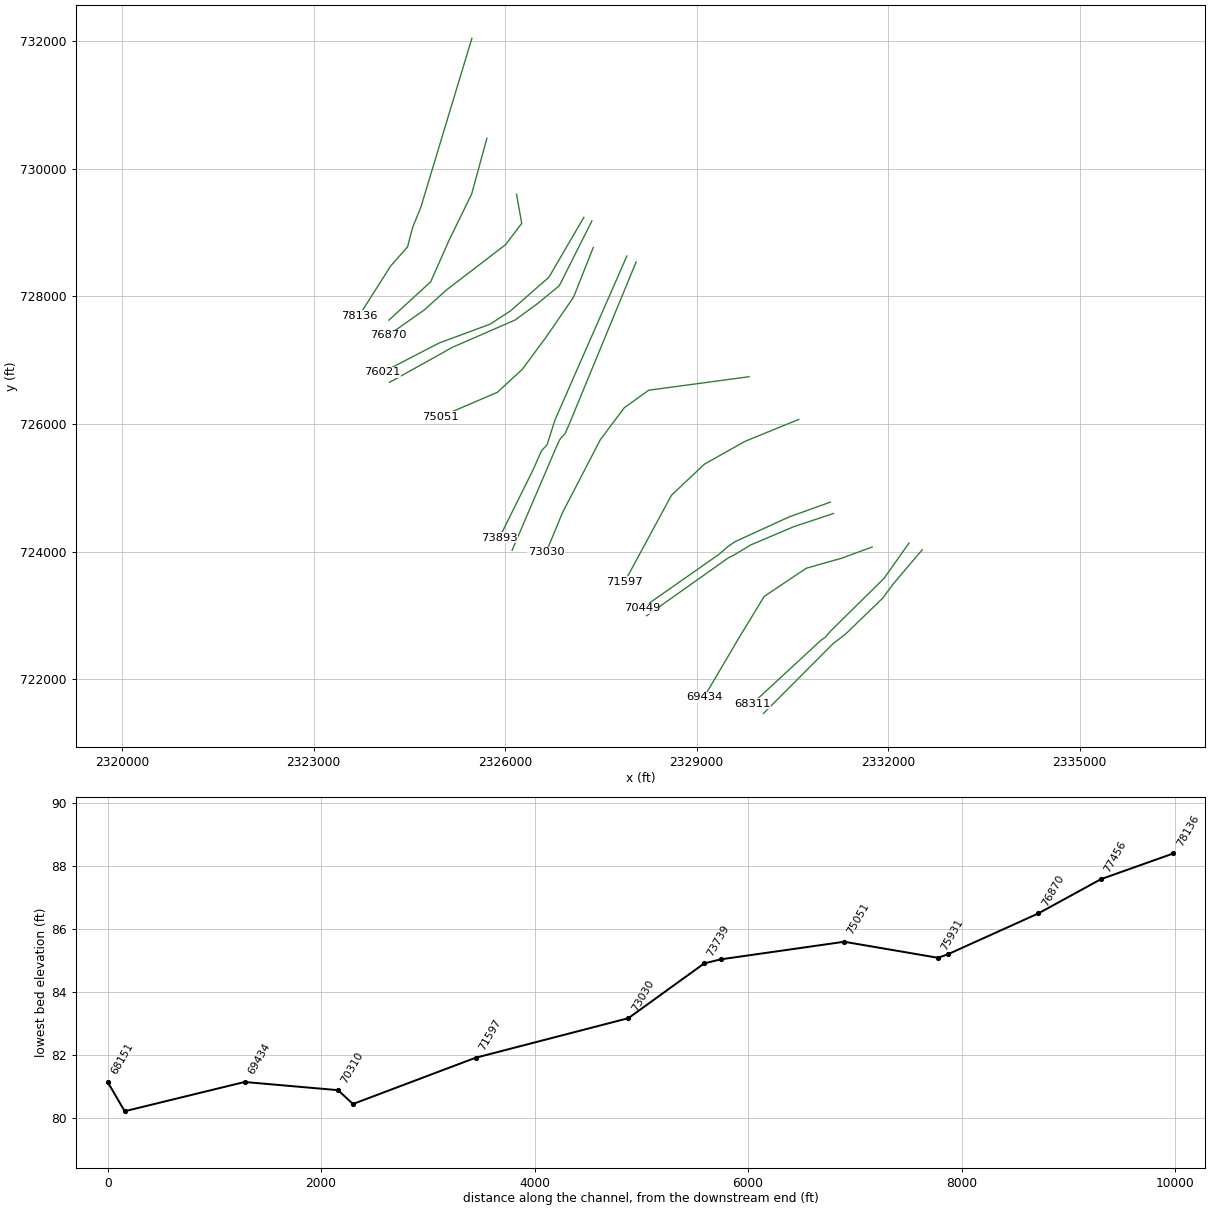
HEC-RAS study DTL_Toisnot_Swamp_Upstream.prj: DTL_Toisnot_Swamp_Upstream

--- DTL_Toisnot_Swamp_Upstream.g01 (geometry) --- (continued)

Type RM Length L Ch R = 3 ,78208   ,,,
BEGIN DESCRIPTION:
Corbett Ave
END DESCRIPTION:
Bridge Culvert--1,0,-1,-1, 0
Deck Dist Width WeirC Skew NumUp NumDn MinLoCord MaxHiCord MaxSubmerge Is_Ogee
21.94,47.35,2.6,0, 60, 60, , , 0.98, 0, 1,1,,
       0  210.08  274.83  287.04  295.48   442.8  461.37  611.13   648.5  797.85
  814.84  827.19  837.27  943.77 1012.77 1052.83 1063.44 1133.45 1167.83 1177.04
 1192.57 1394.25 1438.89 1441.82 1563.48 2013.07 2034.64 2055.63  2086.6 2093.18
 2107.75 2187.74 2458.85 2538.22 2550.67 2577.292749.0972798.2152839.2152962.215
3012.8363161.933 3169.79 3232.96 3289.07 3308.45 3320.07 3336.74 3369.63 3527.52
 3556.13 3689.45 3756.96 3801.63 3847.52 3896.79 3923.23 4048.07    4198 4417.89
  117.06   113.2  112.53  111.76  111.97  108.57  108.77  106.39  106.54  105.11
  105.43  104.92  105.38  104.62  105.03  104.56  104.94   104.5  104.84  104.45
  104.85  102.09  102.06  102.52  100.88   98.63   98.09   98.76   97.91   98.26
   97.81   97.62   98.44   97.94   98.68   98.36   99.86  100.48  100.58  100.45
  100.41   99.08   98.54   98.56   97.91   98.65   98.18   98.65   98.12   98.94
   98.61   99.97  101.26  102.66  104.89  105.73  106.04  105.13  106.18   111.4
                                                                                
                                                                                
                                                                                
                                                           98.68   98.78   98.65
                                                                                
                                                                                
       0  210.08  274.83  287.04  295.48   442.8  461.37  611.13   648.5  797.85
  814.84  827.19  837.27  943.77 1012.77 1052.83 1063.44 1133.45 1167.83 1177.04
 1192.57 1394.25 1438.89 1441.82 1563.48 2013.07 2034.64 2055.63  2086.6 2093.18
 2107.75 2187.74 2458.85 2538.22 2550.67 2577.292749.0972798.2152839.2152962.215
3012.8363161.933 3169.79 3232.96 3289.07 3308.45 3320.07 3336.74 3369.63 3527.52
 3556.13 3689.45 3756.96 3801.63 3847.52 3896.79 3923.23 4048.07    4198 4417.89
  117.06   113.2  112.53  111.76  111.97  108.57  108.77  106.39  106.54  105.11
  105.43  104.92  105.38  104.62  105.03  104.56  104.94   104.5  104.84  104.45
  104.85  102.09  102.06  102.52  100.88   98.63   98.09   98.76   97.91   98.26
   97.81   97.62   98.44   97.94   98.68   98.36   99.86  100.48  100.58  100.45
  100.41   99.08   98.54   98.56   97.91   98.65   98.18   98.65   98.12   98.94
   98.61   99.97  101.26  102.66  104.89  105.73  106.04  105.13  106.18   111.4
                                                                                
                                                                                
                                                                                
                                                           98.68   98.78   98.65
                                                                                
                                                                                
Pier Skew, UpSta & Num, DnSta & Num=  ,2839.22, 4 ,2839.22, 4 , 3 , 3 , 0 ,,
     1.5     1.5       2       2
   91.02   96.78   96.78   98.78
     1.5     1.5       2       2
   91.02   96.78   96.78   98.78
Pier Skew, UpSta & Num, DnSta & Num=  ,2876.8, 4 ,2876.8, 4 , 3 , 3 , 0 ,,
     1.5     1.5       2       2
   91.02   96.78   96.78   98.78
     1.5     1.5       2       2
   91.02   96.78   96.78   98.78
Pier Skew, UpSta & Num, DnSta & Num=  ,2914.57, 4 ,2914.57, 4 , 3 , 3 , 0 ,,
     1.5     1.5       2       2
   91.02   96.78   96.78   98.78
     1.5     1.5       2       2
   91.02   96.78   96.78   98.78
BR Coef=-1 , 1 , 0 ,1.25, 0 ,,,0.8,0,2,0,
WSPro=,,,, 1 ,,,, 0 ,,,, 0 ,,,,-1 ,-1 ,-1 , 0 , 0 , 0 , 0 , 0
BC Design=,, 0 ,, 0 ,,,,,,
BC Use User HTab Curves=0
BC User HTab FreeFlow(D)= 0

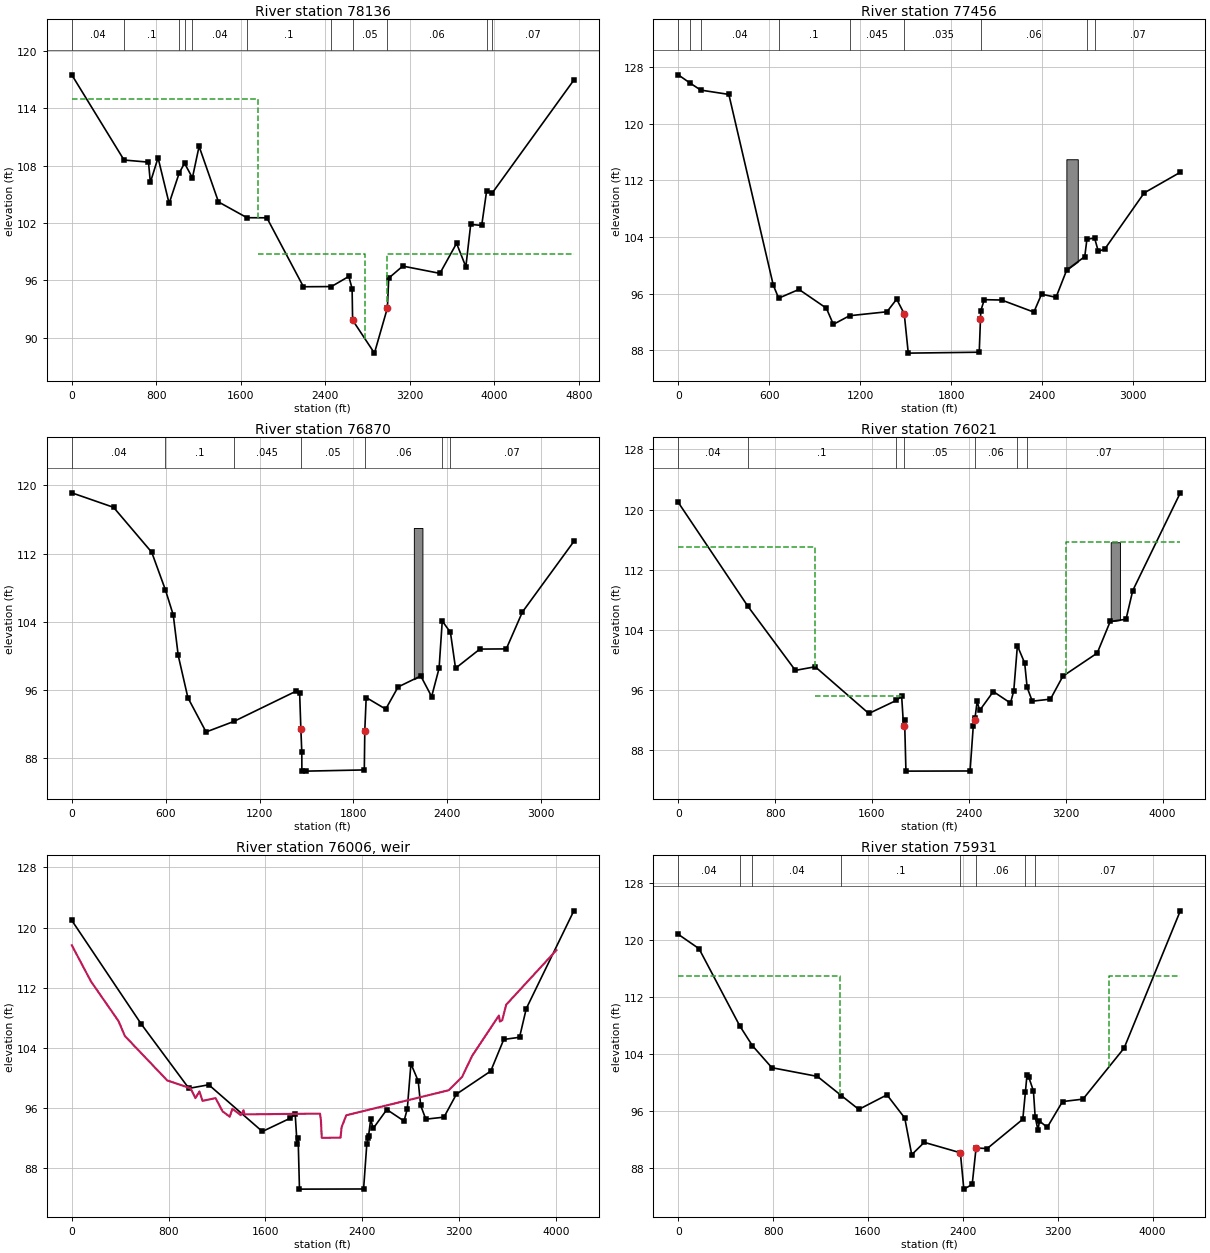
Type RM Length L Ch R = 1 ,78136   ,720.72,679.69,645.8
BEGIN DESCRIPTION:
Surveyed Section
END DESCRIPTION:
XS GIS Cut Line= 6
   2325480.04282  732042.3018177    2324680.0278     729393.2152
     2324552.272     729079.3219 2324472.6324706  728774.2811582
 2324209.5245201  728476.3034794 2323710.5327504  727690.2305921
#Sta/Elev= 30
       0   117.5  494.82  108.59  726.34  108.37  744.04  106.25  816.86  108.83
  921.67  104.05 1017.21  107.24  1067.6  108.25 1142.22  106.73 1205.39  110.02
  1388.9  104.21 1658.68  102.56 1847.04  102.55 2193.22   95.34  2458.1   95.36
2622.959   96.422654.063   95.142658.804   91.852865.365    88.42988.175   93.12
3000.557   96.24 3133.59    97.5 3485.31   96.74 3643.02   99.88  3730.9   97.43
 3776.84  101.86 3880.92  101.75    3928  105.39 3978.53  105.11 4753.32  116.95
#Mann= 11 ,-1 , 0
       0     .04       0  494.82      .1       0 1017.21     .04       0
  1067.6    .035       0 1142.22     .04       0 1658.68      .1       0
  2458.1    .045       02658.804     .05       02988.175     .06       0
    3928    .035       0 3978.53     .07       0
#XS Ineff= 3 ,-1
       0    1760     115    1760  2778.2   98.74 2982.22 4753.32   98.74
Permanent Ineff=
       F       F       F
Bank Sta=2658.804,2988.175
XS Rating Curve= 0 ,0
Exp/Cntr=0.5,0.3

Type RM Length L Ch R = 1 ,77456   ,1015.92,586.47,263.72
XS GIS Cut Line= 5
 2325715.5747431  730475.8776398  2325476.417743  729601.8974145
 2325126.5564268  728885.5147195   2324835.00533  728227.4422438
 2324180.5213178  727625.7966756
#Sta/Elev= 30
       0  126.94   80.48  125.74  148.38124.7807  333.79  124.17  626.83   97.21
  662.43   95.35  796.39   96.59  977.02   93.94 1023.19   91.65  1130.1   92.87
 1376.98   93.43 1440.91   95.21 1490.98   93.14  1517.5   87.58 1985.64   87.71
 1993.93   92.44 1995.94   93.55 2018.73   95.14 2133.57   95.09    2346   93.38
 2396.84   95.92 2492.19   95.47 2562.84   99.34 2681.79  101.23 2696.07103.7036
 2746.75  103.84 2771.41  101.96 2814.49  102.32 3073.84  110.24 3312.13  113.16
#Mann= 9 ,-1 , 0
       0     .04       0   80.48     .05       0  148.38     .04       0
  662.43      .1       0  1130.1    .045       0 1490.98    .035       0
 1995.94     .06       0 2696.07    .035       0 2746.75     .07       0
#Block Obstruct= 1 ,-1
 2560.52 2635.71     115
Bank Sta=1490.98,1993.93
XS Rating Curve= 0 ,0
Exp/Cntr=0.3,0.1

Type RM Length L Ch R = 1 ,76870   ,897.04,848.43,716.9
XS GIS Cut Line= 6
 2326179.2825378  729598.0186086 2326260.7750795  729143.0617872
 2326009.5397486  728810.5444375 2325076.5762388  728094.1617425
  2324735.044954   727785.950583 2324169.2921351  727387.4421369
#Sta/Elev= 30
       0  119.12  266.98  117.42  510.94  112.15  598.37  107.74   648.5   104.8
  680.32  100.05  741.99    95.1  858.26   91.08 1036.33   92.32 1432.87   95.86
 1456.15   95.67 1464.09   91.38 1470.03   88.71 1470.38   86.54 1498.65   86.49
 1869.39   86.63 1872.53   91.24 1881.45   95.12 2006.26   93.76 2085.36   96.36
 2230.19   97.65 2299.59   95.23  2347.3   98.55 2367.51  104.09 2419.81102.7574
 2452.43   98.55 2607.95   100.8 2776.73  100.82 2879.53  105.14 3208.44  113.42
#Mann= 7 ,-1 , 0
       0     .04       0  598.37      .1       0 1036.33    .045       0
 1464.09     .05       0 1872.53     .06       0 2367.51    .035       0
 2419.81     .07       0
#Block Obstruct= 1 ,-1
 2185.95 2240.81     115
Bank Sta=1464.09,1872.53
XS Rating Curve= 0 ,0
Exp/Cntr=0.5,0.3

Type RM Length L Ch R = 1 ,76021   ,207.21,90.65,159.9
BEGIN DESCRIPTION:
Surveyed Section
END DESCRIPTION:
XS GIS Cut Line= 6
 2327233.9326239  729237.5536435 2326687.4201139  728299.5251965
 2326085.0017758  727771.0296774  2325764.453445   727562.187583
 2324969.5863246   727268.824923 2324078.1850975  726807.1069131
#Sta/Elev= 30
       0  120.96  574.74  107.14  967.34    98.6 1131.35   99.08 1574.14   92.86
 1800.93    94.6 1845.25   95.17 1861.06   91.13 1869.48   92.01 1880.61   85.19
 2410.23   85.21 2436.74   91.192449.967   92.04 2451.55   92.28 2468.74   94.49
 2489.24   93.26 2602.18   95.78 2744.16   94.25 2771.22   95.88 2801.12  101.88
 2861.32   99.58 2881.57   96.33 2924.13    94.5 3074.14   94.77 3176.97   97.83
 3460.37   100.9 3567.81  105.11 3698.24   105.4 3753.87  109.22 4146.71  122.23
#Mann= 7 ,-1 , 0
       0     .04       0  574.74      .1       0 1800.93    .045       0
 1861.06     .05       0 2451.55     .06       0 2801.12    .035       0
 2881.57     .07       0
#XS Ineff= 4 ,-1
       0 1131.35     115 1131.35    1836   95.23    2474 3202.62   93.71
 3202.62    4145  115.66
Permanent Ineff=
       F       F       F       F
#Block Obstruct= 1 ,-1
 3571.91 3648.18 115.656
Bank Sta=1861.06,2449.967
XS Rating Curve= 0 ,0
Exp/Cntr=0.5,0.3

Type RM Length L Ch R = 5 ,76006   ,,,
BEGIN DESCRIPTION:
Toisnot Park Dam
END DESCRIPTION:
IW Pilot Flow=0
#Inline Weir SE= 30
     .16  117.65  158.06  112.85  387.02  107.53  438.62  105.57  788.28   99.66
   981.3    98.6 1021.42    97.3 1054.27   98.19 1079.45   96.94 1187.31    97.3
 1245.95   95.54 1304.73   94.83 1326.57   95.88 1396.08   95.03 1418.33   95.69
 1427.27   95.142050.074   95.242057.702   94.382064.702  92.0132219.702  92.044
2228.776   93.442267.092   95.02 3113.15   98.35 3223.58  100.12  3306.3  102.92
 3527.66  108.29 3536.12  107.49 3555.08  107.67 3587.74  109.73    4003     117
IW Dist,WD,Coef,Skew,MaxSub,Min_El,Is_Ogee,SpillHt,DesHd
14,40,2.6,0,0.98,, 0 ,,,0,0,

Type RM Length L Ch R = 1 ,75931   ,702.58,879.31,896.24
BEGIN DESCRIPTION:
Surveyed Section
END DESCRIPTION:
XS GIS Cut Line= 6
 2327359.7905495   729180.917577 2326849.0985882  728164.7931346
 2326512.2684334  727888.5924077 2326159.5164379  727629.1703158
 2325178.4210206   727201.458892 2324191.8920089  726651.7074674
#Sta/Elev= 30
       0  120.82  175.27   118.8  518.66  107.98  625.35   105.2  789.46  102.11
 1173.21  100.89 1376.69   98.18 1522.83   96.26 1760.33    98.3 1910.27   95.05
 1968.99   89.91 2074.56   91.642379.157   90.182408.375   85.08 2478.84   85.73
2511.517   90.85 2605.22   90.77 2905.63   94.88 2927.33   98.65 2940.81  101.08
 2954.83  100.84  2995.4   98.84  3009.9   95.21 3033.69   93.34 3045.98   94.64
 3111.47   93.74 3240.61   97.36 3413.05    97.7 3759.63  104.85 4233.92  124.11
#Mann= 8 ,-1 , 0
       0     .04       0  518.66      .1       0  625.35     .04       0
 1376.69      .1       02379.157     .05       02511.517     .06       0
 2927.33    .035       0  3009.9     .07       0
#XS Ineff= 2 , 0
       0 1361.59     115    3630       0     115
Permanent Ineff=
       F       F
Bank Sta=2379.157,2511.517
XS Rating Curve= 0 ,0
Exp/Cntr=0.5,0.3

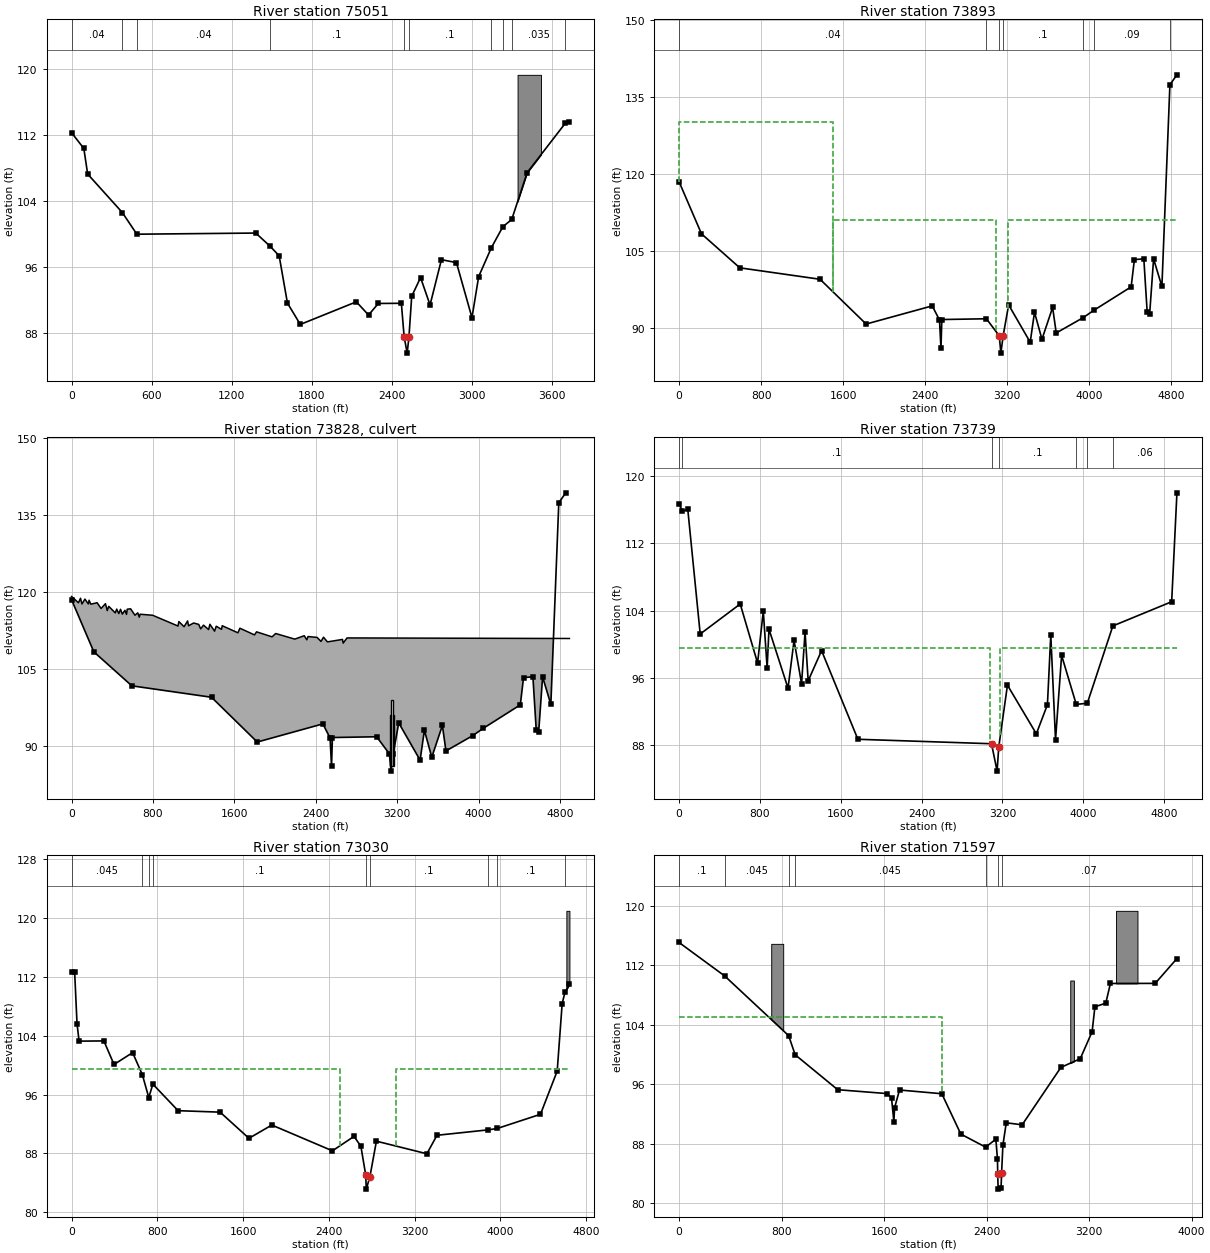
Type RM Length L Ch R = 1 ,75051   ,850.72,1158.42,1295.54
XS GIS Cut Line= 6
 2327381.2902327  728764.3508101 2327072.6684077  727985.8945102
 2326635.5619608  727350.1033146 2326267.9951759  726853.3914431
 2325880.5599161  726495.7588956 2324984.9458941  726111.6142842
#Sta/Elev= 30
       0  112.26   91.84  110.36  120.56  107.26  380.32   102.6  488.83   99.98
  1379.6  100.12 1488.48    98.5 1554.83   97.36 1616.64   91.65 1713.08   89.06
 2132.75    91.8 2224.29    90.2 2297.43    91.6 2469.99   91.62 2490.56   87.59
 2513.42   85.59 2526.87   87.56 2547.37   92.47 2613.78   94.73 2684.77   91.42
 2770.08    96.9 2882.58   96.54 2998.73   89.88    3049   94.86 3144.75   98.37
 3230.14  100.89 3296.51  101.76 3411.95  107.43 3697.71  113.41 3728.66  113.56
#Mann= 10 ,-1 , 0
       0     .04       0  380.32      .1       0  488.83     .04       0
 1488.48      .1       0 2490.56     .05       0 2526.87      .1       0
 3144.75     .06       0 3230.14    .035       0 3296.51    .035       0
 3697.71     .07       0
#XS Ineff= 2 , 0
       0 1436.32                       0
Permanent Ineff=
       F       F
#Block Obstruct= 1 ,-1
 3340.23 3515.48 119.266
Bank Sta=2490.56,2526.87
XS Rating Curve= 0 ,0
Exp/Cntr=0.5,0.3

Type RM Length L Ch R = 1 ,73893   ,227.84,153.77,202.01
BEGIN DESCRIPTION:
Surveyed Section
END DESCRIPTION:
XS GIS Cut Line= 6
 2327907.6730872  728630.1594592 2326782.4778545  726062.9377048
    2326657.3294      725672.069 2326569.2829683  725577.3271307
 2326441.8697723  725286.0663772 2325911.3391475  724218.0820255
#Sta/Elev= 30
       0  118.45   218.8  108.29  592.57  101.66 1375.56   99.43 1824.91    90.7
 2469.85   94.24 2540.64   91.49 2554.96   85.96 2563.52   91.58 2998.22   91.73
3123.955   88.39 3139.24   85.03 3162.13   88.463215.136   94.44 3425.52   87.16
 3467.47      93 3540.29   87.73  3644.3   93.94 3679.44   88.96 3940.97   91.93
 4047.34   93.39 4410.23   97.95 4442.06  103.27    4534  103.41 4566.45   93.11
  4590.5   92.57 4629.26  103.41 4710.35   98.03 4788.51  137.37    4857  139.29
#Mann= 7 ,-1 , 0
       0     .04       0 2998.22      .1       03123.955     .05       0
 3162.13      .1       0 3940.97     .06       0 4047.34     .09       0
 4788.51    .035       0
#XS Ineff= 3 ,-1
       0    1500     130    1500    3092  110.89    3208    4857  110.89
Permanent Ineff=
       F       F       F
Bank Sta=3123.955,3162.13
XS Rating Curve= 0 ,0
Exp/Cntr=0.5,0.3

Type RM Length L Ch R = 2 ,73828   ,,,
BEGIN DESCRIPTION:
Railroad
END DESCRIPTION:
Bridge Culvert--1,0,-1,-1, 0
Deck Dist Width WeirC Skew NumUp NumDn MinLoCord MaxHiCord MaxSubmerge Is_Ogee
46.5,15,2.6,0, 60, 60, , , 0.95, 0, 1,1,,
       0   67.68    87.9  102.06  131.31  165.05  172.02  189.09  251.34  290.38
  333.31  350.76  365.34  429.75  443.39  464.24   481.2   498.8  524.71  540.23
   547.3   580.2  622.95   650.8  665.39  673.82  796.71 1046.18 1054.47  1105.7
 1140.56  1150.2 1199.26 1249.67 1268.96 1296.86 1346.98 1359.39 1405.45 1421.77
 1473.61 1480.71 1634.84 1654.45 1797.97 1818.29 1970.49 2005.84 2193.53 2286.71
 2311.89 2324.28 2413.31 2451.46 2476.03 2514.84 2662.81  2669.2 2707.51 4893.02
  119.08  117.85  118.74  117.62  118.57  117.63  118.35  117.58  117.86  116.74
  117.68  116.33  117.16  115.88  116.62  115.75  116.58  115.65  116.38  115.59
   116.6  116.68  115.43  115.89  115.04  115.62  115.42  113.32  114.19  113.19
  114.31  113.37  113.91  113.64  112.76  113.49  112.63  113.66  112.32  113.28
  112.68  113.38     112  112.89  111.59  112.19  111.21  111.86  110.77  111.43
  110.64  111.27   111.1  110.32  111.14  110.23  110.71  109.99     111  110.89
                                                                                
                                                                                
                                                                                
                                                                                
                                                                                
                                                                                
       0   67.68    87.9  102.06  131.31  165.05  172.02  189.09  251.34  290.38
  333.31  350.76  365.34  429.75  443.39  464.24   481.2   498.8  524.71  540.23
   547.3   580.2  622.95   650.8  665.39  673.82  796.71 1046.18 1054.47  1105.7
 1140.56  1150.2 1199.26 1249.67 1268.96 1296.86 1346.98 1359.39 1405.45 1421.77
 1473.61 1480.71 1634.84 1654.45 1797.97 1818.29 1970.49 2005.84 2193.53 2286.71
 2311.89 2324.28 2413.31 2451.46 2476.03 2514.84 2662.81  2669.2 2707.51 4893.02
  119.08  117.85  118.74  117.62  118.57  117.63  118.35  117.58  117.86  116.74
  117.68  116.33  117.16  115.88  116.62  115.75  116.58  115.65  116.38  115.59
   116.6  116.68  115.43  115.89  115.04  115.62  115.42  113.32  114.19  113.19
  114.31  113.37  113.91  113.64  112.76  113.49  112.63  113.66  112.32  113.28
  112.68  113.38     112  112.89  111.59  112.19  111.21  111.86  110.77  111.43
  110.64  111.27   111.1  110.32  111.14  110.23  110.71  109.99     111  110.89
                                                                                
                                                                                
                                                                                
                                                                                
                                                                                
                                                                                
BR Coef=-1 , 1 , 0 ,1.25, 0 ,,,0.8,0,2,0,
WSPro=,,,, 1 ,,,, 0 ,,,, 0 ,,,,-1 ,-1 ,-1 , 0 , 0 , 0 , 0 , 0
Culvert=2,10,14.5,50,0.011,0.4,1,8,1,85.99,3134.06,84.99,3127.13,Culvert #1  , 0 ,30
Culvert Bottom n=0.011
Culvert=2,13,15,50,0.011,0.5,1,8,3,85.99,3149.81,84.99,3142.88,Culvert #2  , 0 ,30
Culvert Bottom n=0.011
Culvert=2,10,14.5,50,0.011,0.4,1,8,1,85.99,3165.56,84.99,3158.63,Culvert #3  , 0 ,30
Culvert Bottom n=0.011
BC Design=,, 0 ,, 0 ,,,,,,
BC Use User HTab Curves=0
BC User HTab FreeFlow(D)= 0

Type RM Length L Ch R = 1 ,73739   ,703.92,709.45,566.78
BEGIN DESCRIPTION:
Surveyed Section
END DESCRIPTION:
XS GIS Cut Line= 6
 2328052.7640514  728538.3672165 2327010.4779411  726009.6389832
 2326942.3740192  725852.7038587    2326858.6109     725757.9372
    2326810.3222     725654.9694 2326110.3217551  724019.8200455
#Sta/Elev= 30
       0  116.73   33.01  115.83   86.42  116.04   209.2  101.22  605.08  104.79
  777.03   97.77  833.49  103.94  871.53   97.17  889.69  101.79  1078.2   94.77
  1137.9  100.46 1212.07   95.31 1246.73  101.43 1277.53   95.65 1410.12   99.24
 1769.41   88.69 3091.65   88.16 3147.03    84.9 3162.85   87.72 3249.29   95.13
 3535.32   89.34 3644.97   92.81 3678.21  101.11 3725.02   88.62 3785.28   98.67
 3930.27   92.84 4039.64   92.98 4292.36  102.18 4874.32  105.06 4926.39  118.02
#Mann= 7 ,-1 , 0
       0    .035       0   33.01      .1       0 3091.65     .05       0
 3162.85      .1       0 3930.27     .07       0 4039.64      .1       0
 4292.36     .06       0
#XS Ineff= 2 , 0
       0    3080    99.5    3180       0    99.5
Permanent Ineff=
       F       F
Bank Sta=3091.65,3162.85
XS Rating Curve= 0 ,0
Exp/Cntr=0.5,0.3

Type RM Length L Ch R = 1 ,73030   ,1518.83,1432.37,1377.24
XS GIS Cut Line= 6
 2329820.3129954    726739.27382 2328250.3181784   726528.115851
 2327867.1367368  726253.2248169 2327492.2853267  725753.4229366
 2326900.8531017  724612.2086434 2326642.6221303  723987.4562931
#Sta/Elev= 30
       0  112.67      29  112.58   50.92  105.62   70.15  103.25  301.45  103.28
  396.04  100.08  569.34  101.69  660.32   98.69  720.22   95.59   758.3   97.41
  993.62   93.81 1385.55   93.61 1654.48   90.06 1867.89   91.86 2433.19   88.36
 2634.49   90.32 2698.43   88.98 2743.66   85.07 2748.88   83.16 2782.89   84.87
 2843.25   89.67 3313.93   87.96 3408.22   90.47 3888.54   91.21 3971.66    91.4
 4373.43   93.32 4529.48   99.19 4575.73  108.33 4602.26  109.92 4643.59  110.94
#Mann= 9 ,-1 , 0
       0    .045       0  660.32    .035       0  720.22    .045       0
   758.3      .1       0 2743.66     .05       0 2782.89      .1       0
 3888.54     .07       0 3971.66      .1       0 4602.26     .06       0
#XS Ineff= 2 , 0
       0    2500    99.5    3030       0    99.5
Permanent Ineff=
       F       F
#Block Obstruct= 1 ,-1
 4615.03 4643.59 120.941
Bank Sta=2743.66,2782.89
XS Rating Curve= 0 ,0
Exp/Cntr=0.3,0.1

Type RM Length L Ch R = 1 ,71597   ,1380.99,1148.36,1060.04
XS GIS Cut Line= 5
 2330599.3870155  726069.9641275 2329758.6205244  725727.0554013
 2329122.8293289  725369.4228538 2328606.2489825  724882.6452197
 2327875.4667682  723529.3045696
#Sta/Elev= 30
       0  115.07  355.99  110.57  855.16  102.54  906.06   99.97 1237.98   95.27
 1623.44   94.75 1657.97   94.16 1676.28   90.99 1681.97   92.85 1720.36   95.23
 2050.44   94.73 2198.95    89.3 2392.19   87.55 2472.23   88.61 2484.81   85.93
 2486.67   83.98 2489.93    81.9 2512.73   82.02 2517.08   84.12 2527.24   87.81
 2553.39   90.82 2677.44   90.55 2979.59   98.27 3130.96   99.44 3223.54  103.08
 3245.19  106.42 3330.04  106.91 3366.27  109.56 3715.72  109.57 3885.32  112.91
#Mann= 7 ,-1 , 0
       0      .1       0  355.99    .045       0  855.16    .035       0
  906.06    .045       0 2392.19      .1       0 2486.67     .05       0
 2517.08     .07       0
#XS Ineff= 2 , 0
       0    2050     105               0
Permanent Ineff=
       F       F
#Block Obstruct= 3 ,-1
  719.22  812.68 114.889 3052.66 3081.14 109.958 3409.94  3577.4 119.329
Bank Sta=2486.67,2517.08
XS Rating Curve= 0 ,0
Exp/Cntr=0.5,0.3

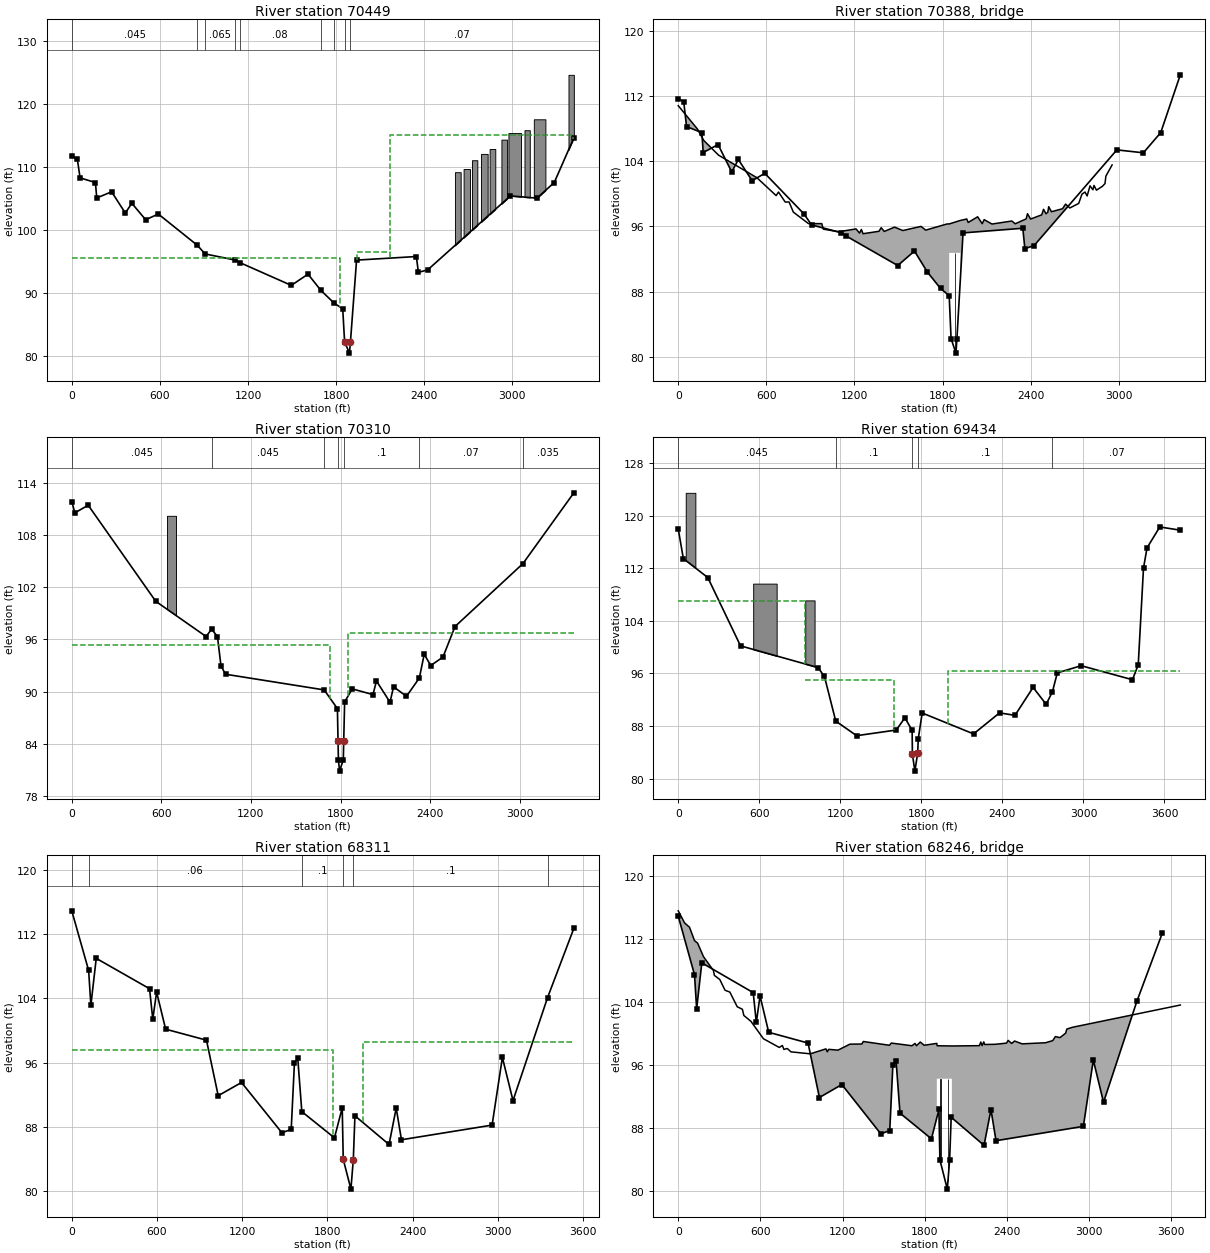
Type RM Length L Ch R = 1 ,70449   ,165.85,139.49,134.35
BEGIN DESCRIPTION:
Surveyed Section
END DESCRIPTION:
XS GIS Cut Line= 6
 2331094.5980881   724774.062149 2330446.3538962  724541.0588551
  2329606.246923  724156.6184137 2329493.0564497  724080.2806527
    2329351.8373     723956.9083 2328140.0080703  723108.1005486
#Sta/Elev= 30
       0  111.71   37.52   111.3   56.56  108.26  160.97  107.52  170.12  105.07
  271.26  106.05  364.42  102.68  409.18  104.22  503.33  101.61  589.34  102.52
  855.82   97.54  908.13   96.18 1111.23   95.22 1143.37   94.82 1494.95   91.19
 1608.84   92.97 1696.25    90.4  1786.5   88.371845.192   87.481858.021   82.22
1891.103   80.431897.619   82.161939.532    95.2 2346.49   95.77 2360.51   93.27
 2422.86   93.63 2987.11   105.4 3167.64  105.04 3285.73  107.52 3419.17  114.62
#Mann= 9 ,-1 , 0
       0    .045       0  855.82    .035       0  908.13    .065       0
 1111.23    .035       0 1143.37     .08       0 1696.25    .045       0
  1786.5      .1       01858.021     .05       01897.619     .07       0
#XS Ineff= 3 ,-1
       0    1825   95.54    1941    2165   96.53    2165    3416     115
Permanent Ineff=
       F       F       F
#Block Obstruct= 10 ,-1
 2609.41 2648.54 109.162 2668.37  2711.7 109.669 2725.39 2761.95 111.064
 2787.07 2832.17 112.067 2845.64 2884.22 112.849 2925.94 2964.64 114.331
 2973.74 3059.36 115.374    3083 3119.12 115.829 3146.59 3225.54 117.562
 3382.63 3419.17 124.623
Bank Sta=1858.021,1897.619
XS Rating Curve= 0 ,0
Exp/Cntr=0.5,0.3

Type RM Length L Ch R = 3 ,70388   ,,,
BEGIN DESCRIPTION:
Herring St
END DESCRIPTION:
Bridge Culvert--1,0,-1,-1, 0
Deck Dist Width WeirC Skew NumUp NumDn MinLoCord MaxHiCord MaxSubmerge Is_Ogee
25.9,71.6,2.6,0, 60, 60, , , 0.95, 0, 1,1,,
       0  130.86  173.69  274.65  535.04  666.89   682.6  728.53  754.82  783.99
  887.16  977.42  988.26 1092.62 1210.64 1234.82 1247.26 1258.48 1367.28 1382.07
 1403.11 1473.36 1529.51 1653.33 1685.081830.811 1845.19 1921.19 1964.86 1974.52
 2039.04 2070.07 2083.31 2136.56 2271.86 2294.92 2369.21 2378.56 2399.35 2475.43
 2487.76 2504.49 2516.68  2522.9 2541.62 2617.07 2637.78 2666.61 2727.23 2749.36
 2770.26 2784.65 2804.28 2823.99 2831.37 2848.23 2888.99 2906.29  2912.2  2954.7
  110.83  107.96  106.56  104.75  101.99   99.78  100.22   98.99      99   97.75
   96.34   96.34   95.66   95.34   95.69   95.18   95.62    95.1    95.4   95.84
   95.38   95.91   95.49      96   95.54    96.3    96.3   96.73   96.91   96.48
   97.18   96.33   96.83   96.29   96.66   96.32   96.92   97.56    96.9   97.42
    98.1   97.55   97.74   98.42    97.8   98.17   98.74   98.26   98.82   99.96
  100.22   99.74  100.98   100.5  101.03  100.45  100.93  101.26  102.17  103.55
                                                                                
                                                                                
                                                   92.75   92.75
                                                                                
                                                                                
                                                                                
       0  130.86  173.69  274.65  535.04  666.89   682.6  728.53  754.82  783.99
  887.16  977.42  988.26 1092.62 1210.64 1234.82 1247.26 1258.48 1367.28 1382.07
 1403.11 1473.36 1529.51 1546.521741.389    17531830.8111868.478 1964.86 1974.52
 2039.04 2070.07 2083.31 2136.56 2271.86 2294.92 2369.21 2378.56 2399.35 2475.43
 2487.76 2504.49 2516.68  2522.9 2541.62 2617.07 2637.78 2666.61 2727.23 2749.36
 2770.26 2784.65 2804.28 2823.99 2831.37 2848.23 2888.99 2906.29  2912.2  2954.7
  110.83  107.96  106.56  104.75  101.99   99.78  100.22   98.99      99   97.75
   96.34   96.34   95.66   95.34   95.69   95.18   95.62    95.1    95.4   95.84
   95.38   95.91   95.49    95.9   95.77   95.77    96.3   96.55   96.91   96.48
   97.18   96.33   96.83   96.29   96.66   96.32   96.92   97.56    96.9   97.42
    98.1   97.55   97.74   98.42    97.8   98.17   98.74   98.26   98.82   99.96
  100.22   99.74  100.98   100.5  101.03  100.45  100.93  101.26  102.17  103.55
                                                                                
                                                                                
                                           91.97   91.97
                                                                                
                                                                                
                                                                                
Pier Skew, UpSta & Num, DnSta & Num=  ,1883.19, 2 ,1791.903, 2 , 0 , 0 , 0 ,,
       3       3
   80.43   92.75
       3       3
   80.87   92.75
BR Coef=-1 , 1 , 0 ,1.25, 0 ,,,0.8,0,2,0,
WSPro=,,,, 1 ,,,, 0 ,,,, 0 ,,,,-1 ,-1 ,-1 , 0 , 0 , 0 , 0 , 0
BC Design=,, 0 ,, 0 ,,,,,,
BC Use User HTab Curves=0
BC User HTab FreeFlow(D)= 0

Type RM Length L Ch R = 1 ,70310   ,759.39,875.69,960.07
BEGIN DESCRIPTION:
Surveyed Section
END DESCRIPTION:
XS GIS Cut Line= 6
 2331144.4345463  724596.0747985 2330525.2098866  724390.8442991
 2329843.1572157  724101.3393454     2329558.222     723928.0215
    2329503.9168     723905.6798 2328218.3225045  722994.1886443
#Sta/Elev= 30
       0  111.83    21.1  110.54  109.87  111.42  562.44  100.38  899.98   96.33
  936.59   97.19  975.97   96.31  999.52   92.94 1030.13      92 1690.57    90.2
1779.366   88.05 1783.36   84.381786.113   82.161793.781   80.871818.906   82.19
 1821.58   84.361827.663   88.811878.346   90.32 2017.59   89.66 2040.81   91.23
 2131.52   88.79 2155.56   90.56 2241.79   89.46 2328.19   91.57 2360.74    94.3
 2404.23      93 2486.25   93.97 2566.93   97.48 3021.97  104.71 3362.98  112.84
#Mann= 7 ,-1 , 0
       0    .045       0  936.59    .045       0 1690.57     .01       0
 1783.36     .05       0 1821.58      .1       0 2328.19     .07       0
 3021.97    .035       0
#XS Ineff= 2 , 0
       0    1733   95.37    1850       0   96.73
Permanent Ineff=
       F       F
#Block Obstruct= 1 ,-1
  637.84  698.11 110.201
Bank Sta=1783.36,1821.58
XS Rating Curve= 0 ,0
Exp/Cntr=0.5,0.3

Type RM Length L Ch R = 1 ,69434   ,1033.35,1123.14,1040.67
XS GIS Cut Line= 6
 2331748.9313401  724070.7566065 2331274.1195538  723895.8259484
 2330716.0074542   723737.555353 2330057.9349786  723296.0636921
 2329658.0934744  722637.9912165 2329115.5086119  721717.5425878
#Sta/Elev= 30
       0  117.96   37.78  113.46  219.02  110.56  461.07  100.18 1034.68   96.88
 1082.53   95.52 1166.04   88.74 1320.61   86.52 1614.33   87.38 1677.79   89.24
 1731.78   87.33 1733.54   83.71 1751.97   81.13 1772.62   83.89 1777.17   86.06
 1805.97   89.97 2186.45   86.79  2378.9   89.99 2492.99   89.61 2627.13   93.86
 2723.79   91.29 2770.33    93.2 2806.33   96.07 2983.33   97.16 3362.71   95.03
  3405.6    97.3 3444.57  112.03 3471.07   115.1 3565.18  118.26 3717.07  117.77
#Mann= 5 ,-1 , 0
       0    .045       0 1166.04      .1       0 1733.54     .05       0
 1777.17      .1       0 2770.33     .07       0
#XS Ineff= 3 ,-1
       0  940.25     107  940.25    1600      95    2000 3717.07    96.3
Permanent Ineff=
       F       F       F
#Block Obstruct= 3 ,-1
   55.46  126.82  123.45  554.82  728.62 109.645  940.25 1009.42 107.094
Bank Sta=1733.54,1772.62
XS Rating Curve= 0 ,0
Exp/Cntr=0.5,0.3

Type RM Length L Ch R = 1 ,68311   ,205.9,159.7,193.97
BEGIN DESCRIPTION:
Surveyed Section
END DESCRIPTION:
XS GIS Cut Line= 6
 2332326.2705534  724133.3076873 2331937.7665654  723582.0384648
    2331098.1285     722753.6119    2331022.6688     722662.3636
    2330941.5551     722603.8548 2329870.0451169  721613.0068046
#Sta/Elev= 30
       0  114.93  118.78  107.49   134.5  103.14  172.26     109  547.58  105.21
  570.41  101.41  597.47  104.79  660.93  100.16  948.46   98.79 1031.12   91.86
 1195.23   93.51 1479.94   87.23 1545.13   87.66  1567.8   95.95 1591.29   96.51
 1619.81   89.87 1849.57    86.61904.312   90.35  1911.5   83.921965.434    80.2
  1982.3   83.86 1993.82   89.35 2233.96   85.77 2284.42   90.32  2321.3   86.36
 2959.52   88.19 3031.97   96.63 3106.71   91.25 3350.27  104.11 3535.16  112.74
#Mann= 6 ,-1 , 0
       0    .035       0  118.78     .06       0 1619.81      .1       0
  1911.5    .045       0  1982.3      .1       0 3350.27     .07       0
#XS Ineff= 2 , 0
       0    1838   97.62    2048       0   98.51
Permanent Ineff=
       F       F
Bank Sta=1911.5,1982.3
XS Rating Curve= 0 ,0
Exp/Cntr=0.5,0.3

Type RM Length L Ch R = 3 ,68246   ,,,
BEGIN DESCRIPTION:
Rt. 301
END DESCRIPTION:
Bridge Culvert--1,0,-1,-1, 0
Deck Dist Width WeirC Skew NumUp NumDn MinLoCord MaxHiCord MaxSubmerge Is_Ogee
46,80,3,0, 60, 60, , , 0.95, 0, 1,1,,
       0   46.11   82.48  119.17  141.66  184.68  256.78  264.31  303.52   341.9
  376.91  430.94  468.69  479.35  531.44  622.36   738.1  760.52  772.12  796.42
  823.43  964.25 1078.82 1088.81  1099.2 1166.99    1254 1341.35 1351.96 1542.48
 1556.67  1707.1 1729.81    1740 1768.03 1796.44 1888.94 1888.941891.083 1998.94
 1998.94 2199.45 2210.34 2219.53 2231.82  2238.5 2312.86 2397.62 2410.16 2435.16
 2457.13 2511.53 2682.84 2735.73 2755.08 2788.03 2829.51 2838.54 2879.98 3667.59
  115.62  114.09  113.53  111.82  111.51  109.78  108.03   107.4  106.88  105.51
  105.28  103.41  103.09   102.3  101.55   99.34   98.23   98.48   97.98    98.1
   97.67   97.42   98.05   97.68   97.99   97.89   98.65   98.67   98.99   98.51
   98.79   98.45   98.74   98.45   98.92   98.51   98.75   98.75   98.45   98.42
   98.42   98.46   98.92   98.46   98.94   98.61   98.63   98.78   99.13   98.74
   99.05   98.69   98.83    99.1   99.62   99.48  100.04  100.57   100.8  103.63
                                                                                
                                                                                
                                                                                
                                                           94.25   94.25   94.25
                                                                                
                                                                                
       0   46.11   82.48  119.17  141.66  184.68  256.78  264.31  303.52   341.9
  376.91  430.94  468.69  479.35  531.44  622.36   738.1  760.52  772.12  796.42
  823.43  964.25 1078.82 1088.81  1099.2 1166.99    1254 1341.35 1351.96 1375.64
 1470.87 1542.48 1609.29  1707.1 1729.81    1740 1768.03 1796.44    1975    1975
    2085    2085 2199.45 2210.34 2219.53 2231.82  2238.5 2393.17 2410.16 2435.16
 2457.13 2511.53 2682.84 2735.73 2755.08 2788.03 2829.51 2838.54 2879.98 3667.59
  115.62  114.09  113.53  111.82  111.51  109.78  108.03   107.4  106.88  105.51
  105.28  103.41  103.09   102.3  101.55   99.34   98.23   98.48   97.98    98.1
   97.67   97.42   98.05   97.68   97.99   97.89   98.65   98.67   98.99    98.7
    98.9   98.51   98.81   98.45   98.74   98.45   98.92   98.51   98.42   98.42
   98.43   98.43   98.46   98.92   98.46   98.94   98.61   98.77   99.13   98.74
   99.05   98.69   98.83    99.1   99.62   99.48  100.04  100.57   100.8  103.63
                                                                                
                                                                                
                                                                                
                                                                           94.22
   94.22
                                                                                
Pier Skew, UpSta & Num, DnSta & Num=  ,1916, 4 ,2003, 4 , 3 , 3 , 0 ,,
       2       2     2.5     2.5
   80.63   91.75   91.75   94.25
       2       2     2.5     2.5
   80.63   91.75   91.75   94.25
Pier Skew, UpSta & Num, DnSta & Num=  ,1970, 4 ,2057, 4 , 3 , 3 , 0 ,,
       2       2     2.5     2.5
   80.63   91.75   91.75   94.25
       2       2     2.5     2.5
   80.63   91.75   91.75   94.25
Abutment Skew #Up #Dn= , 3 , 3
 1888.94 1893.94 1918.44
   91.75   91.75   81.13
    1975    1980    2000
   91.75   91.75   81.13
Abutment Skew #Up #Dn= , 3 , 3
 1971.44 1993.94 1998.94
    81.3   91.72   91.72
  2057.5    2080    2085
    81.3   91.72   91.72
BR Coef=-1 , 1 , 0 ,1.25, 0 ,,,0.8,0,2,0,
WSPro=,,,, 1 ,,,, 0 ,,,, 0 ,,,,-1 ,-1 ,-1 , 0 , 0 , 0 , 0 , 0
BC Design=,, 0 ,, 0 ,,,,,,
BC Use User HTab Curves=0
BC User HTab FreeFlow(D)= 0

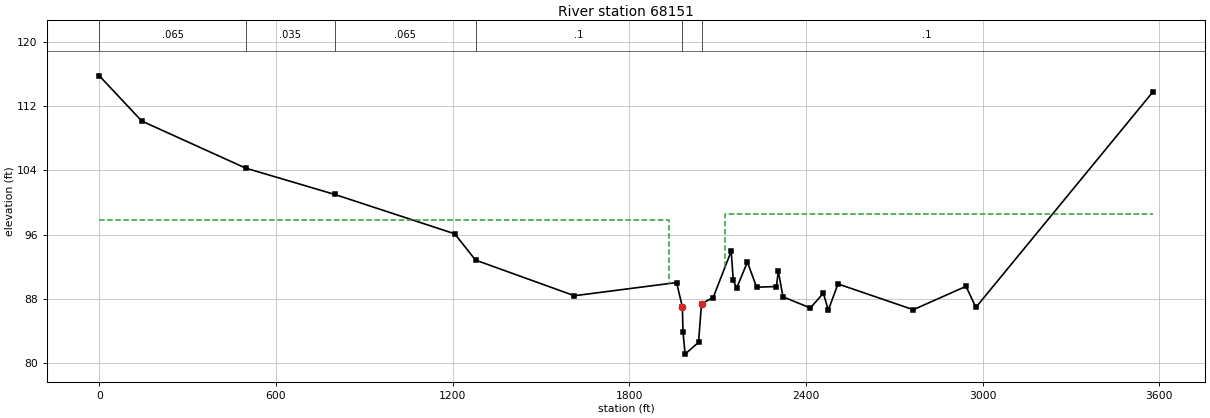
Type RM Length L Ch R = 1 ,68151   ,904.29,905.92,938.01
BEGIN DESCRIPTION:
Surveyed Section
END DESCRIPTION:
XS GIS Cut Line= 6
 2332532.7358799   724026.515277  2332077.752409  723490.1803108
 2331917.4384458  723272.1533207 2331338.3243968  722711.4656278
    2331137.1074     722555.9223 2330048.0324674  721463.4974302
#Sta/Elev= 30
       0  115.78  144.05  110.15  496.95  104.29  799.63  101.01 1207.03   96.11
 1277.62   92.84  1613.4    88.41960.573   90.041980.318   86.98  1982.3   83.88
1989.552   81.13 2035.08    82.62045.166   87.422084.628   88.16 2146.05   93.95
 2153.18    90.3 2164.63   89.35 2201.03    92.6 2232.36   89.46  2299.7   89.55
 2305.95   91.47 2321.96   88.26 2414.85   86.88 2459.04   88.71 2475.88   86.61
 2508.71   89.87 2764.41   86.66 2943.54   89.57 2977.02   86.95 3577.76  113.76
#Mann= 6 ,-1 , 0
       0    .065       0  496.95    .035       0  799.63    .065       0
 1277.62      .1       01980.318    .045       02045.166      .1       0
#XS Ineff= 2 , 0
       0    1935   97.88    2125       0   98.52
Permanent Ineff=
       F       F
Bank Sta=1980.318,2045.166
XS Rating Curve= 0 ,0
Exp/Cntr=0.5,0.3