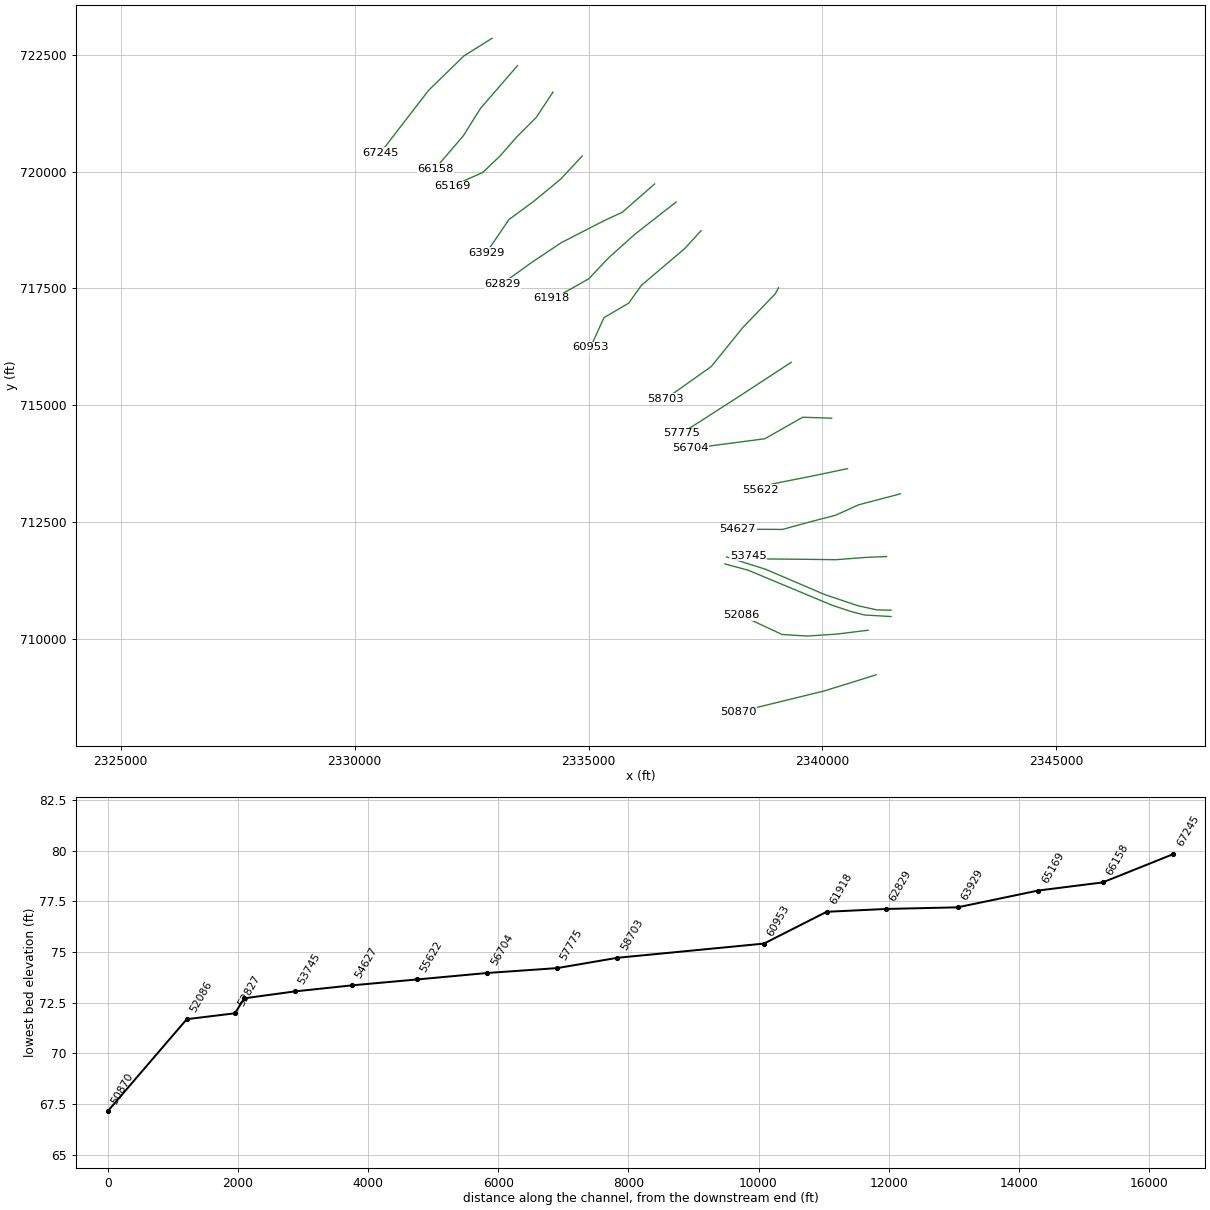
HEC-RAS study DTL_Toisnot_Swamp_Upstream.prj: DTL_Toisnot_Swamp_Upstream

--- DTL_Toisnot_Swamp_Upstream.g01 (geometry) --- (continued)

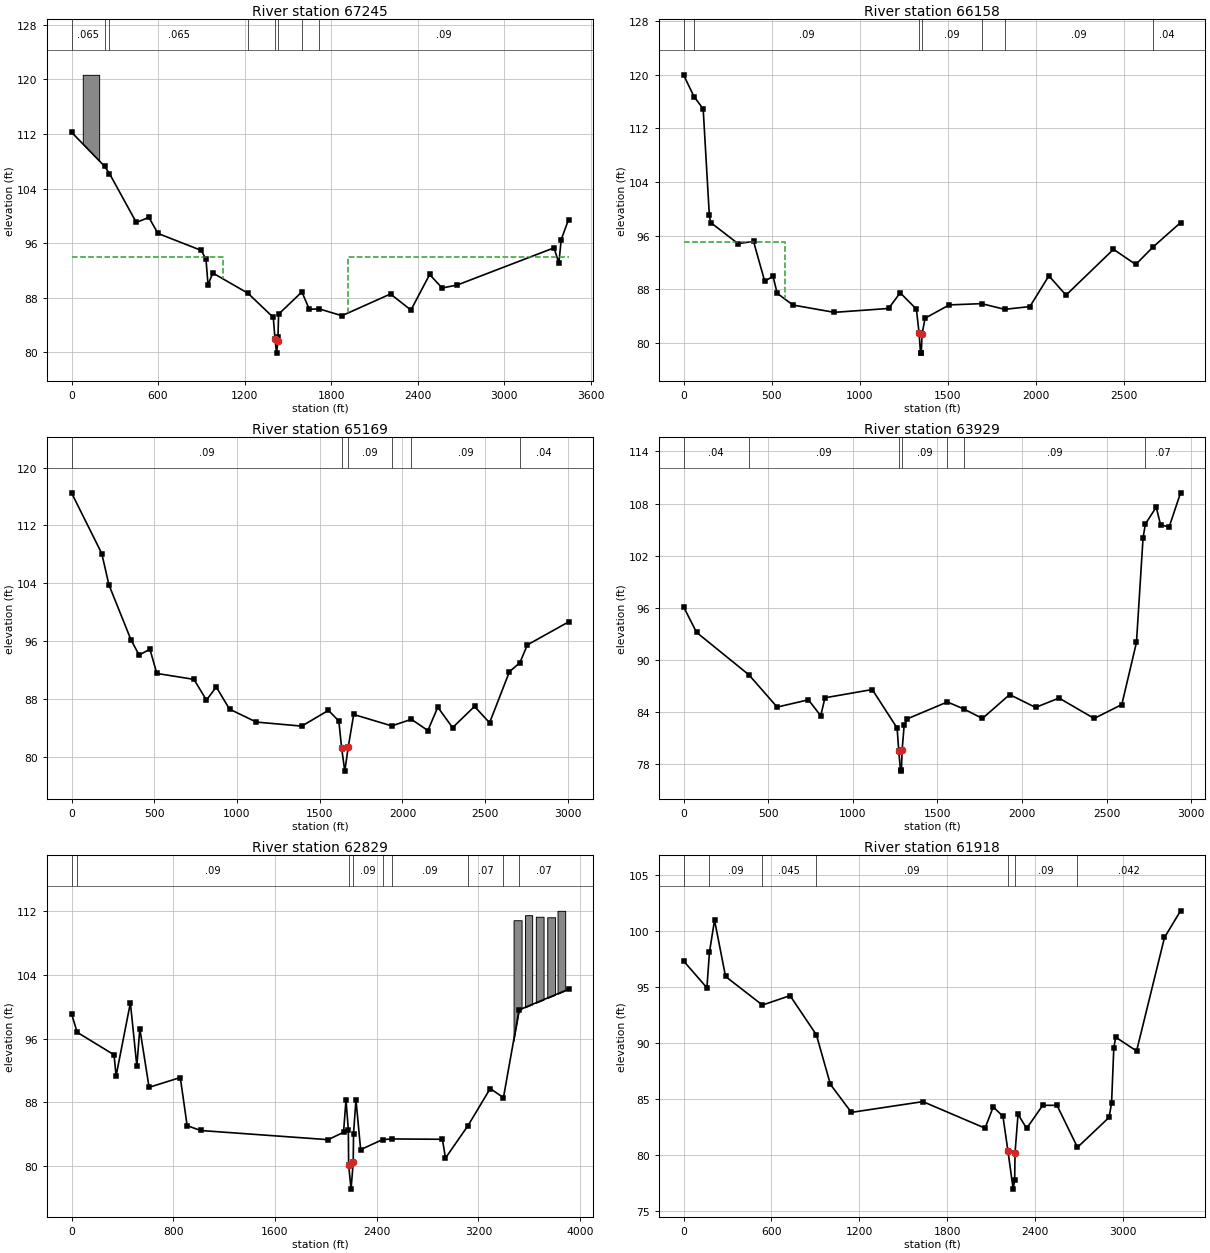
Type RM Length L Ch R = 1 ,67245   ,1031.58,1087.24,1194.06
XS GIS Cut Line= 4
 2332938.2020715  722848.7933207 2332337.8142458  722472.3927364
 2331582.8122011  721737.2591666 2330554.2302906   720404.226369
#Sta/Elev= 30
       0  112.26   230.2  107.24  262.94   106.2  449.19   99.02  536.47   99.76
  599.05   97.41  899.01   94.92  932.36   93.62  946.51   89.86  979.42    91.6
 1223.38   88.63 1399.01   85.08 1410.85   81.91 1421.85   79.84 1431.35   81.65
 1431.35   82.22 1435.85   85.56 1597.28   88.82 1648.71   86.27 1715.83   86.34
 1874.79   85.33 2211.69   88.52 2353.35   86.16 2483.03   91.38 2569.44    89.4
 2673.83   89.83 3345.39   95.29 3379.01   93.05 3395.08   96.49 3446.13   99.45
#Mann= 8 ,-1 , 0
       0    .065       0   230.2     .09       0  262.94    .065       0
 1223.38     .09       0 1410.85    .045       0 1431.35     .09       0
 1597.28     .04       0 1715.83     .09       0
#XS Ineff= 2 , 0
       0    1050      94    1915       0      94
Permanent Ineff=
       F       F
#Block Obstruct= 1 ,-1
   77.99  191.67 120.684
Bank Sta=1410.85,1431.35
XS Rating Curve= 0 ,0
Exp/Cntr=0.3,0.1

Type RM Length L Ch R = 1 ,66158   ,1042.74,988.79,855.26
XS GIS Cut Line= 4
 2333481.5778582  722263.1398063 2332692.1358847  721352.0529225
 2332322.2651115  720762.2589868  2331723.941246  720064.0115332
#Sta/Elev= 30
       0     120   59.25  116.76  111.48  114.91  146.35   99.06  154.05   97.94
  309.44   94.79  397.29   95.12  460.81   89.17  507.92   89.92  531.63   87.37
  621.13   85.62   855.7   84.53 1163.99   85.11 1229.78   87.45 1321.74   85.01
 1336.86   81.45 1345.26   78.44 1349.85   78.49 1353.66   81.26 1371.23   83.66
 1508.38   85.64 1691.61   85.83 1823.08   84.98 1965.97   85.39 2073.82   89.98
 2170.87    87.1 2440.49   93.94 2566.92   91.68 2664.66   94.28 2821.24   97.93
#Mann= 7 ,-1 , 0
       0    .065       0   59.25     .09       0 1336.86     .05       0
 1353.66     .09       0 1691.61     .04       0 1823.08     .09       0
 2664.66     .04       0
#XS Ineff= 2 , 0
       0     575      95               0
Permanent Ineff=
       F       F
Bank Sta=1336.86,1353.66
XS Rating Curve= 0 ,0
Exp/Cntr=0.3,0.1

Type RM Length L Ch R = 1 ,65169   ,1307.11,1240.54,1164.18
XS GIS Cut Line= 6
 2334239.6107099  721696.6976753 2333881.4193624  721155.2456384
 2333464.9177955  720738.7440716 2333115.0564794  720338.9025674
 2332740.2050692  719980.7112198 2332087.1613829  719688.5594262
#Sta/Elev= 30
       0   116.5  182.79  108.11  226.12  103.78  359.06    96.2   408.2   94.09
   473.9   94.88  515.39   91.54  739.74   90.72  815.35   87.85  874.54   89.67
  954.74   86.61 1116.41   84.82  1391.4   84.26 1552.51   86.44 1615.37   84.96
 1631.84    81.3 1651.21   78.04 1672.01   81.34 1705.05   85.87  1935.1   84.29
 2053.74    85.2  2153.4   83.65 2213.23   86.88 2302.58   84.05 2435.16   86.98
 2526.33   84.72  2646.2   91.78 2709.38   93.02  2754.2   95.48 3003.42   98.66
#Mann= 6 ,-1 , 0
       0     .09       0 1631.84     .05       0 1672.01     .09       0
  1935.1     .04       0 2053.74     .09       0 2709.38     .04       0
Bank Sta=1631.84,1672.01
XS Rating Curve= 0 ,0
Exp/Cntr=0.3,0.1

Type RM Length L Ch R = 1 ,63929   ,1304.24,1099.91,1047.4
XS GIS Cut Line= 5
 2334864.3630602   720330.572536 2334406.2113367  719839.1006871
 2333831.4391744  719364.2889009 2333298.3171688   718972.777428
 2332815.7316251  718262.7425295
#Sta/Elev= 30
       0   96.13   77.01   93.18  386.56   88.29  553.26   84.58  738.09   85.42
  810.91   83.58  835.74   85.65 1115.22    86.6 1262.17   82.17 1271.95   79.55
 1282.53   77.21 1287.77   77.38 1291.63    79.6 1303.88   82.48 1322.99   83.23
 1559.16   85.17 1655.2184.37445 1766.34   83.27 1927.22   86.02 2080.22   84.54
 2219.22   85.62 2426.64   83.27 2590.11   84.87 2676.76   92.02 2715.81  104.09
  2729.7  105.66 2793.46  107.59 2819.45  105.54 2870.12  105.32 2937.37  109.24
#Mann= 7 ,-1 , 0
       0     .04       0  386.56     .09       0 1271.95     .05       0
 1291.63     .09       0 1559.16     .04       0 1655.21     .09       0
  2729.7     .07       0
Bank Sta=1271.95,1291.63
XS Rating Curve= 0 ,0
Exp/Cntr=0.3,0.1

Type RM Length L Ch R = 1 ,62829   ,652.53,910.8,988.3
BEGIN DESCRIPTION:
Surveyed Section
END DESCRIPTION:
XS GIS Cut Line= 6
 2336412.8601202  719733.4603836 2335721.9925048  719128.8988891
 2335320.6109291   718942.398359    2334421.8412      718480.853
 2333789.2072951  718058.7741119 2333159.2513536   717604.731672
#Sta/Elev= 30
       0   99.13   44.56   96.79  334.03   93.97  350.62   91.33  462.93  100.49
  513.76   92.55  537.04   97.26  609.92   89.89  855.31   91.12  909.26   85.09
 1015.04   84.48 2016.92   83.332139.093   84.252158.335   88.312176.748   84.59
2179.174   80.152198.196   77.132215.212   80.472217.547   84.082236.758   88.35
2273.536   82.08 2445.53   83.34 2522.13   83.42 2916.58   83.38 2940.61   81.02
 3118.17    85.1 3292.67   89.74 3396.46    88.6 3519.57    99.6 3908.46  102.19
#Mann= 9 ,-1 , 0
       0    .045       0   44.56     .09       02179.174     .05       0
2215.212     .09       0 2445.53     .04       0 2522.13     .09       0
 3118.17     .07       0 3396.46     .09       0 3519.57     .07       0
#Block Obstruct= 5 ,-1
    3476 3539.08 110.838 3565.99 3622.36 111.472 3651.15 3711.98 111.274
 3740.94 3802.62  111.21 3821.78 3882.09 112.018
Bank Sta=2179.174,2215.212
XS Rating Curve= 0 ,0
Exp/Cntr=0.3,0.1

Type RM Length L Ch R = 1 ,61918   ,924.24,964.78,915.51
XS GIS Cut Line= 6
 2336871.9006125  719347.6288382 2335988.9172908  718656.2362372
 2335430.8051912   718156.434357 2335005.9735929  717706.6126648
 2334431.2014307  717381.7414426 2334206.2905846  717290.1110979
#Sta/Elev= 30
       0   97.36  159.62   94.96  176.78   98.12   211.7     101  286.82   95.97
  538.49   93.42  727.21   94.26  906.99   90.76 1002.72   86.34 1145.55   83.84
 1634.07    84.8 2058.51   82.43  2114.1   84.33 2180.54   83.49 2215.16   80.35
 2250.37   76.99 2260.64    77.8 2263.08   80.24 2283.58   83.67 2342.39   82.41
 2452.18   84.47 2549.51   84.47  2689.4   80.72 2904.86   83.39 2922.11   84.66
 2937.46   89.62 2950.44   90.55 3092.86   89.32 3283.45   99.45 3393.14  101.83
#Mann= 7 ,-1 , 0
       0    .045       0  176.78     .09       0  538.49    .045       0
  906.99     .09       0 2215.16     .05       0 2263.08     .09       0
  2689.4    .042       0
Bank Sta=2215.16,2263.08
XS Rating Curve= 0 ,0
Exp/Cntr=0.3,0.1

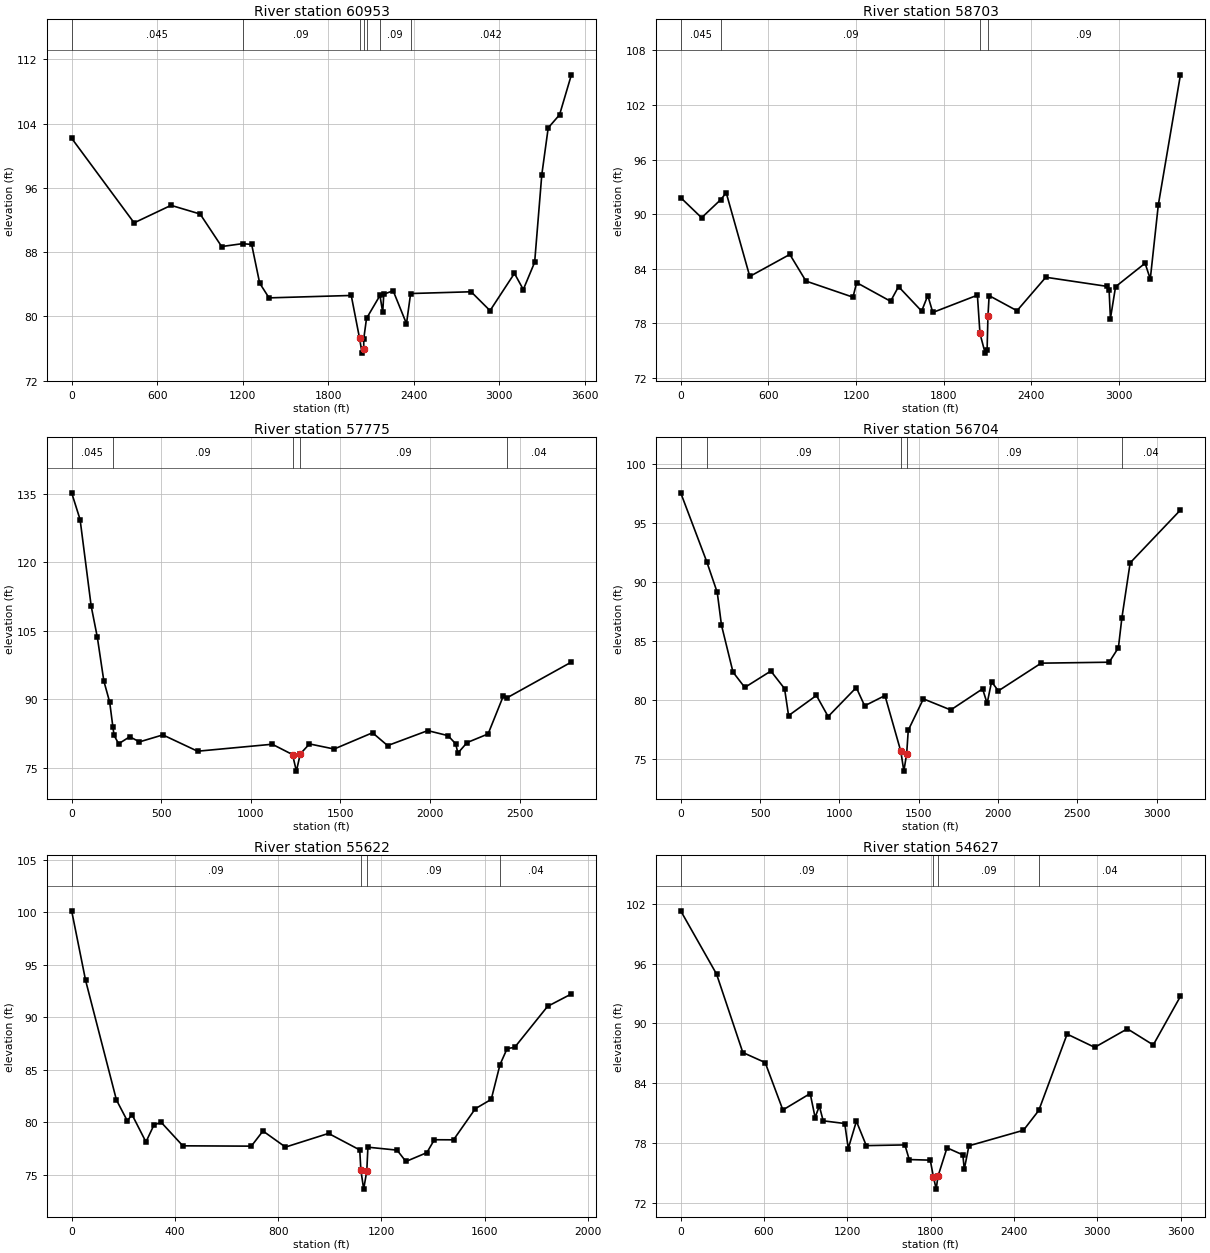
Type RM Length L Ch R = 1 ,60953   ,2275.72,2249.83,2285.2
XS GIS Cut Line= 6
 2337405.3556383  718733.5488014 2337058.9102513  718354.8000676
 2336129.2350645  717565.0759842 2335859.3293651  717185.2087036
 2335329.5144737  716875.3169746 2335043.4169086  716242.7228233
#Sta/Elev= 30
       0  102.17  438.34   91.64  697.55   93.82  901.56   92.74 1052.77   88.69
 1199.11   89.05 1263.39   88.95 1319.62   84.13 1385.23    82.3 1962.24    82.6
 2020.79   77.25 2037.99   75.42 2049.95   75.89 2049.95   77.19  2069.4   79.74
 2163.93    82.6 2183.04   80.48  2190.6   82.75 2256.29   83.19    2350   79.08
 2378.93   82.84 2803.48   83.06 2936.32   80.71 3107.54   85.35 3169.83   83.34
 3249.41   86.73 3299.63   97.64 3344.63  103.47 3424.14  105.09 3507.19  110.07
#Mann= 7 ,-1 , 0
       0    .045       0 1199.11     .09       0 2020.79     .05       0
 2049.95     .09       0  2069.4    .042       0 2163.93     .09       0
 2378.93    .042       0
Bank Sta=2020.79,2049.95
XS Rating Curve= 0 ,0
Exp/Cntr=0.3,0.1

Type RM Length L Ch R = 1 ,58703   ,1101.14,927.98,854.97
XS GIS Cut Line= 5
 2339062.5599998  717514.2236411 2338988.7862053  717381.0960534
 2338300.0124101  716665.8309584 2337624.4842649  715831.3550143
 2336644.1194886  715136.2027486
#Sta/Elev= 30
       0   91.81  143.05    89.6  274.68    91.6  311.45   92.35  472.73   83.15
   746.9   85.57  857.33   82.64 1179.21   80.87 1204.38   82.47 1436.53   80.42
 1490.97   82.03  1649.2   79.34  1691.3   81.05 1725.72   79.19 2030.89   81.09
 2048.44   76.88 2083.89   74.72 2097.18   75.04 2103.03   78.76 2111.24   81.04
  2301.9   79.38 2499.11   83.06 2917.29   82.06 2932.22    81.7 2941.47   78.52
 2976.65   82.02 3178.71    84.6 3214.25   82.86 3269.24   91.01 3420.63  105.31
#Mann= 4 ,-1 , 0
       0    .045       0  274.68     .09       0 2048.44     .05       0
 2103.03     .09       0
#XS Ineff= 2 , 0
       0    1000                       0
Permanent Ineff=
       F       F
Bank Sta=2048.44,2103.03
XS Rating Curve= 0 ,0
Exp/Cntr=0.3,0.1

Type RM Length L Ch R = 1 ,57775   ,1107.41,1070.55,1043.96
XS GIS Cut Line= 3
 2339335.1721722   715921.785113 2338204.7056265  715182.6131695
 2336994.2147557  714405.1971093
#Sta/Elev= 30
       0  135.28   47.19   129.4  108.96  110.43  143.52  103.54  179.54   94.01
  212.38   89.33   230.4   83.82     237   82.03  262.44   80.22  324.24   81.75
  378.67   80.63  509.11   82.16  702.79   78.58 1119.68   80.11 1232.83   77.84
 1254.42   74.21  1276.1   77.99 1327.49   80.18  1465.2   79.06 1679.39   82.63
 1763.62   79.81 1987.69    83.1  2100.5      82  2143.5   80.21 2155.81   78.16
 2206.91   80.47 2324.52   82.37 2408.82   90.63 2431.16   90.32 2789.31   98.14
#Mann= 5 ,-1 , 0
       0    .045       0   230.4     .09       0 1232.83     .05       0
  1276.1     .09       0 2431.16     .04       0
Bank Sta=1232.83,1276.1
XS Rating Curve= 0 ,0
Exp/Cntr=0.3,0.1

Type RM Length L Ch R = 1 ,56704   ,1261.59,1082.26,1091.91
XS GIS Cut Line= 4
 2340197.8135702  714726.0678869 2339578.0301123  714746.0609016
 2338768.3130141  714286.2215619 2337183.0016441  714077.9665027
#Sta/Elev= 30
       0   97.58  163.81   91.75  230.36   89.13  256.93   86.36  329.67   82.37
  404.01   81.07  568.32   82.46  654.64   80.97  680.06   78.68  855.47   80.39
  929.45    78.6  1106.8   81.06 1159.62   79.51 1287.58   80.38 1387.69   75.64
 1406.67   73.97 1424.51   75.45 1434.49   77.44 1529.88    80.1 1702.27   79.16
 1903.01   80.95 1931.73   79.72 1959.61   81.55 2002.59   80.78 2272.22   83.13
 2700.97   83.21 2759.18   84.44 2781.01   86.96 2833.28   91.64 3150.21   96.12
#Mann= 5 ,-1 , 0
       0     .04       0  163.81     .09       0 1387.69     .05       0
 1424.51     .09       0 2781.01     .04       0
#XS Ineff= 2 , 0
       0                    2000       0
Permanent Ineff=
       F       F
Bank Sta=1387.69,1424.51
XS Rating Curve= 0 ,0
Exp/Cntr=0.3,0.1

Type RM Length L Ch R = 1 ,55622   ,934.31,994.94,987.87
XS GIS Cut Line= 4
 2340537.8760776  713647.4134645 2339817.9462895  713496.4974785
 2338933.8100513  713321.1236249 2338665.1004171   713189.324454
#Sta/Elev= 30
       0  100.13   54.04   93.51  173.57   82.13  215.63   80.15  233.85   80.74
  287.87   78.14   318.8   79.75   346.8   80.01  430.77   77.77  696.12   77.74
  741.33   79.18  828.47   77.65  995.31   78.95 1116.22   77.38  1120.6   75.45
 1131.47   73.65 1143.56   75.38 1147.87   77.64 1260.86   77.36 1295.15   76.28
 1376.21   77.12 1405.36   78.35 1479.57   78.34 1563.96    81.3  1625.7   82.19
 1659.74    85.5 1687.22   87.02 1716.54   87.14 1844.04   91.04 1936.23   92.22
#Mann= 4 ,-1 , 0
       0     .09       0  1120.6     .05       0 1143.56     .09       0
 1659.74     .04       0
Bank Sta=1120.6,1143.56
XS Rating Curve= 0 ,0
Exp/Cntr=0.3,0.1

Type RM Length L Ch R = 1 ,54627   ,1034.8,881.7,813.41
XS GIS Cut Line= 6
 2341669.8366925  713108.8604754 2340778.6853098  712875.1944891
 2340278.8834295   712650.283643 2339670.7911419  712492.0130475
 2339145.3038016   712347.313635 2338189.8650491  712353.7129216
#Sta/Elev= 30
       0  101.31  258.04   94.96  447.27   87.08  608.26   86.07  735.66   81.31
  932.38   82.96  967.77   80.55   998.1   81.71 1025.87   80.22 1181.05   79.95
 1206.53   77.44 1265.06   80.18 1336.28   77.73  1614.3    77.8 1645.51   76.33
 1796.91   76.27 1819.18   74.62 1839.69   73.36 1852.06   74.63 1917.46   77.51
 2031.65    76.8 2041.74   75.34 2075.12   77.71 2467.81   79.27 2578.13   81.26
 2782.35   88.93 2980.89    87.6 3216.14   89.46 3402.55   87.84 3598.22   92.72
#Mann= 4 ,-1 , 0
       0     .09       0 1819.18     .05       0 1852.06     .09       0
 2578.13     .04       0
Bank Sta=1819.18,1852.06
XS Rating Curve= 0 ,0
Exp/Cntr=0.3,0.1

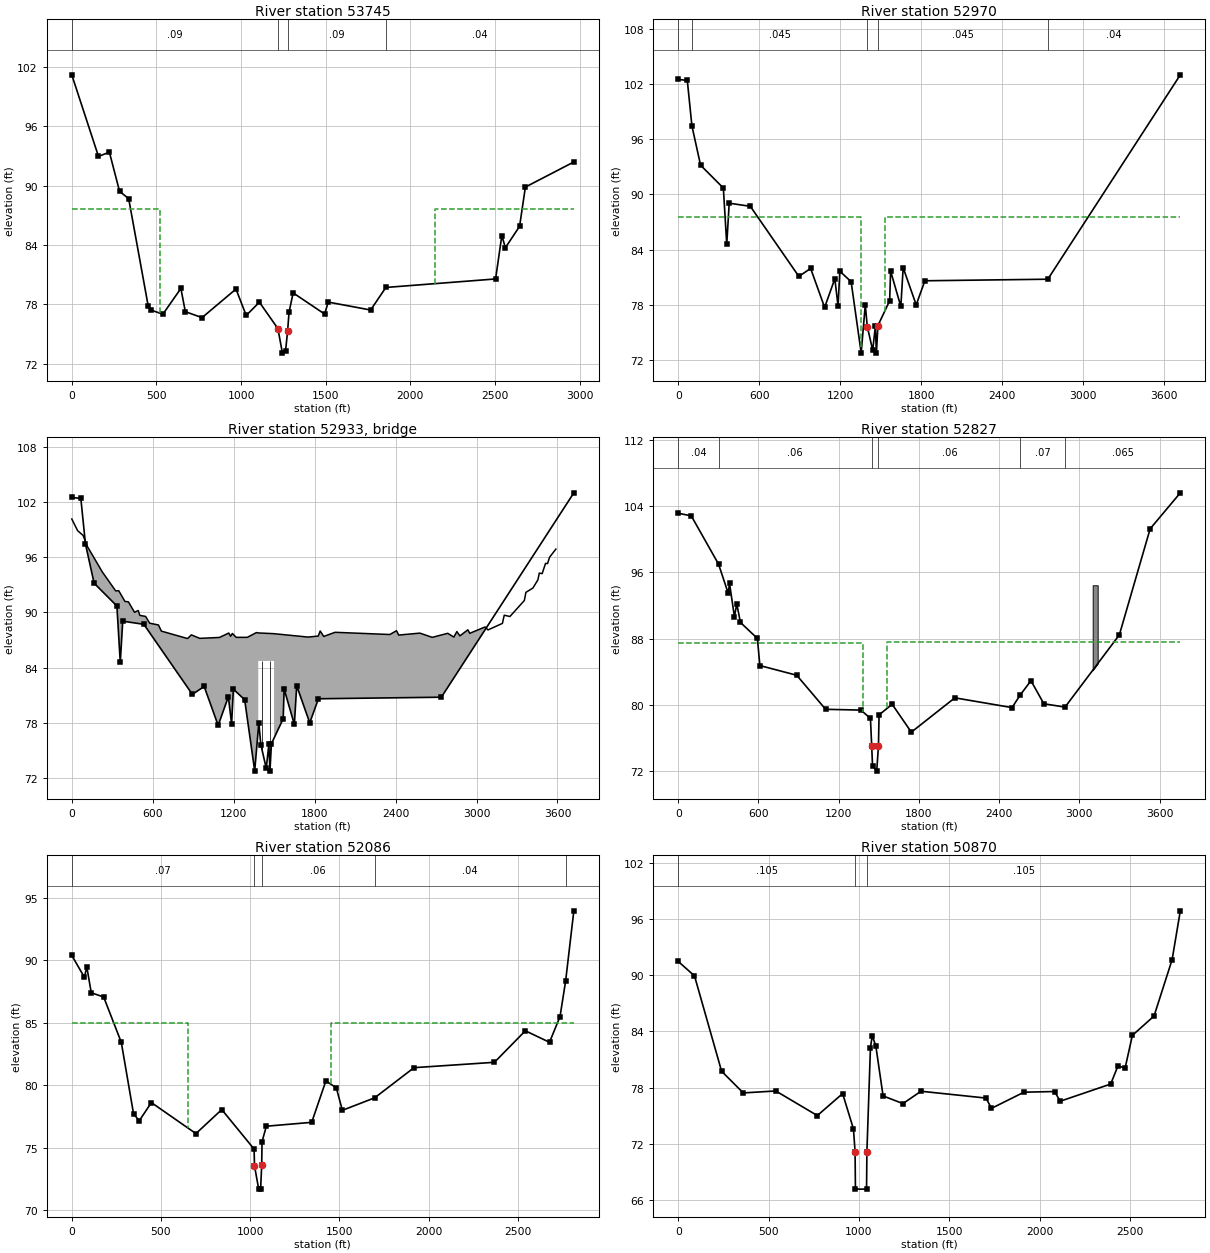
Type RM Length L Ch R = 1 ,53745   ,956.43,775.67,697.73
XS GIS Cut Line= 6
 2341370.1175347  711767.3003212 2340945.2859365  711750.6402585
 2340295.5434922  711700.6600705 2339595.8208598  711708.9901018
 2338814.2458279  711716.5052464 2338413.0498133  711785.2643692
#Sta/Elev= 30
       0   101.2  157.75   92.95  222.14   93.38  282.23   89.42  336.14   88.68
  451.44   77.82   467.9   77.41  538.18      77  644.46    79.6  670.65   77.25
   769.3   76.65  969.88   79.54 1030.25   76.87 1108.16   78.21 1217.48   75.54
 1244.08   73.06 1262.69   73.27 1274.87   75.32 1283.27    77.2 1307.37   79.15
 1493.51   77.01 1514.51   78.22 1765.08   77.42 1855.06    79.7 2503.08   80.56
 2539.89   84.95 2560.94   83.72 2644.75   85.88 2679.04   89.85 2965.25   92.39
#Mann= 4 ,-1 , 0
       0     .09       0 1217.48     .05       0 1274.87     .09       0
 1855.06     .04       0
#XS Ineff= 2 , 0
       0     522    87.6    2144       0    87.6
Permanent Ineff=
       F       F
Bank Sta=1217.48,1274.87
XS Rating Curve= 0 ,0
Exp/Cntr=0.5,0.3

Type RM Length L Ch R = 1 ,52970   ,165.98,142.99,139.26
BEGIN DESCRIPTION:
Surveyed Section
END DESCRIPTION:
XS GIS Cut Line= 6
 2341467.7008736  710620.5080395 2341161.5626308  710627.6275335
 2340755.5085344  710717.2239722    2340044.7966     710957.0819
  2338793.540332  711492.8858196 2337950.6708283  711759.6270825
#Sta/Elev= 30
       0  102.53    67.2  102.42  101.35   97.47  165.52   93.19  334.48    90.7
  359.52   84.56   377.7   89.05  534.19   88.71  893.82   81.08  981.31   81.94
    1085    77.7 1160.55   80.82 1184.65   77.84 1197.66   81.64 1281.35    80.5
1355.836   72.751386.431   77.98 1401.09   75.621441.342   73.031460.881   75.63
1468.803   72.72  1479.9   75.711567.003   78.43 1573.98   81.66 1649.81    77.8
 1667.09   82.02 1763.67   77.98 1828.13    80.6 2739.19   80.77 3721.22  103.03
#Mann= 5 ,-1 , 0
       0     .04       0  101.35    .045       0 1401.09    .055       0
  1479.9    .045       0 2739.19     .04       0
#XS Ineff= 2 , 0
       0    1353    87.6    1529       0    87.6
Permanent Ineff=
       F       F
Bank Sta=1401.09,1479.9
XS Rating Curve= 0 ,0
Exp/Cntr=0.5,0.3

Type RM Length L Ch R = 3 ,52933   ,,,
BEGIN DESCRIPTION:
RT 91
END DESCRIPTION:
Bridge Culvert--1,0,-1,-1, 0
Deck Dist Width WeirC Skew NumUp NumDn MinLoCord MaxHiCord MaxSubmerge Is_Ogee
19.94,29.61,2.6,0, 60, 60, , , 0.95, 0, 1,1,,
       0    43.3   83.99  114.36  225.64  325.39  348.07  394.21  419.82  464.94
  492.46  504.68  547.32  577.36  642.49  663.99  858.06  886.17   948.4  1095.3
 1163.58  1176.7 1190.12 1219.09 1300.71 1368.76 1382.34 1499.341511.002 1751.56
  1826.6 1841.15 1867.43 1951.39  2357.5 2406.72 2422.87 2580.02 2671.68 2786.49
 2831.61 2854.17 2876.71 2935.57 2949.73 3062.72 3085.18 3191.88 3205.24 3247.42
 3354.27 3365.93 3417.75 3455.02 3465.17 3486.35 3511.62 3526.19 3541.55    3588
  100.18   98.91   98.39   97.22   94.43   92.35   92.37    91.2   91.16   90.02
   90.21   89.68   89.57   88.83   88.64   87.97   87.16   87.56   87.18   87.28
   87.76   87.41   87.71   87.29   87.29   87.81   87.77   87.69   87.67   87.32
   87.43   87.98   87.39   87.84    87.6   88.01   87.54   87.75   87.29   87.73
   87.32   87.92   87.45   88.11   87.73   88.42    88.1   88.81    89.7   89.56
    91.3   92.19   92.66   93.56   94.29   94.23   95.35   95.32   96.02    96.9
                                                                                
                                                                                
                                                   84.72   84.72
                                                                                
                                                                                
                                                                                
       0    43.3   83.99  114.36  225.64  325.39  348.07  394.21  419.82  464.94
  492.46  504.68  547.32  577.36  642.49  663.99  858.06  886.17   948.4  981.05
  1095.3 1163.58  1176.7 1190.12 1219.09 1300.71 1383.61 1415.35 1532.351572.967
 1825.09 1841.15 1867.43 1951.39  2357.5 2406.72 2422.87 2580.02 2671.68 2786.49
 2831.61 2854.17 2876.71 2935.57 2949.73 3062.72 3085.18 3191.88 3205.24 3247.42
 3354.27 3365.93 3417.75 3455.02 3465.17 3486.35 3511.62 3526.19 3541.55    3588
  100.18   98.91   98.39   97.22   94.43   92.35   92.37    91.2   91.16   90.02
   90.21   89.68   89.57   88.83   88.64   87.97   87.16   87.56   87.18   87.58
   87.28   87.76   87.41   87.71   87.29   87.29   87.77   87.72   87.67   87.61
   87.42   87.98   87.39   87.84    87.6   88.01   87.54   87.75   87.29   87.73
   87.32   87.92   87.45   88.11   87.73   88.42    88.1   88.81    89.7   89.56
    91.3   92.19   92.66   93.56   94.29   94.23   95.35   95.32   96.02    96.9
                                                                                
                                                                                
                                                           84.69   84.69
                                                                                
                                                                                
                                                                                
Pier Skew, UpSta & Num, DnSta & Num=  ,1411, 2 ,1441, 2 , 0 , 0 , 0 ,,
     2.5     2.5
   72.72   84.72
     2.5     2.5
   72.72   84.72
Pier Skew, UpSta & Num, DnSta & Num=  ,1471, 2 ,1501, 2 , 0 , 0 , 0 ,,
     2.5     2.5
   72.72   84.72
     2.5     2.5
   72.72   84.72
Abutment Skew #Up #Dn= , 2 , 2
 1382.34 1403.34
   83.22   72.26
 1415.35 1436.85
   83.19   72.26
Abutment Skew #Up #Dn= , 2 , 2
 1474.34 1499.34
   71.98   83.22
 1507.35 1532.35
   71.88   83.22
BR Coef=-1 , 1 , 0 ,1.25, 0 ,,,0.8,0,2,0,
WSPro=,,,, 1 ,,,, 0 ,,,, 0 ,,,,-1 ,-1 ,-1 , 0 , 0 , 0 , 0 , 0
BC Design=,, 0 ,, 0 ,,,,,,
BC Use User HTab Curves=0
BC User HTab FreeFlow(D)= 0

Type RM Length L Ch R = 1 ,52827   ,559.18,740.42,885.78
BEGIN DESCRIPTION:
Surveyed Section
END DESCRIPTION:
XS GIS Cut Line= 6
 2341467.7008736  710485.2376531 2340897.2823958  710518.3363412
 2340594.0585571  710597.8913803 2340204.4727423  710727.7533185
 2338413.8961469  711475.7238924 2337915.0733582  711610.1177081
#Sta/Elev= 30
       0  103.15   97.28  102.84  301.53      97  373.53   93.49  383.64   94.67
  420.39   90.64  437.74    92.2  465.12   89.95  592.17   88.02  610.52   84.74
  886.05   83.57  1102.5   79.45  1365.6   79.361437.604   78.36 1446.91   74.98
1453.155   72.641484.353   71.98  1497.5   75.031501.974   78.78 1600.01   80.06
 1743.38   76.69 2068.86   80.84 2496.41   79.66 2557.58   81.18 2638.09   82.91
 2734.53   80.12  2892.9   79.72 3299.15   88.45 3529.39  101.27 3755.07  105.62
#Mann= 6 ,-1 , 0
       0     .04       0  301.53     .06       0 1446.91    .045       0
  1497.5     .06       0 2557.58     .07       0  2892.9    .065       0
#XS Ineff= 2 , 0
       0    1385   87.47    1562       0   87.61
Permanent Ineff=
       F       F
#Block Obstruct= 1 ,-1
 3099.71 3137.03  94.446
Bank Sta=1446.91,1497.5
XS Rating Curve= 0 ,0
Exp/Cntr=0.5,0.3

Type RM Length L Ch R = 1 ,52086   ,1567,1216,1010
XS GIS Cut Line= 5
 2340978.6060619  710192.9243985 2340303.8735235  710109.6240851
 2339679.1211732  710067.9739284 2339137.6691363  710101.2940537
 2338263.0158459  710509.4655893
#Sta/Elev= 30
       0   90.38   71.04   88.62   84.06   89.47  109.23   87.39   178.8   87.05
  277.61   83.42   346.1   77.72  377.96   77.15  446.13   78.61  695.89   76.13
  840.63   78.05  1021.8   74.89 1024.02   73.55 1047.56   71.69  1058.4   71.72
 1064.27   73.59 1066.34   75.49 1090.49   76.72 1344.61   77.03 1423.96   80.34
 1482.65   79.79  1516.3   77.99 1697.49   78.99 1917.96    81.4 2368.75   81.83
 2541.91   84.35 2677.26   83.43 2736.28   85.49 2767.53   88.32 2813.68   93.94
#Mann= 5 ,-1 , 0
       0     .07       0 1024.02    .045       0 1064.27     .06       0
 1697.49     .04       0 2767.53     .09       0
#XS Ineff= 2 , 0
       0     650      85    1450       0      85
Permanent Ineff=
       F       F
Bank Sta=1024.02,1064.27
XS Rating Curve= 0 ,0
Exp/Cntr=0.3,0.1

Type RM Length L Ch R = 1 ,50870   ,1431.4,1431.4,1431.4
BEGIN DESCRIPTION:
LDS
END DESCRIPTION:
XS GIS Cut Line= 5
2341149.03266805709238.8983976722340123.94938035708920.562321965
2340089.74339583708909.6292500392340055.53741131708898.696178114
2338207.88358789708445.857624285
#Sta/Elev= 30
       0   91.47      90   89.93     240   79.74     360   77.42     540   77.63
     770      75     910   77.35     970   73.57   978.9   71.14   980.9   67.14
  1042.4   67.14  1044.4   71.14  1063.9   82.22  1073.9   83.54  1093.9   82.43
  1133.9    77.1  1243.9   76.28  1343.9    77.6  1703.9   76.87  1733.9   75.77
  1913.9    77.5  2083.9   77.57  2113.9   76.53  2393.9   78.37  2433.9    80.3
  2473.9   80.09  2513.9   83.57  2633.9   85.64  2733.9   91.66  2779.3   96.88
#Mann= 3 ,-1 , 0
       0    .105       0   978.9    .041       0  1044.4    .105       0
Bank Sta=978.9,1044.4
XS Rating Curve= 0 ,0
Exp/Cntr=0.3,0.1
Stream Node=Toisnot Swamp   ,Upstream        , 0 , 0 ,Upstream end
Stream Node=Toisnot Swamp   ,Upstream        , 0 , 1 ,Downstream end

Chan Stop Cuts=-1
Use User Specified Reach Order=0
User Specified Reach Order=Toisnot Swamp   ,Upstream