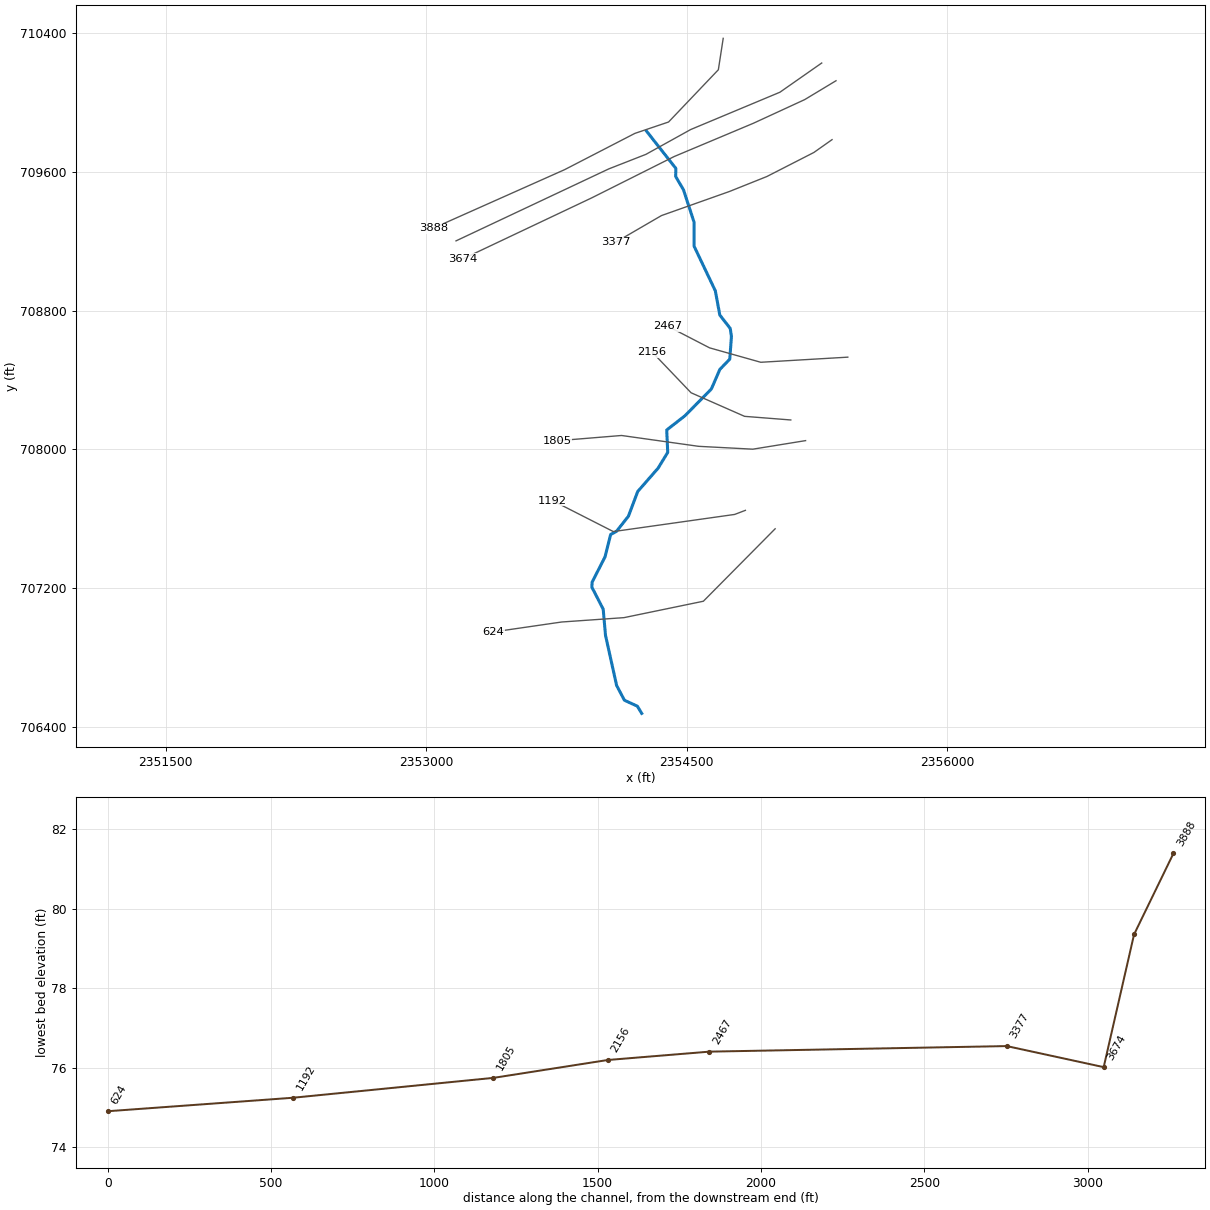
--- DTL_Whiteoak_Swamp_Trib.prj (project) ---

Proj Title=DTL_Whiteoak_Swamp_Trib
Current Plan=p02
Default Exp/Contr=0.3,0.1
English Units
Geom File=g01
Flow File=f02
Flow File=f01
Plan File=p02
Plan File=p01
Y Axis Title=Elevation
X Axis Title(PF)=Main Channel Distance
X Axis Title(XS)=Station
BEGIN DESCRIPTION:
END DESCRIPTION:
DSS Export Rating Curves= 0
DSS Export Rating Curve Sorted= 0
DSS Export Volume Flow Curves= 0
DXF OffsetX= 0
DXF OffsetY= 0
DXF ScaleX= 1
DXF ScaleY= 10

--- DTL_Whiteoak_Swamp_Trib.p02 (plan) ---

Plan Title=DTL_Whiteoak_Swamp_Trib_Future
Program Version=4.00
Short Identifier=Future Flows
Geom File=g01
Flow File=f02
Subcritical Flow
K Sum by GR= 0
Std Step Tol= 0.01
Critical Tol= 0.01
Num of Std Step Trials= 20
Max Error Tol= 0.3
Flow Tol Ratio= 0.001
Split Flow NTrial= 30
Split Flow Tol= 0.02
Split Flow Ratio= 0.02
Log Output Level= 0
Friction Slope Method= 1
Unsteady Friction Slope Method= 2
Unsteady Bridges Friction Slope Method= 1
Parabolic Critical Depth
Global Vel Dist= 0 , 0 , 0
Global Log Level= 0
CheckData=True
Encroach Param=-1 ,10,10, 2
Computation Interval=1HOUR
Output Interval=1HOUR
Run HTab= 0
Run UNet= 0
Run PostProcess= 0
Run WQNet= 0
UNET Theta= 1
UNET Theta Warmup= 1
UNET ZTol= 0.02
UNET ZSATol= 0.05
UNET MxIter= 20
UNET MaxInSteps= 0
UNET DtIC= 0
UNET DtMin= 0
UNET MaxCRTS= 20
UNET WFStab= 2
UNET SFStab= 1
UNET WFX= 1
UNET SFX= 1
UNET DSS MLevel= 4
UNET DZMax Abort= 100
UNET Convert EG Bridges= 0
UNET Use Existing IB Tables=-1
UNET Froude Reduction=False
UNET Froude Limit= 1
UNET Froude Power= 10
UNET Time Slicing=0,0, 5
Instantaneous Interval=1HOUR
Write IC File= 0
Echo Input=False
Echo Output=False
Write Detailed= 0
Detailed Automatic Start=False, 10
WQ ULTIMATE=-1
WQ Max Comp Step=1HOUR
WQ Output Interval=15MIN
WQ Output Selected Increments= 0
WQ Output face flow=0
WQ Output face velocity=0
WQ Output face area=0
WQ Output face dispersion=0
WQ Output cell volume=0
WQ Output cell surface area=0
WQ Output cell continuity=0
WQ Output face conc=0
WQ Output face dconc_dx=0
WQ Output face courant=0
WQ Output face peclet=0
WQ Output face adv mass=0
WQ Output face disp mass=0
WQ Output cell mass=0
WQ Output cell source sink temp=0
WQ Output cell source sink nsm=0
WQ Output MaxMinRange=-1
WQ Daily Max Min Mean=-1
WQ Daily Range=0
WQ Daily Time=0
WQ Create Restart=0
WQ Fixed Restart=0
WQ System Summary=False
Sorting and Armoring Iterations= 10
XS Update Threshold= 0.02
Hydraulics Update Threshold= 0.02
Energy Slope Method= 1
Volume Change Method= 0
XS Weighting Method= 0
Number of US Weighted Cross Sections= 1
Number of DS Weighted Cross Sections= 1
Upstream XS Weight=0.25
Main XS Weight=0.5
Downstream XS Weight=0.25
Number of DS XS's Weighted with US Boundary= 1
Upstream Boundary Weight= 1
Weight of XSs Associated with US Boundary= 0
Number of US XS's Weighted with DS Boundary= 1
Downstream Boundary Weight= 0.5
Weight of XSs Associated with DS Boundary= 0.5
Sediment Output Level= 4
Mass or Volume Output= 0
Output Increment Type= 1
Profile and TS Output Increment= 10
XS Output Flag= 0
XS Output Increment= 10
Disregard all LS=0
Disregard all Conn=0
Disregard all Breaches=0
Disregard all Pumps=0

--- DTL_Whiteoak_Swamp_Trib.p01 (plan) ---

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Plan Title=DTL_Whiteoak_Swamp_Trib
Short Identifier=Multiple
Geom File=g01
Flow File=f01
Encroach River=Whiteoak Swamp
Encroach Reach=Trib
Encroach Node=3888
       1     709     760
Encroach Node=3767
       1    1028    1071
Encroach Node=3674
       1    1033    1076
Encroach Node=3377
       1     879     933
Encroach Node=2467
       1     636     769
Encroach Node=2156
       1     480     553
Encroach Node=1805
       1     765     902
Encroach Node=1192
       4       1
Encroach Node=624
       4       1
UNET Convert EG Bridges=-1

--- DTL_Whiteoak_Swamp_Trib.f02 (steady flow) ---

Flow Title=DTL_Whiteoak_Swamp_Trib_Future
Program Version=4.00
Number of Profiles= 3
Profile Names=100-yr-10%,100-yr-20%,100-yr-35%
River Rch & RM=Whiteoak Swamp,Trib            ,3888
    1420    1820    2220
Boundary for River Rch & Prof#=Whiteoak Swamp,Trib            , 1
Up Type= 0
Dn Type= 3
Dn Slope=5.985916E-04
Boundary for River Rch & Prof#=Whiteoak Swamp,Trib            , 2
Up Type= 0
Dn Type= 3
Dn Slope=5.985916E-04
Boundary for River Rch & Prof#=Whiteoak Swamp,Trib            , 3
Up Type= 0
Dn Type= 3
Dn Slope=5.985916E-04
DSS Import GetInterval= 0
DSS Import GetPeak= 0
DSS Import FillOption= 0

--- DTL_Whiteoak_Swamp_Trib.f01 (steady flow) ---

Flow Title=DTL_Whiteoak_Swamp_Trib
Program Version=4.00
Number of Profiles= 6
Profile Names=100-yr,FW,10-yr,25-yr,50-yr,500-yr
River Rch & RM=Whiteoak Swamp,Trib            ,3888
     820     820     340     500     650    1310
Boundary for River Rch & Prof#=Whiteoak Swamp,Trib            , 1
Up Type= 0
Dn Type= 3
Dn Slope=5.985916E-04
Boundary for River Rch & Prof#=Whiteoak Swamp,Trib            , 2
Up Type= 0
Dn Type= 3
Dn Slope=5.985916E-04
Boundary for River Rch & Prof#=Whiteoak Swamp,Trib            , 3
Up Type= 0
Dn Type= 3
Dn Slope=5.985916E-04
Boundary for River Rch & Prof#=Whiteoak Swamp,Trib            , 4
Up Type= 0
Dn Type= 3
Dn Slope=5.985916E-04
Boundary for River Rch & Prof#=Whiteoak Swamp,Trib            , 5
Up Type= 0
Dn Type= 3
Dn Slope=5.985916E-04
Boundary for River Rch & Prof#=Whiteoak Swamp,Trib            , 6
Up Type= 0
Dn Type= 3
Dn Slope=5.985916E-04
DSS Import GetInterval= 0
DSS Import GetPeak= 0
DSS Import FillOption= 0

--- DTL_Whiteoak_Swamp_Trib.g01 (geometry) ---

Geom Title=DTL_Whiteoak_Swamp_Trib
Program Version=4.00

River Reach=Whiteoak Swamp  ,Trib
Reach XY= 30
 2354268.2634235  709832.4042706 2354437.1361644  709617.9454415
 2354436.1813033   709571.157247 2354481.0597755  709494.7683582
 2354542.1708866  709307.6155804 2354542.1708866  709170.1155804
 2354664.3931088  708913.2579415 2354690.1743588  708773.8482193
 2354750.3306088  708696.5044693 2354757.0146366  708649.7162748
 2354747.4660255  708519.8551637 2354690.1743588  708460.6537748
 2354641.4764422  708347.9801637 2354489.6535255  708194.2475248
 2354384.6188033  708112.1294693   2354390.34797  707983.2232193
 2354334.9660255  707892.5114137 2354217.5181088   707757.875997
 2354164.0458866  707615.6016915 2354095.2958866  707528.7093304
 2354061.8757477  707510.5669693 2354029.4104699  707381.6607193
 2353954.9313032  707235.5669692 2353953.9764421  707206.9211359
 2354018.9069977  707080.8794692 2354032.2750533  706930.0114137
 2354096.2507477  706641.6433582 2354141.1292199  706556.6607192
 2354215.6083866  706522.2857193  2354240.651731  706480.9817104

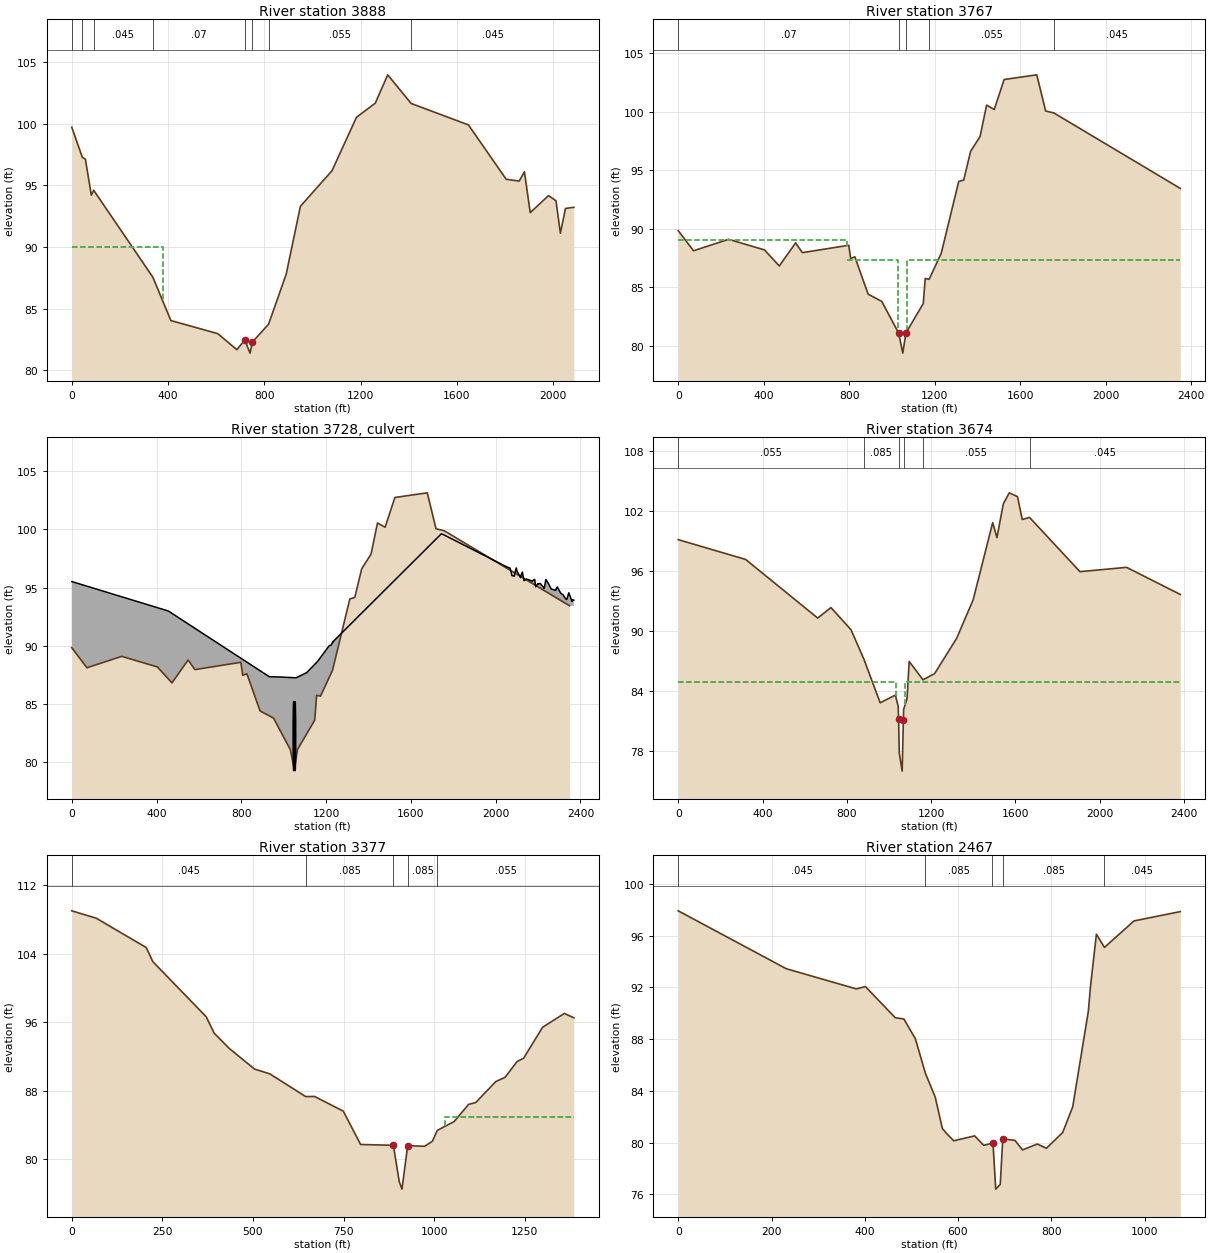
Type RM Length L Ch R = 1 ,3888    ,97.54,120.61,135.16
XS GIS Cut Line= 6
 2354709.7582872  710366.6603621 2354681.8171119  710185.8454078
 2354395.2079125  709885.0271485 2354201.4586846  709819.6017016
 2353796.6771121  709610.6269637  2353041.495648  709274.0787025
#Sta/Elev= 30
       0    99.7   43.81   97.27   56.65   97.11   81.28   94.19   91.17   94.59
  337.16   87.54   411.8   84.03  606.78   82.97  686.01   81.67  719.17   82.46
   740.8   81.39  750.67   82.29  817.65   83.73  891.09   87.79  950.07   93.29
 1081.52   96.18  1183.1  100.51 1261.16  101.65 1312.89  103.95 1410.17  101.63
  1648.4   99.89 1805.43   95.48 1859.45   95.34 1881.06   96.09 1905.17   92.78
 1981.15   94.16 2012.23   93.74 2030.46   91.11 2051.68   93.12 2086.36   93.21
#Mann= 8 ,-1 , 0
       0    .045       0   43.81     .07       0   91.17    .045       0
  337.16     .07       0  719.17     .05       0  750.67     .07       0
  817.65    .055       0 1410.17    .045       0
#XS Ineff= 2 , 0
       0     380      90               0
Permanent Ineff=
       F       F
Bank Sta=719.17,750.67
XS Rating Curve= 0 ,0
Exp/Cntr=0.5,0.3

Type RM Length L Ch R = 1 ,3767    ,102.73,92.98,87.58
BEGIN DESCRIPTION:
Surveyed Section
END DESCRIPTION:
XS GIS Cut Line= 6
 2355276.8178573  710224.6619789 2355036.2469474   710056.495906
  2354522.406169   709841.617035     2354264.966     709698.8789
 2354051.0682412  709615.0937301 2353171.7588539  709200.7782412
#Sta/Elev= 30
       0   89.82   71.54    88.1  235.68   89.08  403.71   88.17  472.71    86.8
  548.99   88.77  580.73   87.94  797.73   88.57  806.45   87.45  826.25   87.58
  888.29   84.39   952.1   83.771030.938   81.071050.337   79.351065.014   81.07
1146.212   83.59  1155.3   85.73 1173.57   85.66 1230.26   87.88 1311.98   94.02
 1335.23   94.14 1367.91   96.61 1411.96   97.87 1442.47  100.55 1478.31  100.18
 1524.47  102.74 1677.24  103.14 1718.56  100.05 1757.18   99.88 2348.55   93.43
#Mann= 5 ,-1 , 0
       0     .07       01030.938     .05       01065.014     .07       0
 1173.57    .055       0 1757.18    .045       0
#XS Ineff= 3 ,-1
       0     788      89     788    1028   87.31 1071.03 2348.55   87.31
Permanent Ineff=
       F       F       F
Bank Sta=1030.938,1065.014
XS Rating Curve= 0 ,0
Exp/Cntr=0.5,0.3

Type RM Length L Ch R = 2 ,3728    ,,,
BEGIN DESCRIPTION:
Ethridge Rd
END DESCRIPTION:
Bridge Culvert--1,0,-1,-1, 0
Deck Dist Width WeirC Skew NumUp NumDn MinLoCord MaxHiCord MaxSubmerge Is_Ogee
21.25,35,2.6,0, 66, 66, , , 0.95, 0, 1,1,,
       0     .29  455.69 931.845 980.1911030.3531058.6631108.1031158.926 1214.78
 1223.93 1231.18 1231.86 1233.51 1743.15 1752.05 2057.26 2061.92 2067.84 2076.73
 2088.26 2090.09 2097.47 2100.69 2117.49 2118.88 2125.87 2133.67 2145.83 2146.38
 2147.38  2156.1 2172.99 2173.36 2184.15 2188.75 2199.44 2200.45  2200.9 2209.14
 2210.49 2216.06  2225.4 2228.58 2230.88 2236.66 2247.73 2258.75 2262.21 2276.27
 2278.64 2281.68 2284.26 2290.34  2301.6 2307.89 2317.23 2331.58 2333.05 2334.61
  2336.4 2344.94 2358.67 2360.88 2362.63 2368.79
   95.51   95.51   92.98   87.33   87.31   87.26   87.24   87.68   88.63      90
   90.05   90.31   90.29   90.36   99.61   99.56   96.73   96.71   96.66   96.03
   95.98   96.22   96.68   96.41   95.85   96.02   96.33   95.59   95.73   95.72
    95.7   95.67   95.54   95.58    95.7   95.06   95.33    95.3   95.32   95.34
   95.34   95.22   95.02   94.92   95.08   95.69   95.39   94.98   94.87   94.79
   94.79   94.75   94.81   95.05   94.68    94.5   94.39   93.99   93.99   93.97
   94.02   94.55   93.88    93.8   93.94   93.91
                                                                                
                                                                                
                                                                                
                                                                                
                                                                                
                                                                                
                                                
       0     .29  455.69 931.845 980.1911030.3531058.6631108.1031158.926 1214.78
 1223.93 1231.18 1231.86 1233.51 1743.15 1752.05 2057.26 2061.92 2067.84 2076.73
 2088.26 2090.09 2097.47 2100.69 2117.49 2118.88 2125.87 2133.67 2145.83 2146.38
 2147.38  2156.1 2172.99 2173.36 2184.15 2188.75 2199.44 2200.45  2200.9 2209.14
 2210.49 2216.06  2225.4 2228.58 2230.88 2236.66 2247.73 2258.75 2262.21 2276.27
 2278.64 2281.68 2284.26 2290.34  2301.6 2307.89 2317.23 2331.58 2333.05 2334.61
  2336.4 2344.94 2358.67 2360.88 2362.63 2368.79
   95.51   95.51   92.98   87.33   87.31   87.26   87.24   87.68   88.63      90
   90.05   90.31   90.29   90.36   99.61   99.56   96.73   96.71   96.66   96.03
   95.98   96.22   96.68   96.41   95.85   96.02   96.33   95.59   95.73   95.72
    95.7   95.67   95.54   95.58    95.7   95.06   95.33    95.3   95.32   95.34
   95.34   95.22   95.02   94.92   95.08   95.69   95.39   94.98   94.87   94.79
   94.79   94.75   94.81   95.05   94.68    94.5   94.39   93.99   93.99   93.97
   94.02   94.55   93.88    93.8   93.94   93.91
                                                                                
                                                                                
                                                                                
                                                                                
                                                                                
                                                                                
                                                
BR Coef=-1 , 0 , 0 ,, 0 ,,,0.8,-1,,0,
WSPro=,,,, 1 ,,,, 0 ,,,, 0 ,,,,-1 ,-1 ,-1 , 0 , 0 , 0 , 0 , 0
Multiple Barrel Culv=1,6,,60.94,0.026,0.9,1,2,3,79.2136,78.9422, 2,Culvert #1  , 0 ,9.1
1046.8881051.3641053.8881058.364
Culvert Bottom n=0.026
BC Design=,, 0 ,, 0 ,,,,,,
BC Use User HTab Curves=0
BC User HTab FreeFlow(D)= 0

Type RM Length L Ch R = 1 ,3674    ,298.35,296.81,275.71
BEGIN DESCRIPTION:
Surveyed Section
END DESCRIPTION:
XS GIS Cut Line= 6
 2355358.9844176  710122.5035302 2355178.9105766  710013.9974978
 2354883.4047863  709877.7877976    2354427.6475     709686.3311
 2353953.0232747  709448.3809461 2353211.9501599  709097.4678201
#Sta/Elev= 30
       0   99.15  319.87   97.17  661.84   91.31  724.75   92.36  820.02   90.14
  881.03    87.2  958.27   82.841030.273   83.611043.775   82.491045.674   81.18
1048.835   77.821062.661   76.011068.209   81.081069.475   82.161085.622   83.23
1096.014   86.97 1161.45   85.14 1216.61   85.76 1321.08   89.28 1399.51   93.14
 1492.16  100.85 1512.42   99.35 1542.51  102.72  1570.9  103.83  1609.9  103.45
 1632.51  101.16 1667.01  101.37 1906.35   95.95  2127.6   96.38 2382.46   93.67
#Mann= 6 ,-1 , 0
       0    .055       0  881.03    .085       01045.674     .05       0
1069.475    .085       0 1161.45    .055       0 1667.01    .045       0
#XS Ineff= 2 , 0
       0    1033    84.9    1076       0    84.9
Permanent Ineff=
       F       F
Bank Sta=1045.674,1068.209
XS Rating Curve= 0 ,0
Exp/Cntr=0.5,0.3

Type RM Length L Ch R = 1 ,3377    ,935.42,910.46,845.56
XS GIS Cut Line= 6
 2355336.2828009  709783.5183723 2355231.6245001  709709.6419247
 2354960.7441924  709571.1235855 2354745.2712203  709484.9343967
 2354354.3416852  709346.4160575  2354089.617748  709192.5067917
#Sta/Elev= 30
       0  109.01   67.51  108.15  205.74  104.72  223.53  103.09   370.9   96.65
  392.91   94.74  434.87   92.94  504.67   90.54   546.5   89.99  645.31   87.34
  669.97   87.35  749.22   85.64  796.97   81.75   887.5   81.65  903.59   77.42
  911.13   76.54  926.82   81.61  973.65   81.54  994.86   82.12 1008.83    83.4
 1054.95   84.42    1095   86.43 1114.65   86.64 1169.99   89.09  1195.6   89.58
 1228.57   91.42 1246.71   91.81 1299.33   95.43 1359.23   97.04 1385.38   96.53
#Mann= 5 ,-1 , 0
       0    .045       0  645.31    .085       0   887.5     .05       0
  926.82    .085       0 1008.83    .055       0
#XS Ineff= 2 , 0
       0                    1030       0      85
Permanent Ineff=
       F       F
Bank Sta=887.5,926.82
XS Rating Curve= 0 ,0
Exp/Cntr=0.3,0.1

Type RM Length L Ch R = 1 ,2467    ,317.6,311,291.64
XS GIS Cut Line= 4
 2355427.0470126  708531.4682294 2354925.9900003  708501.9942875
 2354631.2505813  708585.0572147 2354392.7795969  708708.3118808
#Sta/Elev= 30
       0   97.93  231.71   93.45  381.78   91.89  401.34   92.07  465.39   89.66
  483.87   89.56  508.41   88.04  530.11   85.35  551.08   83.52  566.25    81.1
  573.76   80.77  590.69   80.14  635.54   80.52  655.05   79.79  674.94   79.96
  680.79    76.4  690.48   76.76   695.9   80.29  722.05   80.17  738.19   79.43
   769.9   79.89  789.42   79.56  824.35   80.78  845.89   82.77  879.39   90.16
  884.01   92.09  896.66   96.12  913.91    95.1  977.35   97.15 1076.58   97.87
#Mann= 5 ,-1 , 0
       0    .045       0  530.11    .085       0  673.19     .05       0
   695.9    .085       0  913.91    .045       0
Bank Sta=674.94,695.9
XS Rating Curve= 0 ,0
Exp/Cntr=0.3,0.1

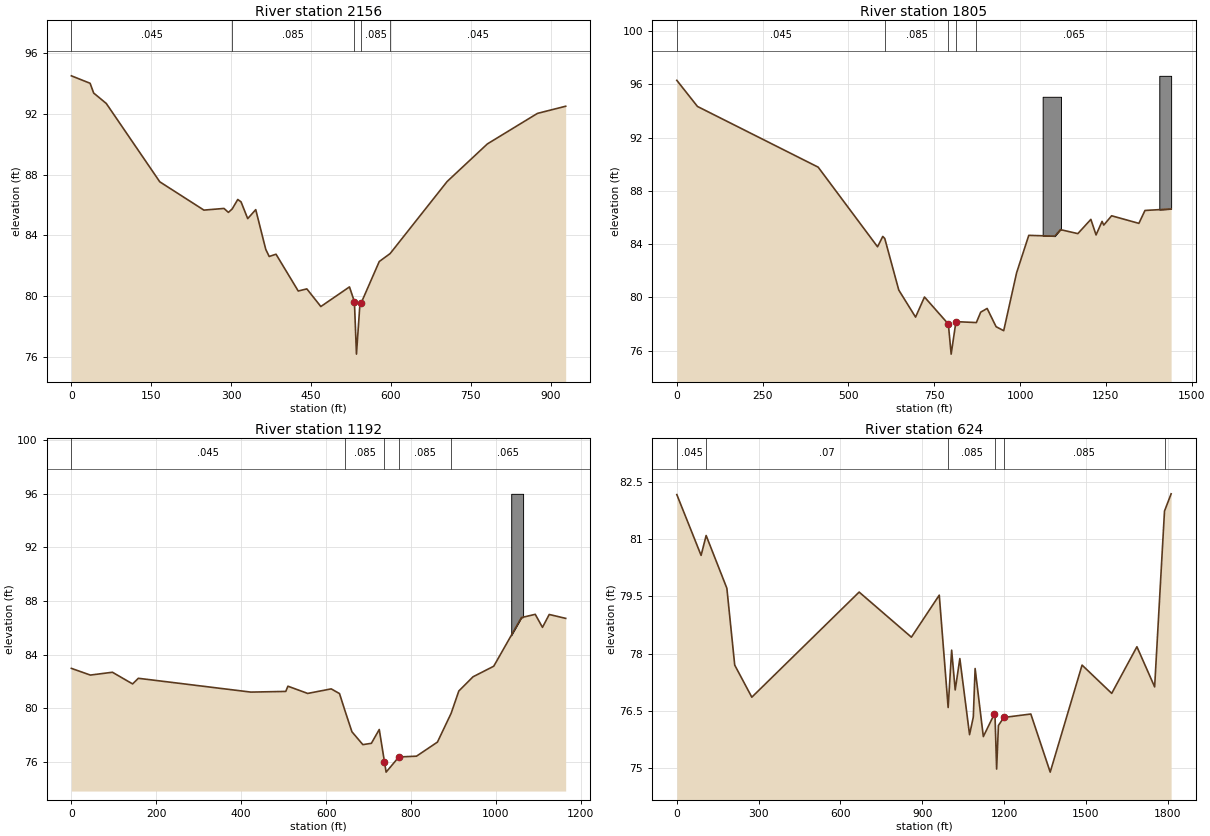
Type RM Length L Ch R = 1 ,2156    ,300.44,350.15,401.18
XS GIS Cut Line= 4
 2355098.8525089  708169.8838431 2354832.7059529  708190.7580828
 2354524.8109177  708326.4406407 2354300.4128411  708561.2758371
#Sta/Elev= 30
       0   94.49   35.16      94   41.84   93.36   65.59   92.67  166.04   87.52
  248.89   85.66  286.56   85.77  294.89   85.51  302.05   85.74  312.48   86.36
  318.66    86.2  331.11    85.1  346.21   85.69  365.01   83.08   371.5   82.61
  384.28   82.76  426.02   80.34  442.16   80.48  468.46   79.32  522.23   80.61
   531.5   79.64  535.34   76.19  541.67   79.38  543.76   79.52  578.18   82.28
  598.53    82.8  705.61   87.54   781.1   90.01  875.23   92.02  928.24   92.49
#Mann= 5 ,-1 , 0
       0    .045       0  302.05    .085       0   531.5     .05       0
  543.76    .085       0  598.53    .045       0
Bank Sta=531.5,543.76
XS Rating Curve= 0 ,0
Exp/Cntr=0.3,0.1

Type RM Length L Ch R = 1 ,1805    ,501.03,613.08,596.01
XS GIS Cut Line= 5
 2355183.9126278  708051.0130704 2354880.1983433  708001.7621054
 2354568.2755646  708018.1790938 2354124.5046303  708080.5710346
 2353753.7171384  708050.2059264
#Sta/Elev= 30
       0    96.3    60.1   94.34  411.89   89.78  584.85    83.8  600.03   84.58
  605.89   84.42  646.69   80.55  695.58   78.52  721.56   80.03   791.1      78
   799.3   75.74  813.28   78.18  872.76   78.11  885.33   78.89  904.13   79.17
   930.2    77.8  952.39    77.5  989.99   81.85 1025.46   84.66 1101.39    84.6
  1117.5   85.09 1168.45   84.79 1206.38   85.86 1221.44   84.69 1239.04   85.71
 1243.87   85.43 1266.82   86.13 1346.25   85.56 1364.07   86.53  1440.2   86.64
#Mann= 5 ,-1 , 0
       0    .045       0  605.89    .085       0   791.1     .05       0
  813.28    .085       0  872.76    .065       0
#Block Obstruct= 2 ,-1
 1065.88 1119.26  95.067  1405.7  1440.2   96.64
Bank Sta=791.1,813.28
XS Rating Curve= 0 ,0
Exp/Cntr=0.3,0.1

Type RM Length L Ch R = 1 ,1192    ,490.2,568.05,691.19
XS GIS Cut Line= 4
 2354837.4856674  707649.6827744 2354775.6401807  707626.1225889
 2354077.3773646  707527.4288538 2353727.2119299  707705.6382147
#Sta/Elev= 30
       0   82.98   44.76   82.48   96.67   82.69  144.21   81.82  157.74   82.24
  422.74   81.21  504.98   81.26  510.05   81.65  556.57   81.11  611.99   81.45
  631.54    81.1  645.37   79.73  660.83   78.25  686.57   77.29  706.62   77.39
  725.18   78.42  737.46   76.01  741.32   75.24  771.34   76.37  812.96   76.43
  862.23   77.48  894.52   79.63  912.57   81.29  945.98   82.35  994.82   83.14
 1060.04   86.77 1092.63   87.01 1109.62   86.04 1125.53      87 1164.29   86.71
#Mann= 5 ,-1 , 0
       0    .045       0  645.37    .085       0  737.46     .05       0
  771.34    .085       0  894.52    .065       0
#Block Obstruct= 1 ,-1
    1036    1064      96
Bank Sta=737.46,771.34
XS Rating Curve= 0 ,0
Exp/Cntr=0.3,0.1

Type RM Length L Ch R = 1 ,624     ,521.67,624.23,790.58
XS GIS Cut Line= 5
 2355008.7291639  707543.4948424 2354595.6144168  707126.5114775
 2354138.6370606  707032.0694905 2353779.7321358  707006.9461458
 2353384.9367186  706949.5213578
#Sta/Elev= 30
       0   82.16   89.01   80.57  107.47   81.09  183.47   79.71  212.26    77.7
  274.93   76.86  668.46   79.61  860.04   78.43   962.2   79.53  994.79   76.59
 1007.61   78.09 1020.63   77.05 1037.69   77.87 1073.28   75.88 1087.02   76.34
 1093.66   77.61 1123.79   75.83 1163.43   76.41 1166.59   76.38 1172.57   74.98
 1179.11   76.12 1199.03   76.33 1297.95   76.42 1369.01    74.9  1485.8    77.7
  1594.5   76.96  1686.9   78.18  1751.9   77.13 1788.06   81.73 1812.34   82.18
#Mann= 6 ,-1 , 0
       0    .045       0  107.47     .07       0  994.79    .085       0
 1166.59     .05       0 1199.03    .085       0 1788.06    .035       0
#XS Ineff= 2 , 0
       0    1093            1433       0
Permanent Ineff=
       F       F
Bank Sta=1163.43,1199.03
XS Rating Curve= 0 ,0
Exp/Cntr=0.3,0.1

Chan Stop Cuts=-1
Use User Specified Reach Order=0
User Specified Reach Order=Whiteoak Swamp  ,Trib