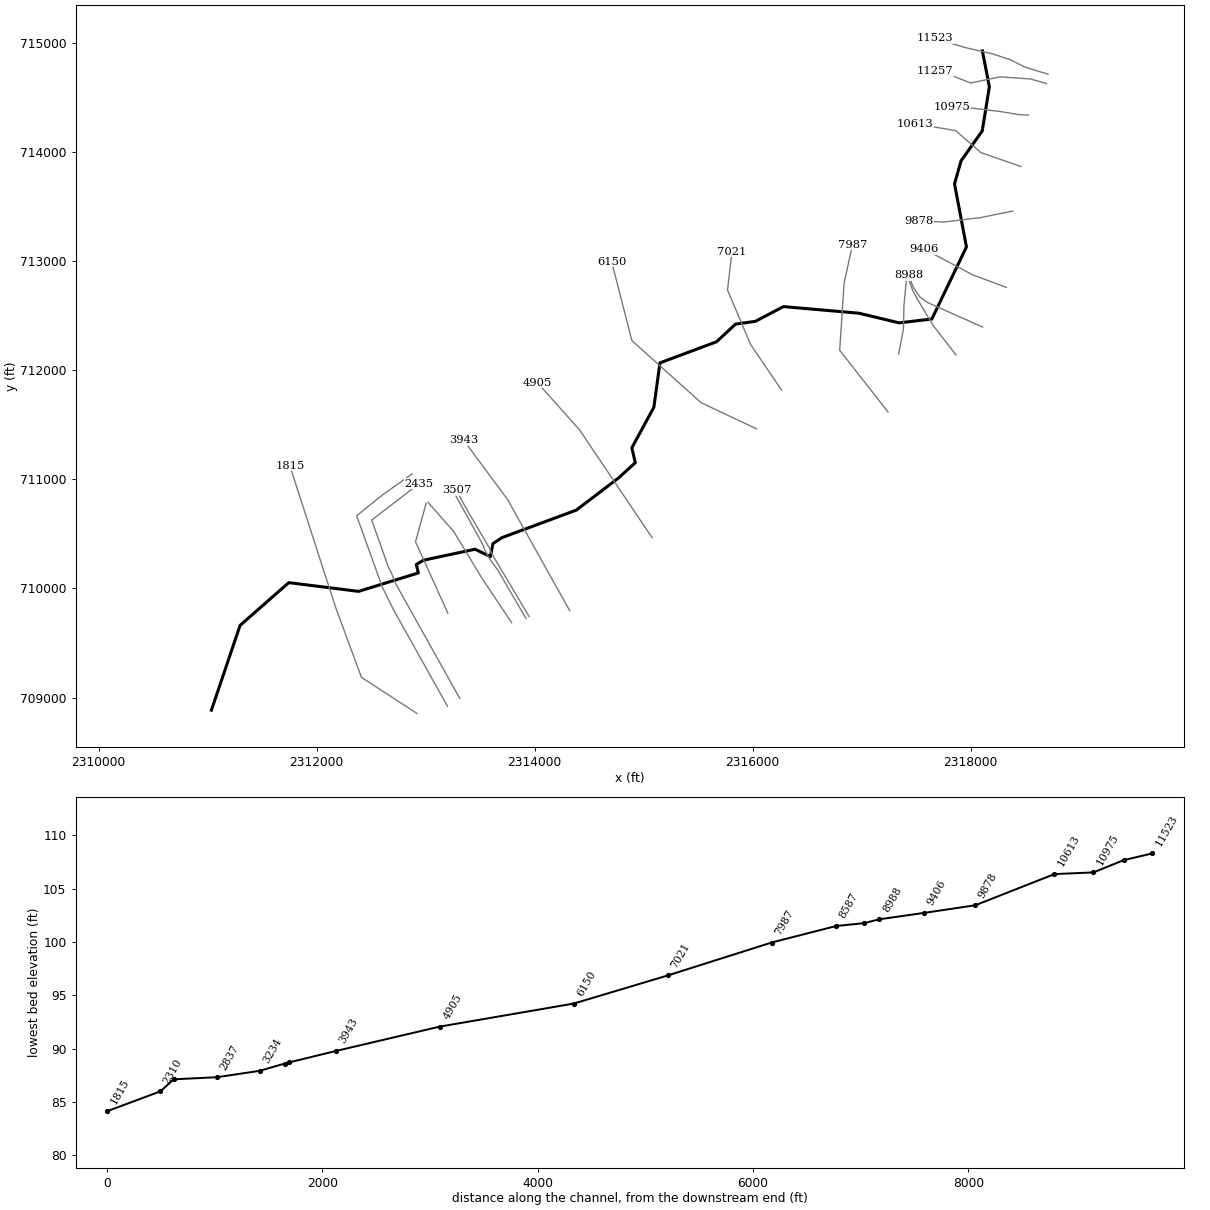
--- DTL_Wiggins_Mil_Trib.prj (project) ---

Proj Title=DTL_Wiggins_Mill_Trib
Current Plan=p04
Default Exp/Contr=0.3,0.1
English Units
Geom File=g01
Flow File=f01
Flow File=f02
Plan File=p02
Plan File=p04
Y Axis Title=Elevation
X Axis Title(PF)=Main Channel Distance
X Axis Title(XS)=Station
BEGIN DESCRIPTION:
END DESCRIPTION:
DSS Export Rating Curves= 0
DSS Export Rating Curve Sorted= 0
DSS Export Volume Flow Curves= 0
DXF OffsetX= 0
DXF OffsetY= 0
DXF ScaleX= 1
DXF ScaleY= 10

--- DTL_Wiggins_Mil_Trib.p04 (plan) ---

Plan Title=DTL_Wiggins_Mill_Trib_Future
Program Version=4.00
Short Identifier=Future
Geom File=g01
Flow File=f02
Subcritical Flow
K Sum by GR= 0
Std Step Tol= 0.01
Critical Tol= 0.01
Num of Std Step Trials= 20
Max Error Tol= 0.3
Flow Tol Ratio= 0.001
Split Flow NTrial= 30
Split Flow Tol= 0.02
Split Flow Ratio= 0.02
Log Output Level= 0
Friction Slope Method= 1
Unsteady Friction Slope Method= 2
Unsteady Bridges Friction Slope Method= 1
Parabolic Critical Depth
Global Vel Dist= 0 , 0 , 0
Global Log Level= 0
CheckData=True
Encroach Param=-1 ,10,10, 2
Computation Interval=1HOUR
Output Interval=1HOUR
Run HTab= 0
Run UNet= 0
Run PostProcess= 0
Run WQNet= 0
UNET Theta= 1
UNET Theta Warmup= 1
UNET ZTol= 0.02
UNET ZSATol= 0.05
UNET MxIter= 20
UNET MaxInSteps= 0
UNET DtIC= 0
UNET DtMin= 0
UNET MaxCRTS= 20
UNET WFStab= 2
UNET SFStab= 1
UNET WFX= 1
UNET SFX= 1
UNET DSS MLevel= 4
UNET DZMax Abort= 100
UNET Convert EG Bridges= 0
UNET Use Existing IB Tables=-1
UNET Froude Reduction=False
UNET Froude Limit= 1
UNET Froude Power= 10
UNET Time Slicing=0,0, 5
Instantaneous Interval=1HOUR
Write IC File= 0
Echo Input=False
Echo Output=False
Write Detailed= 0
Detailed Automatic Start=False, 10
WQ ULTIMATE=-1
WQ Max Comp Step=1HOUR
WQ Output Interval=15MIN
WQ Output Selected Increments= 0
WQ Output face flow=0
WQ Output face velocity=0
WQ Output face area=0
WQ Output face dispersion=0
WQ Output cell volume=0
WQ Output cell surface area=0
WQ Output cell continuity=0
WQ Output face conc=0
WQ Output face dconc_dx=0
WQ Output face courant=0
WQ Output face peclet=0
WQ Output face adv mass=0
WQ Output face disp mass=0
WQ Output cell mass=0
WQ Output cell source sink temp=0
WQ Output cell source sink nsm=0
WQ Output MaxMinRange=-1
WQ Daily Max Min Mean=-1
WQ Daily Range=0
WQ Daily Time=0
WQ Create Restart=0
WQ Fixed Restart=0
WQ System Summary=False
Sorting and Armoring Iterations= 10
XS Update Threshold= 0.02
Hydraulics Update Threshold= 0.02
Energy Slope Method= 1
Volume Change Method= 0
XS Weighting Method= 0
Number of US Weighted Cross Sections= 1
Number of DS Weighted Cross Sections= 1
Upstream XS Weight=0.25
Main XS Weight=0.5
Downstream XS Weight=0.25
Number of DS XS's Weighted with US Boundary= 1
Upstream Boundary Weight= 1
Weight of XSs Associated with US Boundary= 0
Number of US XS's Weighted with DS Boundary= 1
Downstream Boundary Weight= 0.5
Weight of XSs Associated with DS Boundary= 0.5
Sediment Output Level= 4
Mass or Volume Output= 0
Output Increment Type= 1
Profile and TS Output Increment= 10
XS Output Flag= 0
XS Output Increment= 10
Disregard all LS=0
Disregard all Conn=0
Disregard all Breaches=0
Disregard all Pumps=0

--- DTL_Wiggins_Mil_Trib.p02 (plan) ---

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Plan Title=DTL_Wiggins_Mill_Trib
Short Identifier=Multi
Geom File=g01
Flow File=f01
Encroach River=Wiggins Mill
Encroach Reach=Trib
Encroach Node=11523
       4       1
Encroach Node=11257
       1     525     560
Encroach Node=10975
       1     374     408
Encroach Node=10613
       4       1
Encroach Node=9878
       1     439     540
Encroach Node=9406
       1     400     495
Encroach Node=8988
       4       1
Encroach Node=8843
       1     388     418
Encroach Node=8587
       1     255     339
Encroach Node=7987
       1    1016    1111
Encroach Node=7021
       4       1
Encroach Node=6150
       4       1
Encroach Node=4905
       4       1
Encroach Node=3943
       4       1
Encroach Node=3507
       4       1
Encroach Node=3466
       4       1
Encroach Node=3234
       4       1
Encroach Node=2837
       1     460     580
Encroach Node=2435
       1 1213.75    1300
Encroach Node=2310
       1 1239.75    1300
Encroach Node=1815
       1    1330    1552
UNET Convert EG Bridges=-1

--- DTL_Wiggins_Mil_Trib.f02 (steady flow) ---

Flow Title=DTL_Wiggins_Mill_Trib_Future
Program Version=4.00
Number of Profiles= 3
Profile Names=100-yr-10%,100-yr-20%,100-yr-35%
River Rch & RM=Wiggins Mill,Trib            ,11523
    1050    1340    1640
Boundary for River Rch & Prof#=Wiggins Mill,Trib            , 1
Up Type= 0
Dn Type= 3
Dn Slope=2.888889E-03
Boundary for River Rch & Prof#=Wiggins Mill,Trib            , 2
Up Type= 0
Dn Type= 3
Dn Slope=2.888889E-03
Boundary for River Rch & Prof#=Wiggins Mill,Trib            , 3
Up Type= 0
Dn Type= 3
Dn Slope=2.888889E-03
DSS Import GetInterval= 0
DSS Import GetPeak= 0
DSS Import FillOption= 0

--- DTL_Wiggins_Mil_Trib.f01 (steady flow) ---

Flow Title=DTL_Wiggins_Mill_Trib
Program Version=4.00
Number of Profiles= 6
Profile Names=100-yr,FW,10-yr,25-yr,50-yr,500-yr
River Rch & RM=Wiggins Mill,Trib            ,11523
    1480    1480     770    1110    1300    2000
Boundary for River Rch & Prof#=Wiggins Mill,Trib            , 1
Up Type= 0
Dn Type= 3
Dn Slope=2.888889E-03
Boundary for River Rch & Prof#=Wiggins Mill,Trib            , 2
Up Type= 0
Dn Type= 3
Dn Slope=2.888889E-03
Boundary for River Rch & Prof#=Wiggins Mill,Trib            , 3
Up Type= 0
Dn Type= 3
Dn Slope=2.888889E-03
Boundary for River Rch & Prof#=Wiggins Mill,Trib            , 4
Up Type= 0
Dn Type= 3
Dn Slope=2.888889E-03
Boundary for River Rch & Prof#=Wiggins Mill,Trib            , 5
Up Type= 0
Dn Type= 3
Dn Slope=2.888889E-03
Boundary for River Rch & Prof#=Wiggins Mill,Trib            , 6
Up Type= 0
Dn Type= 3
Dn Slope=2.888889E-03
DSS Import GetInterval= 0
DSS Import GetPeak= 0
DSS Import FillOption= 0

--- DTL_Wiggins_Mil_Trib.g01 (geometry) ---

Geom Title=DTL_Wiggins_Mill_Trib
Program Version=4.00

River Reach=Wiggins Mill    ,Trib
Reach XY= 30
2318107.11584082714931.3763592242318170.84552404 714601.86492914
2318105.66743895714197.0366007542317911.58158563  713922.5644425
2317851.47290716713711.8219674382317960.82724991713132.461211219
2317643.62723586712471.9899491672317343.80804452712436.504102826
2316975.18976343712524.8566181662316282.12945879 712585.68949756
2316026.48652512712450.9881217482315842.53948502 712424.91688773
 2315669.4554591712263.4200769222315149.47918043712069.334223598
2315093.71570766 711662.333292352314891.66364394711290.094006494
2314923.52848549711153.9442287832314765.65267943711010.552441627
2314381.82617848710718.6994606852313701.07728994710466.677531734
2313617.81963634710412.172017172    2313594.3794710292.317000002
2313453.65178636710360.0245824752312978.32474656710258.831860468
2312915.31926431710219.7250094122312932.70008703710142.235508278
2312385.20417239709973.4966880232311745.05579934710053.634048864
2311298.26303984709661.5192868262311035.13595451708883.668461815

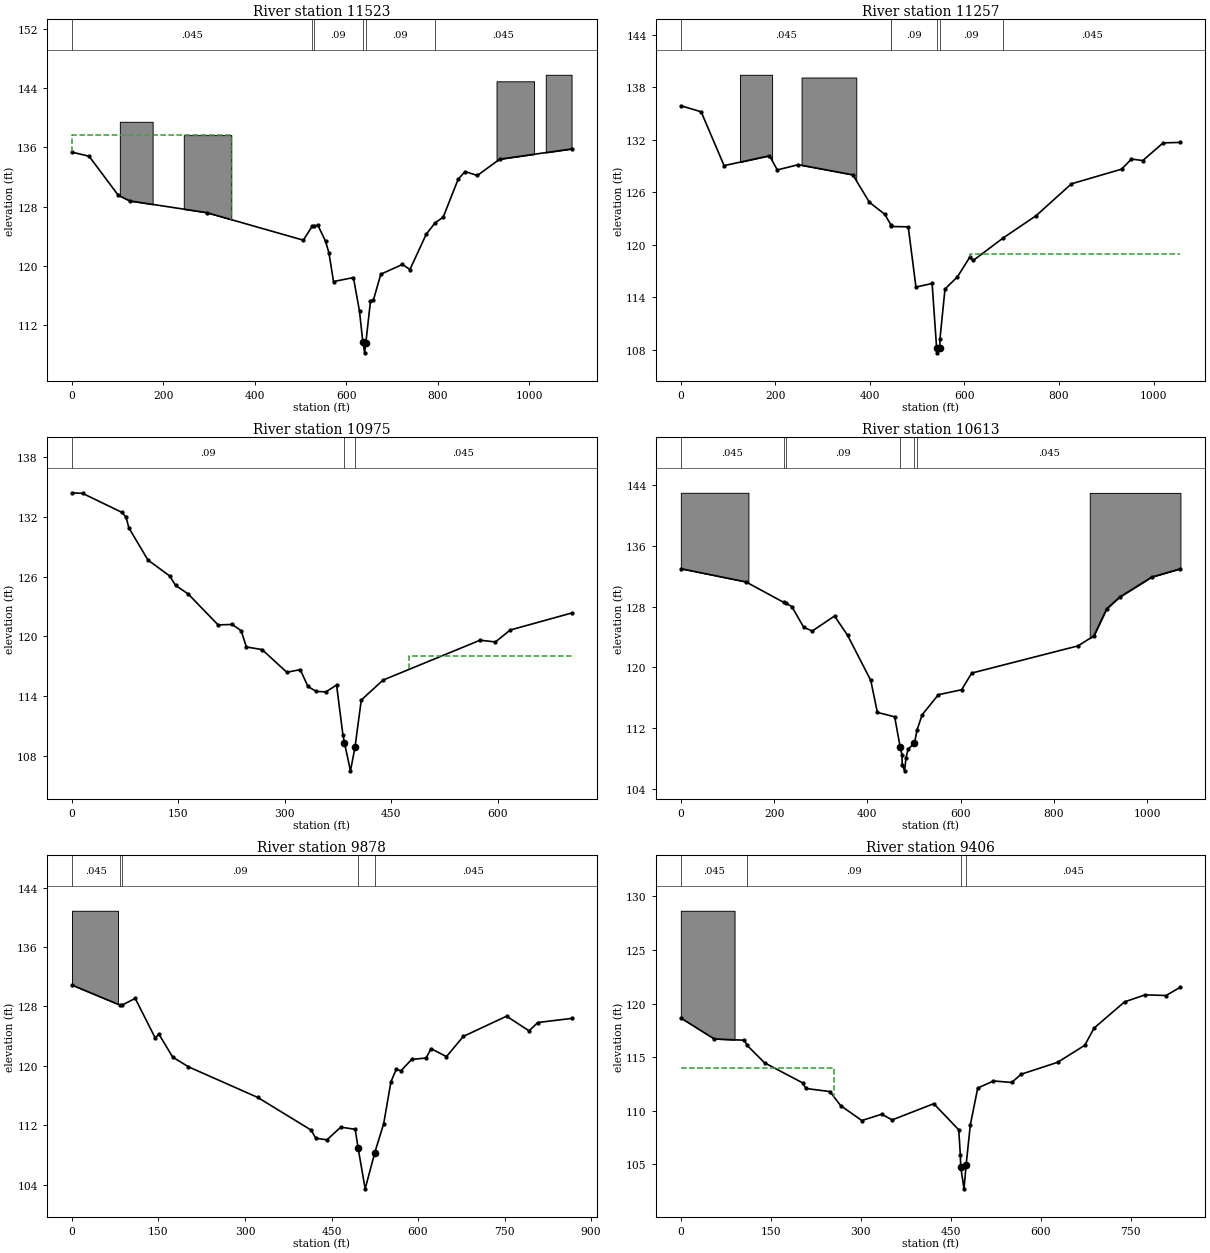
Type RM Length L Ch R = 1 ,11523   ,244.42,265.8,294.55
XS GIS Cut Line= 6
 2318708.7180293  714717.0840482 2318494.1252499  714783.7536496
 2318367.0363224  714848.3398259  2318204.411793  714902.8169891
 2317946.7713441  714962.0918988 2317671.1723582  715046.2652049
#Sta/Elev= 30
       0  135.36   37.36  134.81  101.44  129.53   126.7  128.78  294.79   127.2
  505.74  123.49  525.57   125.4  528.41  125.42  537.72  125.49   554.4  123.35
  561.77  121.78  571.83  117.91  615.35  118.45  628.68  113.89  635.84  109.78
  639.86   108.3   642.4  109.61  652.62  115.28  659.21  115.46  675.19   118.9
  722.47  120.22  738.84  119.53   774.5  124.29  793.49   125.8  811.53  126.59
  844.43  131.72  859.48  132.74  886.24  132.21  935.06  134.41 1092.22  135.79
#Mann= 6 ,-1 , 0
       0    .045       0  525.57    .045       0  528.41     .09       0
  635.84     .05       0   642.4     .09       0  793.49    .045       0
#XS Ineff= 2 , 0
       0  348.35  137.65               0
Permanent Ineff=
       F       F
#Block Obstruct= 4 ,-1
  104.68  176.35 139.454  244.46  348.35 137.654  928.18 1010.27  144.91
 1035.85 1092.22 145.789
Bank Sta=635.84,642.4
XS Rating Curve= 0 ,0
Exp/Cntr=0.3,0.1

Type RM Length L Ch R = 1 ,11257   ,300.26,281.93,253.97
BEGIN DESCRIPTION:
Surveyed Area
END DESCRIPTION:
XS GIS Cut Line= 6
2318694.61865364714631.7672348022318549.39257483714673.260400176
2318270.10580003714693.1340000182317998.81018838714636.554907724
2317842.41287279714698.7946557852317668.46075651714745.075494051
#Sta/Elev= 30
       0  135.89   42.96   135.2    91.5  129.05  187.56  130.18  204.08  128.56
  248.59  129.16  363.82     128  398.98  124.86 431.369   123.5  444.31   122.3
  445.26   122.1 481.072  122.06  497.43  115.18 531.622  115.59 541.155   108.2
 542.239  107.67 548.002  108.22 548.172  109.22 558.857  114.96 585.162  116.35
 611.078  118.57  618.89  118.23  681.21  120.76  751.81  123.34  826.35  126.97
  932.56  128.65   953.3   129.8   977.4  129.63 1020.42  131.65 1056.98   131.7
#Mann= 6 ,-1 , 0
       0    .045       0  444.31    .045       0  445.26     .09       0
 541.155     .05       0 548.002     .09       0  681.21    .045       0
#XS Ineff= 2 , 0
       0                  611.08       0     119
Permanent Ineff=
       F       F
#Block Obstruct= 2 ,-1
  125.13  193.09 139.425  255.43  371.18 139.112
Bank Sta=541.155,548.002
XS Rating Curve= 0 ,0
Exp/Cntr=0.3,0.1

Type RM Length L Ch R = 1 ,10975   ,406.37,361.81,303.95
XS GIS Cut Line= 5
 2318527.8955997  714342.0256206 2318443.6950455  714346.6183781
 2318266.1084223  714375.7058423 2318022.6922749  714404.7933064
 2317828.2655408  714417.0406597
#Sta/Elev= 30
       0   134.4   15.08  134.34   69.96  132.45    76.2  131.98   80.16  130.89
  107.07  127.66  137.89  126.05  145.96  125.12  163.74  124.26  206.03  121.15
  225.96   121.2  238.48  120.57  245.89  118.94  267.99  118.68  302.91   116.4
  321.82  116.67  332.62  114.98  344.13  114.49  357.79  114.43  373.01  115.12
  381.98   110.1  384.14  109.31   392.6  106.52  398.94  108.87  407.81  113.62
  438.52  115.62  575.36  119.62  596.84  119.44  617.79  120.64  704.24  122.34
#Mann= 3 , 0 , 0
       0     .09       0  384.14     .05       0  398.94    .045       0
#XS Ineff= 2 , 0
       0                     475       0     118
Permanent Ineff=
       F       F
Bank Sta=384.14,398.94
XS Rating Curve= 0 ,0
Exp/Cntr=0.3,0.1

Type RM Length L Ch R = 1 ,10613   ,662.43,734.95,823.13
XS GIS Cut Line= 4
 2318460.5351563  713870.5025175 2318091.5836373  713999.0997275
 2317862.2216798  714199.9651994 2317491.4633244   714262.417824
#Sta/Elev= 30
       0     133  139.55  131.26  220.32  128.57  225.35  128.46   238.2  127.99
  263.43  125.29  281.75  124.78  329.61  126.76  357.76  124.21   407.4  118.27
  421.52  114.06  458.63  113.48  470.48  109.47  474.49  108.45  474.71  107.15
     480  106.36  482.86  108.04   487.4  109.23  501.15  109.99  506.32  111.68
  517.49  113.74  552.31  116.39  602.38  117.05  623.82  119.24  852.06  122.83
  886.01  124.15  913.46  127.72  941.02  129.25 1009.91  131.89 1071.59  132.99
#Mann= 6 ,-1 , 0
       0    .045       0  220.32    .045       0  225.35     .09       0
  470.48     .05       0  501.15     .09       0  506.32    .045       0
#Block Obstruct= 2 ,-1
       0  144.95 143.002  877.06 1071.59 142.987
Bank Sta=470.48,501.15
XS Rating Curve= 0 ,0
Exp/Cntr=0.3,0.1

Type RM Length L Ch R = 1 ,9878    ,504.53,472.34,427.07
XS GIS Cut Line= 4
 2318385.5201172  713461.7471002 2318090.0527182  713402.0412528
 2317750.1886634  713360.7064353 2317528.2053843  713374.4847078
#Sta/Elev= 30
       0  130.87   84.11  128.15   87.05  128.19  109.73  129.07  144.47  123.73
  150.64  124.28  174.58  121.18  201.92  119.87  322.24  115.74  414.62  111.35
  422.76  110.25  442.14  110.04   466.1  111.75  491.07  111.45  496.04  108.98
  508.37  103.44  525.11  108.33  540.47  112.21  553.04  117.84  562.12  119.51
  570.66  119.35  588.97  120.86  613.92  121.05  622.66  122.31  649.26  121.24
  678.59  123.96   753.5  126.68  792.54  124.71  807.68  125.83  866.22  126.38
#Mann= 5 ,-1 , 0
       0    .045       0   84.11    .045       0   87.05     .09       0
  496.04     .05       0  525.11    .045       0
#Block Obstruct= 1 ,-1
       0   79.83 140.871
Bank Sta=496.04,525.11
XS Rating Curve= 0 ,0
Exp/Cntr=0.3,0.1

Type RM Length L Ch R = 1 ,9406    ,412.05,417.25,426.01
XS GIS Cut Line= 3
 2318325.8142697  712762.1170414 2318015.0376791   712878.466898
 2317572.6020401  713114.2284496
#Sta/Elev= 30
       0  118.66   55.69  116.71   105.7  116.59  110.81   116.1  139.74  114.48
  203.17  112.61  208.51  112.09  248.63   111.8  266.71  110.48   301.9   109.1
  335.02  109.69  352.47  109.16  421.84  110.67  463.47  108.23  466.08  105.92
  466.79  104.76  472.25  102.73  475.76  104.96  482.77  108.69  495.14  112.13
  521.42  112.79  551.74  112.65  567.66  113.42  628.37  114.53  673.67  116.12
  689.09  117.72  740.13  120.17  774.25  120.82  809.29  120.76  833.17  121.54
#Mann= 4 ,-1 , 0
       0    .045       0  110.81     .09       0  466.79     .05       0
  475.76    .045       0
#XS Ineff= 2 , 0
       0     255     114               0
Permanent Ineff=
       F       F
#Block Obstruct= 1 ,-1
       0   89.58 128.661
Bank Sta=466.79,475.76
XS Rating Curve= 0 ,0
Exp/Cntr=0.3,0.1

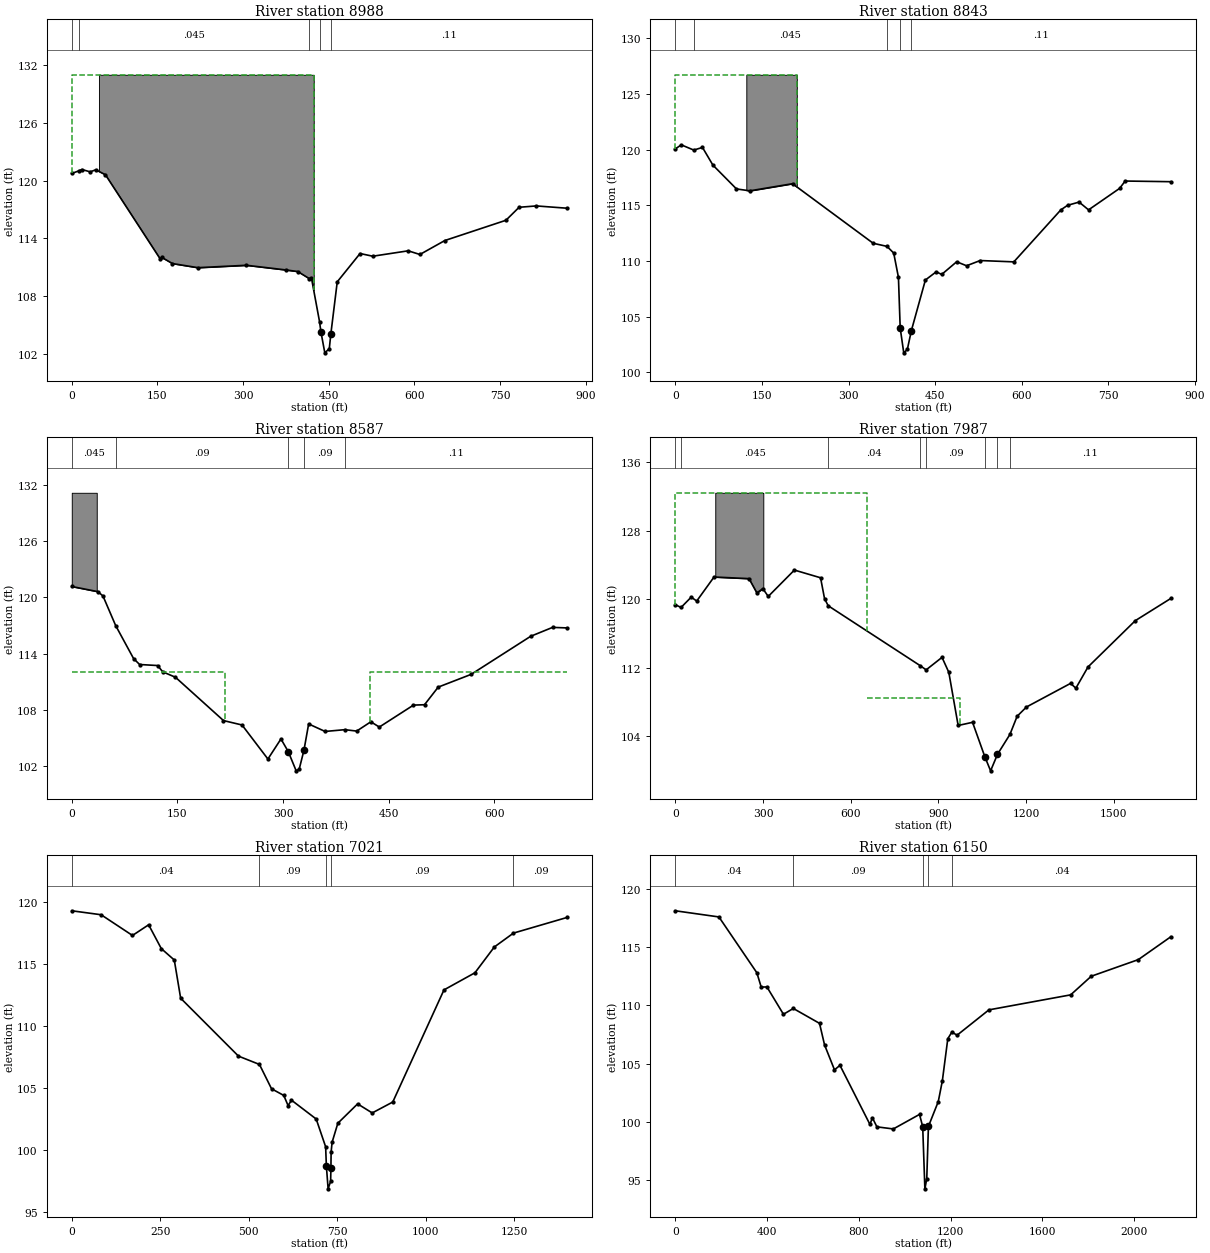
Type RM Length L Ch R = 1 ,8988    ,181.13,145.57,82.62
XS GIS Cut Line= 5
 2318109.9546674    712397.75828 2317604.7513426  712622.8033973
 2317532.7981418   712674.854649 2317471.5613752  712766.7097989
 2317431.7574769  712875.4050597
#Sta/Elev= 30
       0  120.75   12.33  121.02   17.76  121.16   32.18  120.92   42.12  121.13
   58.92  120.62  155.29  111.84  157.29  112.05  176.29   111.4     221  110.97
  305.92  111.22   374.4  110.74  395.88  110.57  416.13  109.83  419.84  109.88
  433.99  105.35  436.27  104.34  443.17  102.13  451.02  102.56  453.74  104.09
  464.95   109.5  504.91  112.44  527.12  112.16   589.2  112.72  609.72  112.34
  653.44  113.79  760.34  115.89  783.43  117.24  813.64  117.38  868.02  117.14
#Mann= 5 ,-1 , 0
       0    .035       0   12.33    .045       0  416.13     .09       0
  433.99     .05       0  453.74     .11       0
#XS Ineff= 2 , 0
       0  423.79  130.99               0
Permanent Ineff=
       F       F
#Block Obstruct= 1 ,-1
   47.61  423.79 130.994
Bank Sta=436.27,453.74
XS Rating Curve= 0 ,0
Exp/Cntr=0.3,0.1

Type RM Length L Ch R = 1 ,8843    ,278.67,255.51,175.58
XS GIS Cut Line= 5
 2317865.0076008  712142.0947793 2317655.2716751  712413.0674716
 2317549.6382527  712587.5922565  2317470.030456  712728.4368198
 2317419.5101236  712869.2813831
#Sta/Elev= 30
       0  120.07   10.46  120.44   32.09  119.97   47.12  120.21   65.18  118.62
     106  116.48  129.22  116.31  203.03  116.95  342.66   111.6  366.66  111.32
  378.21  110.72   386.4  108.54  389.43  103.99  395.59  101.76  401.76  102.06
  408.81  103.76  433.04   108.3  451.85  109.04  461.27   108.8  487.23  109.94
  504.34  109.58  527.92  110.05  586.19  109.93  667.56   114.6  679.21  115.01
  699.16   115.3  715.54   114.6  769.31  116.53  778.91  117.19  858.08  117.13
#Mann= 5 ,-1 , 0
       0    .035       0   32.09    .045       0  366.66     .09       0
  389.43     .05       0  408.81     .11       0
#XS Ineff= 2 , 0
       0  210.48  126.73               0
Permanent Ineff=
       F       F
#Block Obstruct= 1 ,-1
  123.01  210.48 126.733
Bank Sta=389.43,408.81
XS Rating Curve= 0 ,0
Exp/Cntr=0.3,0.1

Type RM Length L Ch R = 1 ,8587    ,583.37,600.07,566.66
XS GIS Cut Line= 4
 2317338.3714078  712149.7493751 2317382.7680636  712376.3254116
 2317387.3608211  712593.7159332 2317411.8555277  712847.8485147
#Sta/Elev= 30
       0  121.16   37.12  120.61    44.3  120.15   62.41  116.98   87.79  113.47
   96.33  112.84   121.9  112.73  129.16  112.06  147.21  111.48  215.41  106.86
  241.73  106.39  278.46  102.76  296.98   104.9  307.36  103.55  318.59   101.5
  322.82  101.66  329.62  103.69  336.29   106.5  359.63   105.7  387.63  105.89
   404.5  105.74  424.59  106.73  436.64  106.17  485.12  108.51  500.77  108.55
  520.24  110.43  567.02  111.79  651.52  115.85  682.63   116.8  703.63  116.74
#Mann= 5 ,-1 , 0
       0    .045       0   62.41     .09       0  307.36     .05       0
  329.62     .09       0  387.63     .11       0
#XS Ineff= 2 , 0
       0     218     112     424       0     112
Permanent Ineff=
       F       F
#Block Obstruct= 1 ,-1
       0   35.47 131.155
Bank Sta=307.36,329.62
XS Rating Curve= 0 ,0
Exp/Cntr=0.3,0.1

Type RM Length L Ch R = 1 ,7987    ,934.83,966.49,1012.35
XS GIS Cut Line= 4
 2317241.7533982   711619.115782 2316798.1270444  712185.2156691
 2316838.9515554  712803.0266036 2316915.1573094  713151.3957649
#Sta/Elev= 30
       0  119.37   19.83  119.04   54.67  120.25   73.39  119.79  132.63   122.6
   252.2  122.41  279.04  120.74  299.56  121.24  317.99  120.33  407.46  123.41
  496.92  122.51  510.54  120.07  523.07  119.24  837.66  112.24     858  111.75
   912.3  113.21  935.53  111.46  967.44  105.25 1016.72  105.62 1058.69   101.6
 1078.41   99.95 1101.97  101.88 1144.45   104.2  1169.2  106.33 1201.09  107.41
 1351.94  110.17 1370.03  109.61 1411.55  112.09 1573.32   117.5 1694.98   120.1
#Mann= 8 ,-1 , 0
       0    .035       0   19.83    .045       0  523.07     .04       0
  837.66    .045       0     858     .09       0 1058.69     .05       0
 1101.97     .09       0 1144.45     .11       0
#XS Ineff= 2 ,-1
       0     656  132.44     656     975   108.5
Permanent Ineff=
       F       F
#Block Obstruct= 1 ,-1
   136.8  301.09 132.442
Bank Sta=1058.69,1101.97
XS Rating Curve= 0 ,0
Exp/Cntr=0.3,0.1

Type RM Length L Ch R = 1 ,7021    ,823.17,870.98,899.74
XS GIS Cut Line= 4
 2316264.6867661  711820.5167034 2315981.6368225  712236.9267165
 2315769.3493649  712737.7073858  2315810.173876  713088.7981812
#Sta/Elev= 30
       0  119.28   82.95  118.96   171.6  117.29  217.29  118.15  253.08  116.23
  289.79  115.31  307.79  112.23  471.25  107.56  530.51  106.89  564.59  104.93
   599.3  104.39  611.44  103.57  620.98  104.01  690.87  102.49  717.57  100.25
  719.57   98.73  724.58   96.86  731.63   97.46   732.5   98.53  733.04   99.82
  735.88  100.62  752.08  102.15  807.95  103.71  849.24  102.98   907.3  103.86
 1052.03   112.9 1139.55  114.28 1194.33  116.36 1248.46  117.48 1400.88  118.75
#Mann= 5 ,-1 , 0
       0     .04       0  530.51     .09       0  717.57     .05       0
   732.5     .09       0 1248.46     .09       0
Bank Sta=719.57,732.5
XS Rating Curve= 0 ,0
Exp/Cntr=0.3,0.1

Type RM Length L Ch R = 1 ,6150    ,1169.68,1245,1125.2
XS GIS Cut Line= 4
 2316035.1622926  711464.4362455 2315527.1239324  711703.9400439
 2314892.0759821  712273.6687765 2314707.0048652  712995.8090171
#Sta/Elev= 30
       0  118.14  190.31  117.61  355.68  112.81  374.63  111.58  399.58  111.59
  471.62  109.24  514.58  109.74  628.82  108.46  650.69  106.61  694.07  104.46
   717.9  104.85  848.52   99.77  859.35  100.34  878.89   99.56  950.46   99.38
 1064.63  100.63 1078.53   99.58 1088.03   94.23 1096.24    95.1 1103.48    99.6
 1146.39  101.73  1164.1  103.51 1187.95  107.14 1205.66  107.71 1228.37  107.44
 1367.12  109.62 1723.46  110.91 1813.14  112.51 2018.32  113.94  2160.3  115.91
#Mann= 5 ,-1 , 0
       0     .04       0  514.58     .09       0 1078.53     .05       0
 1103.48     .09       0 1205.66     .04       0
Bank Sta=1078.53,1103.48
XS Rating Curve= 0 ,0
Exp/Cntr=0.3,0.1

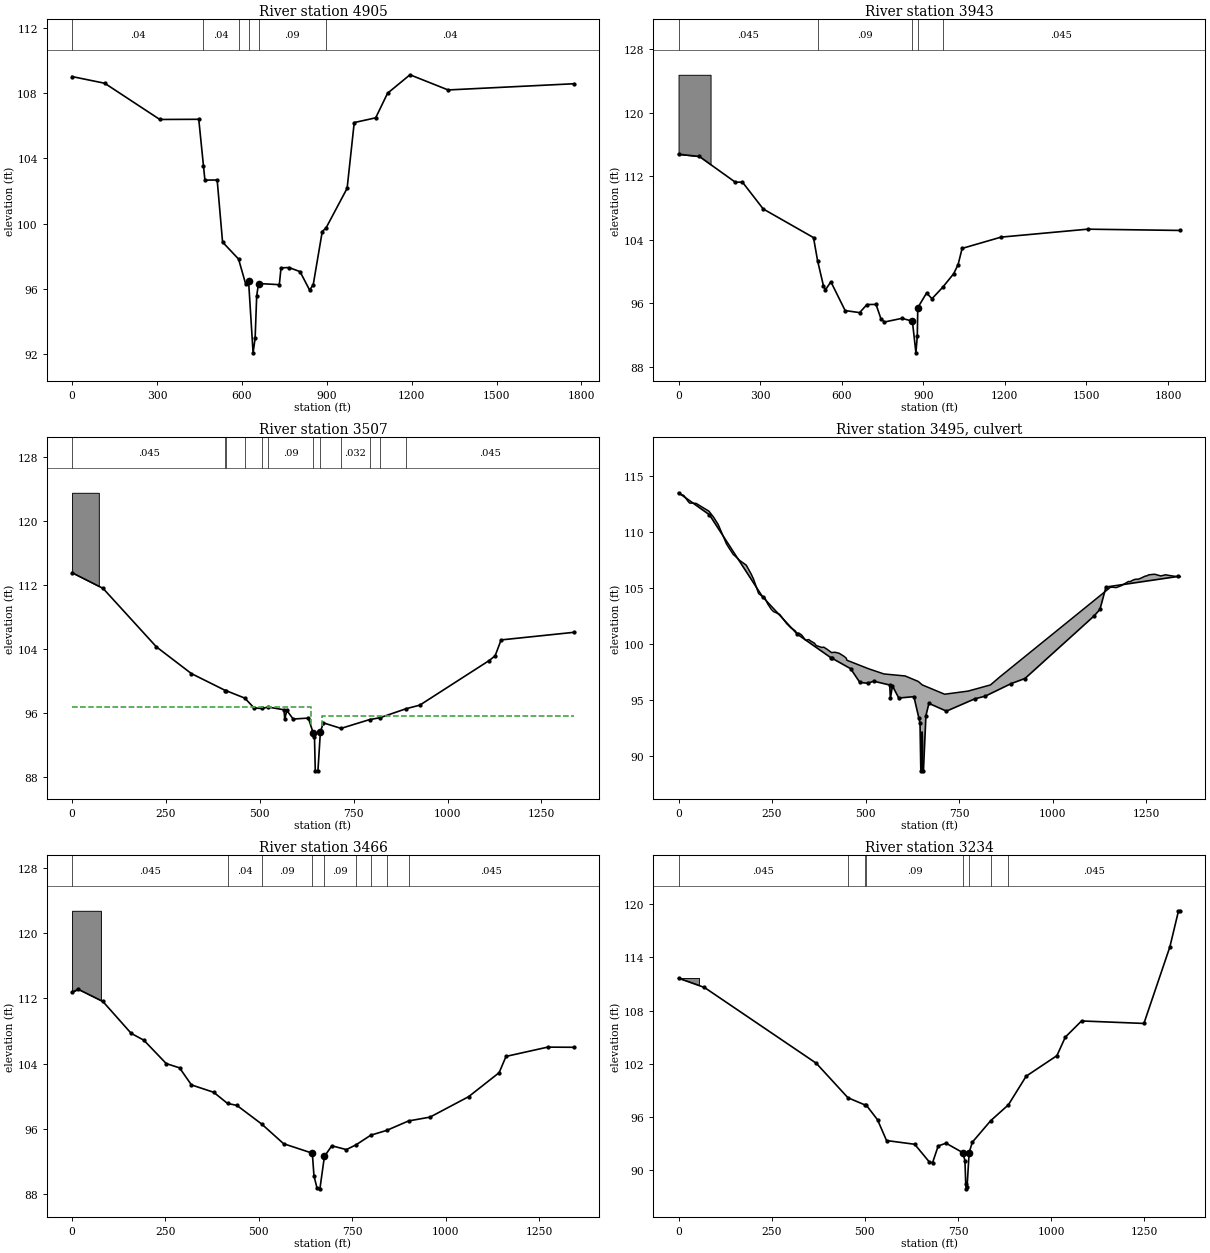
Type RM Length L Ch R = 1 ,4905    ,961.56,962.33,930.22
XS GIS Cut Line= 3
 2315077.1470991  710466.5037522 2314413.0683853  711453.5497092
 2314024.7819243  711889.0111609
#Sta/Elev= 30
       0  109.01  115.32   108.6  309.96  106.38  447.67  106.39  464.37  103.52
  469.44  102.66  512.72  102.67   531.8   98.86  588.31   97.82  613.75   96.27
  623.68   96.48  639.58   92.07  646.82   92.96  652.37   95.56  658.82   96.32
  732.29   96.25  738.35   97.28  766.66    97.3  805.47   97.05  839.33   95.92
  852.07   96.24  884.03   99.51  897.18   99.72   971.9  102.16  997.01  106.19
 1072.75  106.48 1114.89  107.99 1194.03  109.12 1328.74  108.19 1773.08  108.57
#Mann= 6 ,-1 , 0
       0     .04       0  464.37     .04       0  588.31     .09       0
  623.68     .05       0  658.82     .09       0  897.18     .04       0
Bank Sta=623.68,658.82
XS Rating Curve= 0 ,0
Exp/Cntr=0.3,0.1

Type RM Length L Ch R = 1 ,3943    ,399.75,435.31,368.25
XS GIS Cut Line= 3
 2314322.3472496  709795.1673476 2313752.6185171  710814.8729135
 2313349.8166743  711359.1997281
#Sta/Elev= 30
       0  114.78   76.53   114.5  208.83  111.26  234.99  111.27  311.49  107.89
  496.33  104.29  511.31  101.38  532.79   98.24  540.38   97.72  560.23   98.73
  612.61   95.11  665.95   94.85  692.95   95.87  726.25   95.88   744.2   94.09
  757.23   93.67   821.5   94.13  859.91   93.78  872.98   89.79  877.92   91.88
   879.8   95.47  912.14   97.32  931.99    96.6  971.14   98.03 1011.65   99.74
 1028.03  100.89  1042.8  102.93 1186.14  104.35  1504.3  105.35 1845.23  105.19
#Mann= 5 ,-1 , 0
       0    .045       0  511.31     .09       0  859.91     .05       0
   879.8     .09       0  971.14    .045       0
#Block Obstruct= 1 ,-1
       0  117.78 124.776
Bank Sta=859.91,879.8
XS Rating Curve= 0 ,0
Exp/Cntr=0.5,0.3

Type RM Length L Ch R = 1 ,3507    ,31.81,41.5,35.8
BEGIN DESCRIPTION:
Surveyed Area
END DESCRIPTION:
XS GIS Cut Line= 6
 2313948.9800864  709743.7925249 2313610.7078702   710312.163388
  2313599.121125  710332.9430662 2313582.3916263  710376.5592593
  2313377.455267   710724.891322 2313281.8581314  710900.5510585
#Sta/Elev= 30
       0  113.51   82.46  111.55  224.63  104.23  317.72  100.89   408.4   98.77
   409.2   98.77  459.99   97.82  484.72   96.59  505.56   96.52     522    96.7
  564.49   96.36  566.43   95.17  571.89   96.28  588.76    95.2  629.25   95.32
  642.27   93.45  645.59   92.97  647.74   88.72  654.79   88.72  661.38   93.63
  669.41   94.72  716.31   94.03  792.22   95.13  819.61   95.36   889.5   96.49
  926.15   96.94  1110.9  102.52 1126.68  103.11 1142.67   105.1  1336.4  106.05
#Mann= 12 ,-1 , 0
       0    .045       0   408.4    .075       0   409.2     .04       0
  459.99    .075       0  505.56     .04       0     522     .09       0
  642.27     .05       0  661.38     .09       0  716.31    .032       0
  792.22     .09       0  819.61    .075       0   889.5    .045       0
#XS Ineff= 2 , 0
       0  637.27   96.68  666.38       0   95.54
Permanent Ineff=
       F       F
#Block Obstruct= 1 ,-1
       0   71.26 123.509
Bank Sta=642.27,661.38
XS Rating Curve= 0 ,0
Exp/Cntr=0.5,0.3

Type RM Length L Ch R = 2 ,3495    ,,,
Node Photo=STR_39PHT2.JPG
BEGIN DESCRIPTION:
Dirt Road
END DESCRIPTION:
Bridge Culvert--1,0,-1,-1, 0
Deck Dist Width WeirC Skew NumUp NumDn MinLoCord MaxHiCord MaxSubmerge Is_Ogee
9,10.7,2.6,0, 85, 85, , , 0.95, 0, 1,1,,
       0   13.78   25.18   29.62    36.4   47.21   52.54   66.25   81.22   85.42
   93.77  106.06  120.29  127.79  134.23  146.22  151.09  163.62   175.8  181.18
  194.55  198.23  200.32  214.07  224.86  229.67  238.32  248.31   254.1  270.51
  289.48  293.16  294.83  299.42  312.16  316.54  322.07  329.44  339.92  347.88
  352.59  363.48  368.02  383.42  388.15  397.11  408.81  418.87  429.53  442.05
  448.28 450.214 508.154 549.007 605.798 640.858 651.637 711.398  774.22 833.966
  857.32 1154.22  1158.5  1169.9 1183.51 1185.78 1189.68 1202.94 1207.05 1214.27
 1220.42 1230.19 1238.43 1246.46 1253.38 1256.84 1271.08 1274.57 1276.93 1289.19
 1301.47 1303.88 1307.46 1324.29  1341.5
  113.43  113.28  112.76  112.59  112.59  112.56  112.45  112.17  111.87  111.69
  111.33  110.68  109.57  108.97  108.62  108.01  107.87  107.47  107.18  107.05
  106.24  105.97  105.83  104.52  104.25  104.21   103.6   103.1  102.91  102.66
  101.82  101.71  101.65  101.49  101.19  100.96  100.99  100.81  100.35  100.42
   100.3  100.09   99.88   99.71   99.74   99.55   99.26   99.28   99.19   98.93
   98.76   98.57   97.81   97.35   97.17   96.68   96.37   95.54   95.82   96.37
   97.04  105.07  105.09  105.05  105.22  105.26  105.34   105.6  105.58  105.71
  105.79  105.81  105.93  106.06  106.12  106.19  106.24  106.23  106.21  106.09
  106.19  106.19  106.16  106.07  106.03
                                                                                
                                                                                
                                                                                
                                                                                
                                                                                
                                                                                
                                                                                
                                                                                
                                        
       0   13.78   25.18   29.62    36.4   47.21   52.54   66.25   81.22   85.42
   93.77  106.06  120.29  127.79  134.23  146.22  151.09  163.62   175.8  181.18
  194.55  198.23  200.32  214.07  224.86  229.67  238.32  248.31   254.1  270.51
  289.48  293.16  294.83  299.42  312.16  316.54  322.07  329.44  339.92  347.88
  352.59  363.48  368.02  383.42  388.15  397.11  408.81  418.87  429.53  442.05
  448.28 450.214 508.154 549.007 605.798 640.858 651.637 711.398  774.22 833.966
  857.32 1154.22  1158.5  1169.9 1183.51 1185.78 1189.68 1202.94 1207.05 1214.27
 1220.42 1230.19 1238.43 1246.46 1253.38 1256.84 1271.08 1274.57 1276.93 1289.19
 1301.47 1303.88 1307.46 1324.29  1341.5
  113.43  113.28  112.76  112.59  112.59  112.56  112.45  112.17  111.87  111.69
  111.33  110.68  109.57  108.97  108.62  108.01  107.87  107.47  107.18  107.05
  106.24  105.97  105.83  104.52  104.25  104.21   103.6   103.1  102.91  102.66
  101.82  101.71  101.65  101.49  101.19  100.96  100.99  100.81  100.35  100.42
   100.3  100.09   99.88   99.71   99.74   99.55   99.26   99.28   99.19   98.93
   98.76   98.57   97.81   97.35   97.17   96.68   96.37   95.54   95.82   96.37
   97.04  105.07  105.09  105.05  105.22  105.26  105.34   105.6  105.58  105.71
  105.79  105.81  105.93  106.06  106.12  106.19  106.24  106.23  106.21  106.09
  106.19  106.19  106.16  106.07  106.03
                                                                                
                                                                                
                                                                                
                                                                                
                                                                                
                                                                                
                                                                                
                                                                                
                                        
BR Coef=-1 , 0 , 0 ,, 0 ,,,0.8,-1,,0,
WSPro=,,,, 1 ,,,, 0 ,,,, 0 ,,,,-1 ,-1 ,-1 , 0 , 0 , 0 , 0 , 0
Culvert=1,3.5,,38,0.024,0.9,1,2,3,88.705,651.03,88.605,663.57,Culvert #1  , 0 ,1.5
Culvert Bottom n=0.024
Culvert Bottom Depth=3.5
Culvert Depth Blocked=3.4
BC Design=,, 0 ,, 0 ,,,,,,
BC Use User HTab Curves=0
BC User HTab FreeFlow(D)= 0

Type RM Length L Ch R = 1 ,3466    ,165.6,231.27,168.18
BEGIN DESCRIPTION:
Surveyed Area
END DESCRIPTION:
XS GIS Cut Line= 6
 2313921.1794964  709723.8162151    2313665.8837     710162.7303
    2313586.3747     710272.0683    2313543.8151     710350.8831
     2313519.886     710411.6503 2313256.7171666  710887.4125993
#Sta/Elev= 30
       0  112.77   16.51  113.13   82.45  111.63  158.32  107.71  192.18  106.87
   252.1     104  287.86  103.47  319.53  101.38  379.25  100.47  416.22    99.1
 441.347   98.86 507.986   96.56 566.429   94.15 643.278   92.99 647.712   90.18
 655.639   88.75 663.565   88.61 675.657   92.59 695.407    93.9 734.503   93.43
  760.43   94.02 799.799    95.2  842.39   95.79  900.83   96.95  958.36   97.42
 1061.66   99.93 1143.43  102.88 1161.91  104.88 1273.43  106.02 1343.52     106
#Mann= 9 ,-1 , 0
       0    .045       0  416.22     .04       0 507.986     .09       0
 643.278     .05       0 675.657     .09       0  760.43    .032       0
 799.799     .09       0  842.39    .075       0  900.83    .045       0
#XS Ineff= 2 , 0
       0  638.28   92.11  680.66       0   92.11
Permanent Ineff=
       F       F
#Block Obstruct= 1 ,-1
       0   77.24  122.77
Bank Sta=643.278,675.657
XS Rating Curve= 0 ,0
Exp/Cntr=0.5,0.3

Type RM Length L Ch R = 1 ,3234    ,430.02,397.11,389.87
XS GIS Cut Line= 4
 2313788.9069714  709686.3019847 2313513.1147186  710099.9903638
 2313259.0955385  710520.9364337 2313023.2205856  710789.4709955
#Sta/Elev= 30
       0  111.65   69.61  110.61  369.43  102.08   454.5   98.19   499.6   97.39
   503.1   97.39  533.91   95.71  558.05   93.37  633.58   92.95     673   90.95
  681.64   90.89  696.68   92.76  717.66   93.07   762.5   92.01  768.41   91.11
  770.58   88.42  772.16   87.93  774.05   88.09  779.68   92.02  788.17   93.18
  837.37    95.6   884.9   97.39  932.72  100.62 1015.12  102.93 1037.74  105.02
 1081.23  106.84 1248.58  106.56 1318.19  115.18 1341.03  119.18 1346.26  119.25
#Mann= 8 ,-1 , 0
       0    .045       0   454.5     .04       0   499.6    .075       0
   503.1     .09       0   762.5     .05       0  779.68     .09       0
  837.37    .075       0   884.9    .045       0
#Block Obstruct= 1 ,-1
       0   53.99111.6491
Bank Sta=762.5,779.68
XS Rating Curve= 0 ,0
Exp/Cntr=0.3,0.1

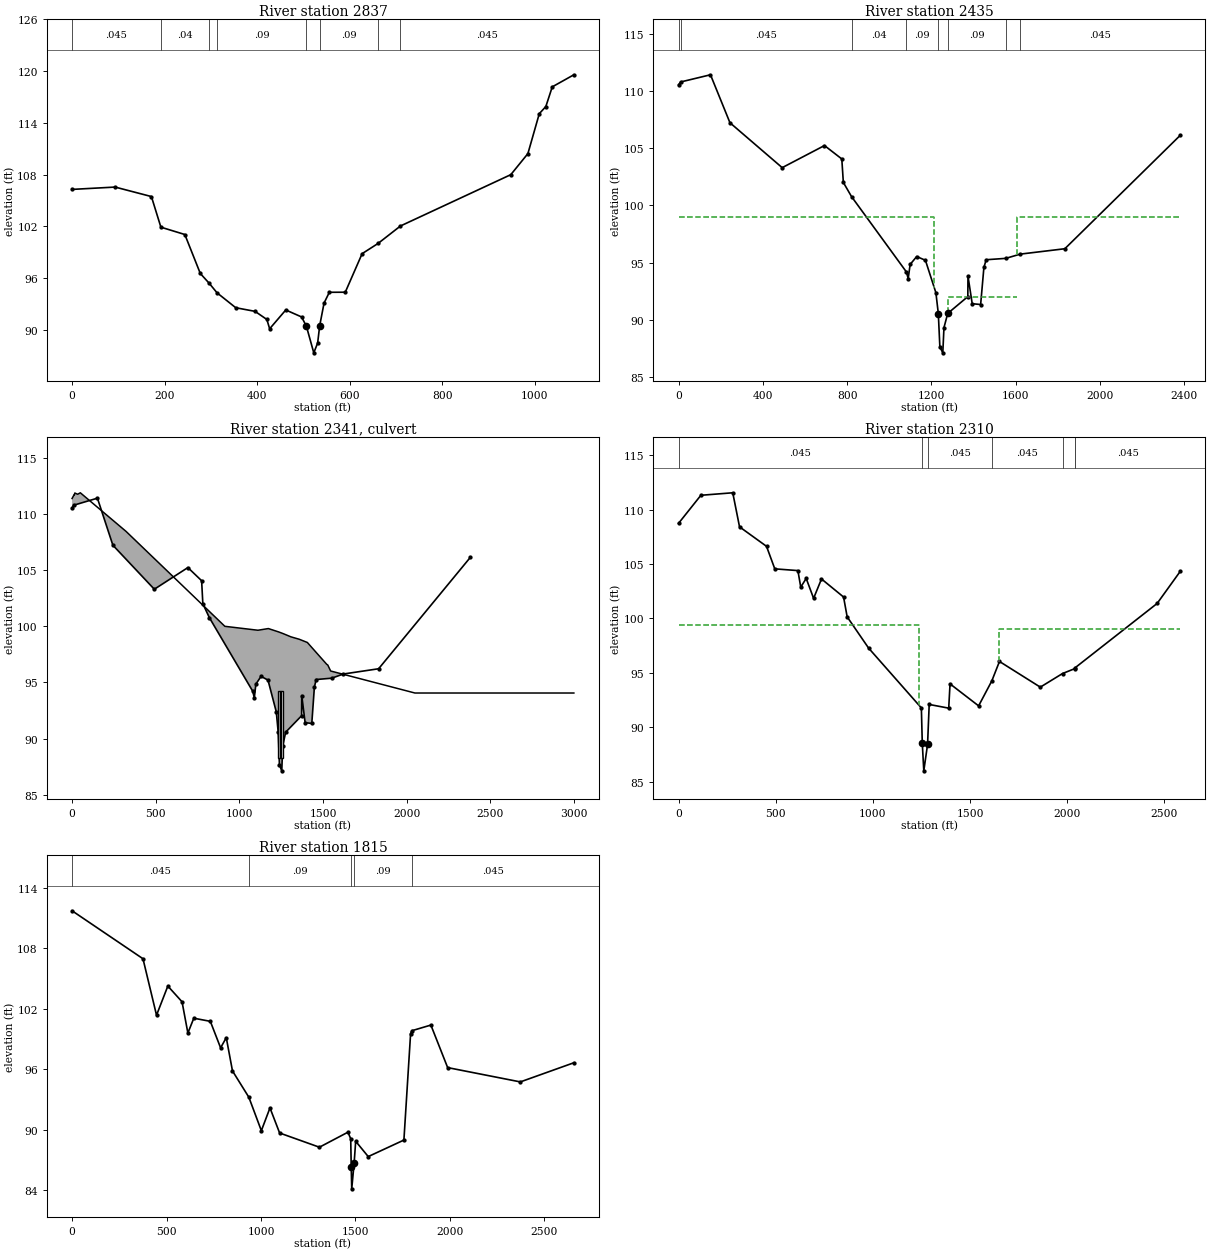
Type RM Length L Ch R = 1 ,2837    ,324.8,402.69,323.88
XS GIS Cut Line= 3
 2313203.4532419  709774.9667747 2312907.0975318  710428.0077503
 2313005.0763584  710781.8201797
#Sta/Elev= 30
       0  106.28   93.01  106.55  171.44  105.45  191.92   101.9  243.66  101.05
   277.1   96.53  296.22    95.4  313.24   94.29  353.69   92.56  395.37   92.14
  420.88    91.2  426.95   90.12  461.77    92.3  495.99   91.49  506.43    90.4
  522.29   87.33  530.67   88.47  534.98   90.45  544.49    93.1   555.9   94.35
  590.35   94.36  626.77   98.83  661.08  100.01  709.65  102.04  948.04  107.99
  984.95  110.43 1009.57  115.06 1023.74  115.89 1037.59  118.17 1084.27  119.57
#Mann= 8 ,-1 , 0
       0    .045       0  191.92     .04       0  296.22    .075       0
  313.24     .09       0  506.43     .05       0  534.98     .09       0
  661.08     .07       0  709.65    .045       0
Bank Sta=506.43,534.98
XS Rating Curve= 0 ,0
Exp/Cntr=0.5,0.3

Type RM Length L Ch R = 1 ,2435    ,123.25,124.6,124.71
BEGIN DESCRIPTION:
Surveyed Area
END DESCRIPTION:
XS GIS Cut Line= 6
 2313314.3359453   708989.770753    2312719.1035       710055.55
    2312685.1858     710145.6697    2312659.3456     710193.4535
 2312505.6226067  710627.6435826 2312939.8251889  710961.6166516
#Sta/Elev= 30
       0  110.53    9.52  110.78  151.56  111.41  243.97  107.22  491.77   103.3
  692.41  105.23  774.56  104.06  781.86  102.01  820.83  100.77 1080.79    94.2
 1089.53   93.62 1098.82   94.851129.811   95.541171.348   95.211220.963   92.38
1232.458   90.561239.782   87.651253.699   87.131259.256   89.331277.019   90.57
1372.439   92.04 1373.16   93.83 1393.27   91.42 1433.25   91.35 1448.73   94.59
 1459.51   95.26 1552.62   95.38 1621.18   95.75 1832.72   96.22 2380.59  106.13
#Mann= 8 ,-1 , 0
       0    .035       0    9.52    .045       0  820.83     .04       0
 1080.79     .09       01232.458     .05       01277.019     .09       0
 1552.62     .07       0 1621.18    .045       0
#XS Ineff= 3 ,-1
       0 1213.75      99 1278.25    1605      92    1605 2380.59      99
Permanent Ineff=
       F       F       F
Bank Sta=1232.458,1277.019
XS Rating Curve= 0 ,0
Exp/Cntr=0.5,0.3

Type RM Length L Ch R = 2 ,2341    ,,,
BEGIN DESCRIPTION:
Forrest Hills Rd
END DESCRIPTION:
Bridge Culvert--1,0,-1,-1, 0
Deck Dist Width WeirC Skew NumUp NumDn MinLoCord MaxHiCord MaxSubmerge Is_Ogee
29,64,2.6,0, 20, 20, , , 0.98, 0, 1,1,,
       0   11.47   13.37   16.36   33.35   49.35  322.86  913.381111.3261173.462
1235.0891261.828 1308.941357.8341406.728 1522.86 1528.54    1546 2049.72    3000
  111.38   111.7  111.69  111.87  111.76  111.89  108.45     100   99.65    99.8
    99.5   99.35   99.06   98.85   98.56   96.61   96.56   96.02   94.06   94.06
                                                                                
                                                                                
       0   11.47   13.37   16.36   33.35   49.35  322.86  913.381111.3261173.462
1235.0891261.828 1308.941357.8341406.728 1522.86 1528.54    1546 2049.72    3000
  111.38   111.7  111.69  111.87  111.76  111.89  108.45     100   99.65    99.8
    99.5   99.35   99.06   98.85   98.56   96.61   96.56   96.02   94.06   94.06
                                                                                
                                                                                
BR Coef=-1 , 0 , 0 ,, 0 ,,,0.8,-1,,0,
WSPro=,,,, 1 ,,,, 0 ,,,, 0 ,,,,-1 ,-1 ,-1 , 0 , 0 , 0 , 0 , 0
Multiple Barrel Culv=2,6,7.5,95.54,0.012,0.4,1,8,1,88.23,88.13, 3,Culvert #1  , 0 ,14.95
  1237.5  1258.5    1246    1267  1254.5  1275.5
Culvert Bottom n=0.012
BC Design=,, 0 ,, 0 ,,,,,,
BC Use User HTab Curves=0
BC User HTab FreeFlow(D)= 0

Type RM Length L Ch R = 1 ,2310    ,496.47,495.03,500.47
BEGIN DESCRIPTION:
Surveyed Section
END DESCRIPTION:
XS GIS Cut Line= 6
 2313200.9845499  708919.0657942 2312703.9742968  709808.1197585
    2312601.9351     710014.9058  2312367.549284  710667.4317523
 2312606.0185132  710859.7507647 2312877.1384892  711050.9451986
#Sta/Elev= 30
       0  108.74  115.01  111.32  278.99  111.55  313.85  108.42  452.75  106.63
  495.23  104.56  614.12   104.4  628.85  102.88  656.84  103.68  694.94  101.85
  735.57  103.63  849.18  101.97  867.64  100.15   977.9   97.281249.419   91.78
1254.181   88.52 1261.94      861281.325   88.431289.734    92.11390.132   91.76
 1396.99   93.99 1543.96   91.97 1611.85   94.26 1651.25   96.05 1861.43   93.69
 1975.63   94.94 2039.92    95.4 2040.43   95.47 2462.47  101.38 2581.85  104.34
#Mann= 7 ,-1 , 0
       0    .045       01254.181     .05       01281.325    .045       0
 1611.85    .045       0 1975.63    .035       0 2039.92    .035       0
 2040.43    .045       0
#XS Ineff= 3 ,-1
       0 1239.75    99.4 1294.25    1650      92    1650 2581.85      99
Permanent Ineff=
       F       F       F
Bank Sta=1254.181,1281.325
XS Rating Curve= 0 ,0
Exp/Cntr=0.5,0.3

Type RM Length L Ch R = 1 ,1815    ,1554.34,1815,1997.87
XS GIS Cut Line= 5
 2312919.7984908  708854.4496506 2312411.7601306  709184.6745848
 2312179.7689733  709812.3161857 2312062.7387081  710171.5718832
 2311754.9391078  711126.1068899
#Sta/Elev= 30
       0  111.73  375.32  106.97  447.01  101.37  506.87  104.26  582.08   102.7
  612.95    99.6  644.33  101.07   731.8  100.76  786.16   98.13  816.16   99.14
  849.02   95.84  935.65   93.23 1001.83   89.91 1047.45   92.17 1098.57   89.68
 1309.14   88.27 1460.06   89.76  1474.8   89.11 1477.55   86.28 1480.18   84.14
 1492.85   86.69 1501.08   88.86 1567.52   87.34 1756.34   88.98 1791.74   99.54
 1798.54   99.83 1899.06  100.39 1987.85   96.17 2372.55   94.75 2655.85   96.65
#Mann= 5 ,-1 , 0
       0    .045       0  935.65     .09       0 1477.55     .05       0
 1492.85     .09       0 1798.54    .045       0
#XS Ineff= 2 , 0
       0    1236            1610       0
Permanent Ineff=
       F       F
Bank Sta=1477.55,1492.85
XS Rating Curve= 0 ,0
Exp/Cntr=0.3,0.1

Chan Stop Cuts=-1
Use User Specified Reach Order=0
User Specified Reach Order=Wiggins Mill    ,Trib