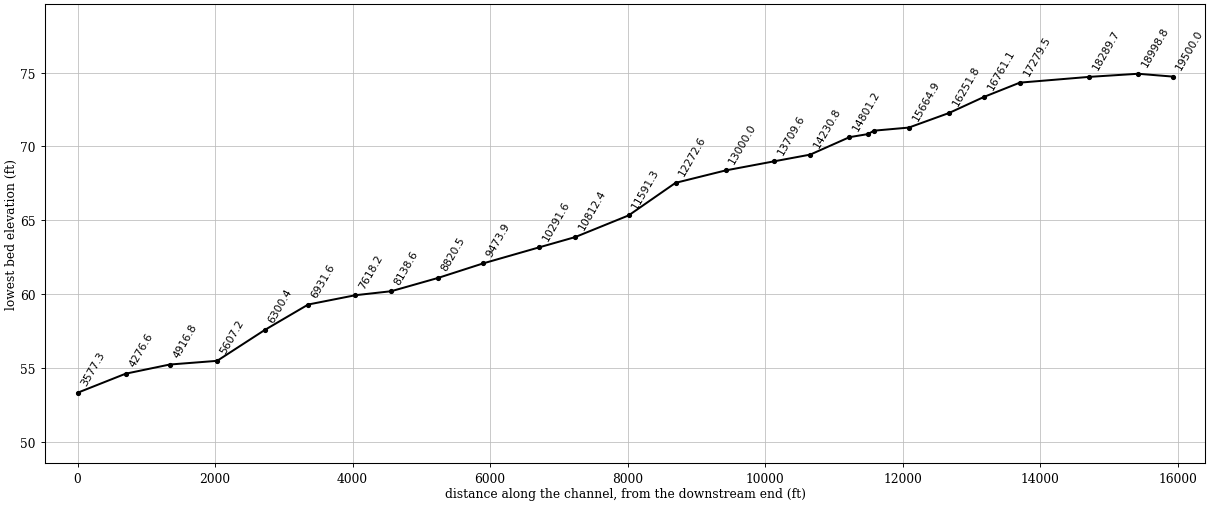
--- Goss_Swamp_021220.prj (project) ---

Proj Title=Goss Swamp
Current Plan=p02
Default Exp/Contr=0.3,0.1
English Units
Geom File=g01
Flow File=f02
Flow File=f01
Plan File=p02
Plan File=p01
Y Axis Title=Elevation
X Axis Title(PF)=Main Channel Distance
X Axis Title(XS)=Station
BEGIN DESCRIPTION:
NEUSE RIVER BASIN
Little Contentnea Creek Sub-basin
GOSS SWAMP
(Flood Hazard, Floodway) Model
Prepared by: Andrew J. Bonner   Date: 11/6/2002
Watershed Concepts
3333 Regency Pkwy
Cary, North Carolina 27511
END DESCRIPTION:
DSS Export Rating Curves= 0
DSS Export Rating Curve Sorted= 0
DSS Export Volume Flow Curves= 0
DXF OffsetX= 0
DXF OffsetY= 0
DXF ScaleX= 1
DXF ScaleY= 10

--- Goss_Swamp_021220.p02 (plan) ---

Plan Title=Multi_Profile
Program Version=4.00
Short Identifier=Multi_Profile
Geom File=g01
Flow File=f02
Subcritical Flow
K Sum by GR= 0
Std Step Tol= 0.01
Critical Tol= 0.01
Num of Std Step Trials= 20
Max Error Tol= 0.3
Flow Tol Ratio= 0.001
Split Flow NTrial= 30
Split Flow Tol= 0.02
Split Flow Ratio= 0.02
Log Output Level= 0
Friction Slope Method= 1
Unsteady Friction Slope Method= 2
Unsteady Bridges Friction Slope Method= 1
Parabolic Critical Depth
Global Vel Dist= 0 , 0 , 0
Global Log Level= 0
CheckData=True
Encroach Param=-1 ,0,0, 0
Computation Interval=1HOUR
Output Interval=1HOUR
Run HTab= 0
Run UNet= 0
Run PostProcess= 0
Run WQNet= 0
UNET Theta= 1
UNET Theta Warmup= 1
UNET ZTol= 0.02
UNET ZSATol= 0.05
UNET MxIter= 20
UNET MaxInSteps= 0
UNET DtIC= 0
UNET DtMin= 0
UNET MaxCRTS= 20
UNET WFStab= 2
UNET SFStab= 1
UNET WFX= 1
UNET SFX= 1
UNET DSS MLevel= 4
UNET DZMax Abort= 100
UNET Convert EG Bridges= 0
UNET Use Existing IB Tables=-1
UNET Froude Reduction=False
UNET Froude Limit= 1
UNET Froude Power= 10
UNET Time Slicing=0,0, 5
Instantaneous Interval=1HOUR
Write IC File= 0
Echo Input=False
Echo Output=False
Write Detailed= 0
Detailed Automatic Start=False, 10
WQ ULTIMATE=-1
WQ Max Comp Step=1HOUR
WQ Output Interval=15MIN
WQ Output Selected Increments= 0
WQ Output face flow=0
WQ Output face velocity=0
WQ Output face area=0
WQ Output face dispersion=0
WQ Output cell volume=0
WQ Output cell surface area=0
WQ Output cell continuity=0
WQ Output face conc=0
WQ Output face dconc_dx=0
WQ Output face courant=0
WQ Output face peclet=0
WQ Output face adv mass=0
WQ Output face disp mass=0
WQ Output cell mass=0
WQ Output cell source sink temp=0
WQ Output cell source sink nsm=0
WQ Output MaxMinRange=-1
WQ Daily Max Min Mean=-1
WQ Daily Range=0
WQ Daily Time=0
WQ Create Restart=0
WQ Fixed Restart=0
WQ System Summary=False
Sorting and Armoring Iterations= 10
XS Update Threshold= 0.02
Hydraulics Update Threshold= 0.02
Energy Slope Method= 1
Volume Change Method= 0
XS Weighting Method= 0
Number of US Weighted Cross Sections= 1
Number of DS Weighted Cross Sections= 1
Upstream XS Weight=0.25
Main XS Weight=0.5
Downstream XS Weight=0.25
Number of DS XS's Weighted with US Boundary= 1
Upstream Boundary Weight= 1
Weight of XSs Associated with US Boundary= 0
Number of US XS's Weighted with DS Boundary= 1
Downstream Boundary Weight= 0.5
Weight of XSs Associated with DS Boundary= 0.5
Sediment Output Level= 4
Mass or Volume Output= 0
Output Increment Type= 1
Profile and TS Output Increment= 10
XS Output Flag= 0
XS Output Increment= 10
Disregard all LS=0
Disregard all Conn=0
Disregard all Breaches=0
Disregard all Pumps=0

--- Goss_Swamp_021220.p01 (plan) ---

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Plan Title=100 Year Single
Version=Version 3.0.1  Mar 2001
Short Identifier=Plan01
Geom File=g01
Flow File=f01
Encroach Param=-1 ,10,10, 2
Encroach River=Goss Swamp
Encroach Reach=Reach - 1
Encroach Node=19500.0
       4      .7
Encroach Node=18998.8
       4      .7
Encroach Node=18289.7
       4      .7
Encroach Node=17279.5
       4      .7
Encroach Node=16761.1
       4      .7
Encroach Node=16251.8
       4      .7
Encroach Node=15664.9
       1    4900    5200
Encroach Node=15157.8
       4      .7
Encroach Node=15114.3
       4      .7
Encroach Node=15070.8
       4      .7
Encroach Node=14801.2
       4      .7
Encroach Node=14230.8
       4      .7
Encroach Node=13709.6
       4      .7
Encroach Node=13000.0
       4      .7
Encroach Node=12272.6
       4      .7
Encroach Node=11591.3
       1    4700    5150
Encroach Node=10812.4
       4      .7
Encroach Node=10291.6
       4      .7
Encroach Node=9473.9
       4      .7
Encroach Node=8820.5
       4      .7
Encroach Node=8138.6
       1    4950    5150
Encroach Node=7618.2
       1    4850    5100
Encroach Node=6931.6
       1    4850    5200
Encroach Node=6300.4
       4      .7
Encroach Node=5607.2
       1    4900    5300
Encroach Node=4916.8
       4      .7
Encroach Node=4276.6
       4      .7
Encroach Node=3577.3
       4      .7
UNET ZSATol= 0.1
UNET MaxInSteps= 20
UNET Convert EG Bridges=-1
Write Velocity= 0

--- Goss_Swamp_021220.f02 (steady flow) ---

Flow Title=Multi_Profile
Program Version=3.13
Number of Profiles= 7
Profile Names=10yr,25yr,50yr,500yr,100yr-10%,100yr-20%,100yr-35%
River Rch & RM=Goss Swamp,Reach - 1       ,19500.0
     824    1148    1432    2649    1916    2455    3000
River Rch & RM=Goss Swamp,Reach - 1       ,17279.5
    1014    1405    1747    3201    2306    2956    3612
River Rch & RM=Goss Swamp,Reach - 1       ,15157.8
    1106    1528    1898    3464    2492    3194    3903
River Rch & RM=Goss Swamp,Reach - 1       ,12272.6
    1189    1640    2035    3701    2659    3408    4164
River Rch & RM=Goss Swamp,Reach - 1       ,8820.5
    1264    1741    2158    3915    2810    3601    4400
River Rch & RM=Goss Swamp,Reach - 1       ,6300.4
    1341    1844    2284    4132    2962    3797    4639
River Rch & RM=Goss Swamp,Reach - 1       ,3577.3
    1400    1924    2381    4299    3080    3947    4822
Boundary for River Rch & Prof#=Goss Swamp,Reach - 1       , 1
Up Type= 0
Dn Type= 3
Dn Slope=0.0018
DSS Import GetInterval= 0
DSS Import GetPeak= 0
DSS Import FillOption= 0

--- Goss_Swamp_021220.f01 (steady flow) ---

Flow Title= 100 Year Single
Version=Version 3.0.1  Mar 2001
Number of Profiles= 2
Profile Names=100-Year,AFW
River Rch & RM=Goss Swamp,Reach - 1       ,19500.0
    1748    1748
River Rch & RM=Goss Swamp,Reach - 1       ,17279.5
    2126    2126
River Rch & RM=Goss Swamp,Reach - 1       ,15157.8
    2307    2307
River Rch & RM=Goss Swamp,Reach - 1       ,12272.6
    2470    2470
River Rch & RM=Goss Swamp,Reach - 1       ,8820.5
    2618    2618
River Rch & RM=Goss Swamp,Reach - 1       ,6300.4
    2768    2768
River Rch & RM=Goss Swamp,Reach - 1       ,3577.3
    2883    2883
Boundary for River Rch & Prof#=Goss Swamp,Reach - 1       , 1
Up Type= 0
Dn Type= 3
Dn Slope=.0018
Boundary for River Rch & Prof#=Goss Swamp,Reach - 1       , 2
Up Type= 0
Dn Type= 3
Dn Slope=.0018
DSS Import GetInterval= 0
DSS Import GetPeak= 0
DSS Import FillOption= 0

--- Goss_Swamp_021220.g01 (geometry) ---

Geom Title=Geom 01 by CodeH2 for Windows
Version=Version 3.0.1  Mar 2001

River Reach=Goss Swamp      ,Reach - 1
Reach XY= 30
        .9262037        .8507012        .9247456         .817939
        .8989351         .793161        .8803518        .7879989
        .8638328        .7363778        .8719175        .7082996
        .8566846        .6772248        .8676519        .6479779
        .8342763        .5159812        .7812781        .4372464
        .7535793        .4134737        .7492175        .3934088
        .7282799        .3702902        .7051613         .367673
        .6624133        .3470016        .6331877        .3470016
        .6227589        .3384372        .6192341        .3225485
        .5765422        .3248987        .5687085        .3147148
         .534046        .3125611        .5269956        .2984604
        .5230787         .252635        .3762021        .2173848
        .3456521        .1981142        .2905045        .2200479
         .267944         .219421        .2109166        .1739878
        .1692505        .1511789        .1266234        .0634807

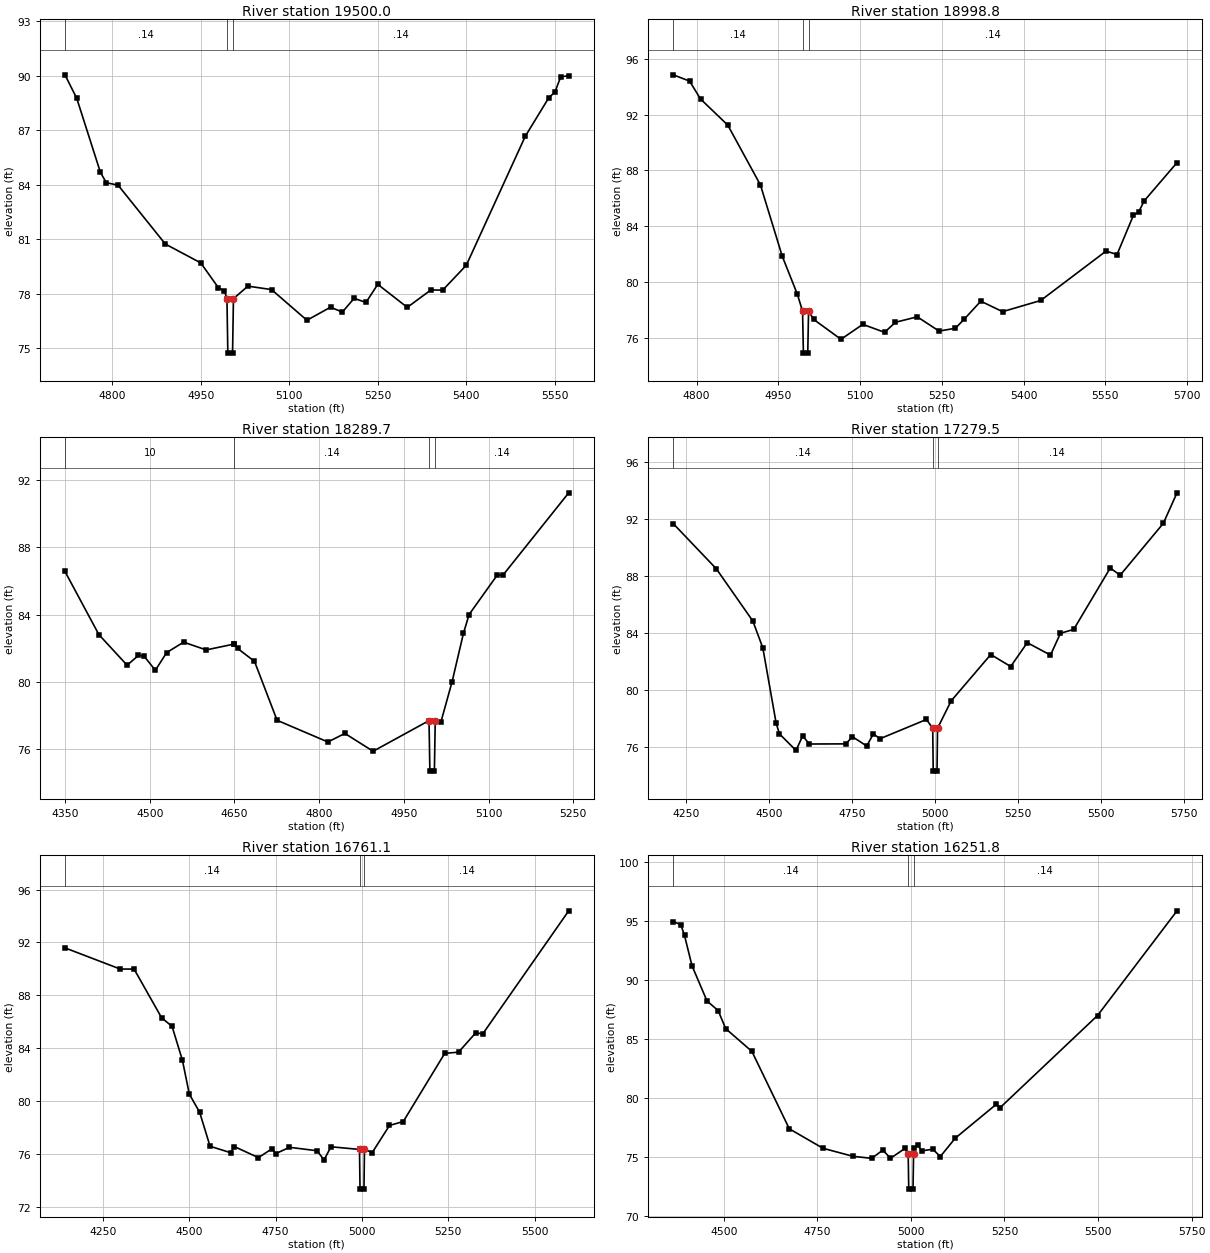
Type RM Length L Ch R = 1 ,19500.0 ,501.2,501.2,501.2
BEGIN DESCRIPTION:
Goss Swamp 23.0
END DESCRIPTION:
#Sta/Elev= 30
  4720.1   90.06  4740.1   88.76  4780.1   84.69  4790.1   84.12  4810.1   83.98
  4890.1   80.74  4950.1    79.7  4980.1   78.33  4990.1   78.16  4994.5   77.73
    4996   74.73    5004   74.73  5005.5   77.73    5030   78.42    5070   78.23
    5130   76.54    5170   77.26    5190   76.99    5210   77.75    5230   77.52
    5250   78.52    5300   77.25    5340   78.21    5360    78.2    5400   79.57
    5500   86.68    5540   88.81    5550    89.1    5560   89.95  5573.5   90.01
#Mann= 3 , 1 , 0
  4720.1     .14       0  4994.5    .048       0  5005.5     .14       0
Bank Sta=4994.5,5005.5
XS Rating Curve= 0
Exp/Cntr=.3,.1

Type RM Length L Ch R = 1 ,18998.8 ,709.1,709.1,709.1
BEGIN DESCRIPTION:
Goss Swamp 22.0
END DESCRIPTION:
#Sta/Elev= 29
  4757.2   94.85  4787.2    94.4  4807.2   93.12  4857.2   91.25  4917.2   86.96
  4957.2   81.86    4985   79.13  4994.5   77.92    4996   74.92    5004   74.92
  5005.5   77.92    5015   77.33    5065   75.91    5105   76.98    5145   76.41
    5165   77.13    5205   77.52    5245    76.5    5275    76.7  5291.6   77.37
  5321.6   78.64  5361.6   77.89  5431.6   78.69  5551.6   82.23  5571.6   81.98
  5601.6   84.78  5611.6   85.05  5621.6   85.83  5681.7   88.56
#Mann= 3 , 1 , 0
  4757.2     .14       0  4994.5    .048       0  5005.5     .14       0
Bank Sta=4994.5,5005.5
XS Rating Curve= 0
Exp/Cntr=.3,.1

Type RM Length L Ch R = 1 ,18289.7 ,1010.2,1010.2,1010.2
BEGIN DESCRIPTION:
Goss Swamp 21.0
END DESCRIPTION:
#Sta/Elev= 28
    4350   86.57    4410   82.82    4460      81    4480   81.58    4490   81.54
    4510    80.7    4530   81.75    4560   82.37    4600   81.91  4649.9   82.26
    4650   82.26  4655.5      82  4685.5   81.23  4725.5   77.73  4815.5   76.44
  4845.5   76.95  4895.5   75.89  4994.5   77.71    4996   74.71    5004   74.71
  5005.5   77.71  5015.4   77.61  5035.4   80.03  5055.4   82.89  5065.4   84.01
  5115.4   86.36  5125.4   86.35  5241.8   91.24
#Mann= 4 , 1 , 0
    4350      10       0  4649.9     .14       0  4994.5    .048       0
  5005.5     .14       0
Bank Sta=4994.5,5005.5
XS Rating Curve= 0
Exp/Cntr=.3,.1

Type RM Length L Ch R = 1 ,17279.5 ,518.4,518.4,518.4
BEGIN DESCRIPTION:
Goss Swamp 20.0
END DESCRIPTION:
#Sta/Elev= 30
  4210.7   91.66  4340.7   88.49  4450.7   84.83  4480.7   82.95  4520.7   77.69
  4530.7   76.93  4580.7   75.77  4600.7   76.79  4620.7   76.22  4730.7   76.23
  4750.7   76.73  4793.8   76.08  4813.8   76.93  4833.8   76.59  4973.8   77.94
  4992.7   77.32  4994.2   74.32  5005.7   74.32  5007.2   77.32  5048.2   79.24
  5167.7   82.49  5227.7   81.65  5277.7   83.32  5347.7   82.45  5377.7   83.98
  5417.7   84.25  5527.7   88.55  5557.7   88.05  5687.7   91.68    5729   93.82
#Mann= 3 , 1 , 0
  4210.7     .14       0  4992.7    .048       0  5007.2     .14       0
Bank Sta=4992.7,5007.2
XS Rating Curve= 0
Exp/Cntr=.3,.1

Type RM Length L Ch R = 1 ,16761.1 ,509.3,509.3,509.3
BEGIN DESCRIPTION:
Goss Swamp 19.5
END DESCRIPTION:
#Sta/Elev= 30
  4140.1   91.59  4300.1   89.99  4340.1   89.99  4420.1    86.3  4450.1   85.66
  4480.1    83.1  4500.1   80.54  4530.1   79.16  4560.1    76.6  4620.1   76.11
  4630.1   76.58  4700.1   75.74  4740.1   76.42  4750.1   76.04  4790.1   76.52
  4870.1   76.26  4890.1   75.56  4910.1   76.56  4992.8   76.36  4994.3   73.36
  5005.7   73.36  5007.2   76.36  5029.6   76.12  5079.6   78.17  5119.6   78.47
  5239.6   83.62  5279.6   83.71  5329.6   85.18  5349.6   85.09  5598.5   94.39
#Mann= 3 , 1 , 0
  4140.1     .14       0  4992.8    .048       0  5007.2     .14       0
Bank Sta=4992.8,5007.2
XS Rating Curve= 0
Exp/Cntr=.3,.1

Type RM Length L Ch R = 1 ,16251.8 ,586.9,586.9,586.9
BEGIN DESCRIPTION:
Goss Swamp 19.0
END DESCRIPTION:
#Sta/Elev= 29
  4365.3   94.93  4385.3   94.69  4395.3   93.76  4415.3    91.2  4455.3   88.22
  4485.3   87.39  4505.3   85.87  4575.3   83.94  4675.3   77.38  4765.3   75.73
  4845.3   75.05  4895.3   74.88  4925.3   75.58  4945.3   74.88  4985.3   75.74
  4992.8   75.27  4994.3   72.27  5005.7   72.27  5007.2   75.27  5008.6   75.73
  5018.6   76.01  5028.6   75.51  5058.6   75.65  5078.6   75.03  5118.6   76.59
  5228.6   79.47  5238.6   79.18  5498.6   86.98  5710.9   95.85
#Mann= 3 , 1 , 0
  4365.3     .14       0  4992.8    .048       0  5007.2     .14       0
Bank Sta=4992.8,5007.2
XS Rating Curve= 0
Exp/Cntr=.3,.1

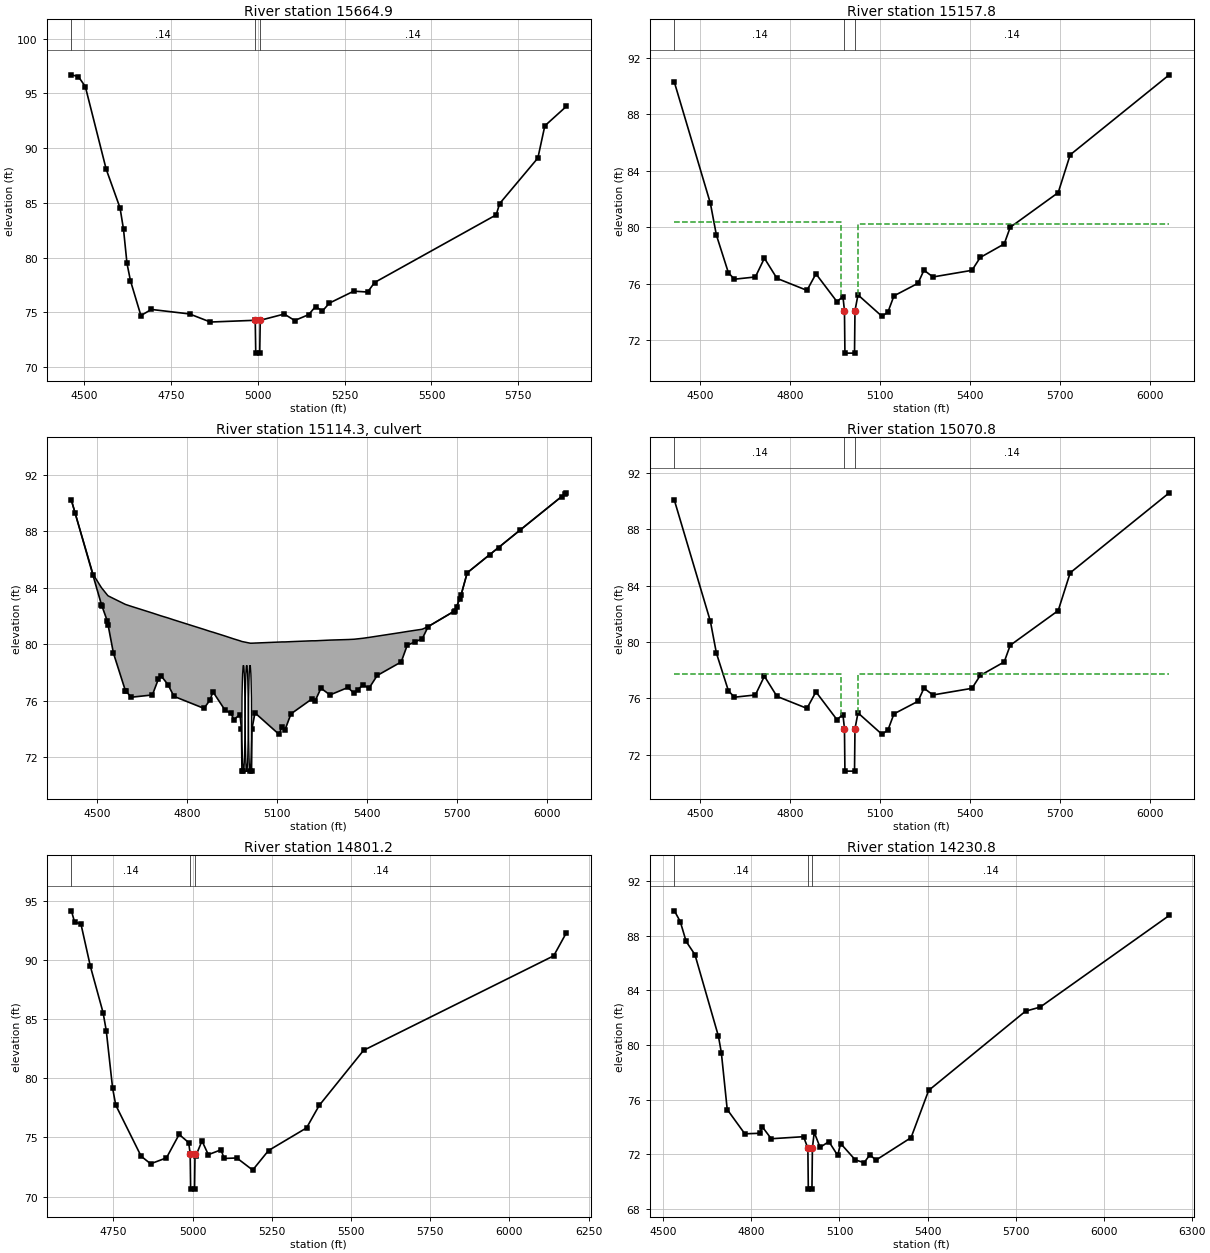
Type RM Length L Ch R = 1 ,15664.9 ,507.1,507.1,507.1
BEGIN DESCRIPTION:
Goss Swamp 18.0
END DESCRIPTION:
#Sta/Elev= 30
  4463.7    96.7  4483.7   96.54  4503.7   95.63  4563.7   88.09  4603.7   84.54
  4613.7   82.58  4623.7   79.47  4633.7   77.89  4663.7   74.71  4693.7   75.27
  4803.7   74.86  4863.7   74.12  4992.8   74.28  4994.3   71.28  5005.7   71.28
  5007.2   74.28  5076.3   74.85  5106.3   74.26  5146.3   74.79  5166.3   75.53
  5186.3   75.13  5206.3   75.85  5276.3   76.94  5316.3   76.86  5336.3   77.73
  5686.3   83.91  5696.3   84.94  5806.3    89.1  5826.3   92.04    5888   93.81
#Mann= 3 , 1 , 0
  4463.7     .14       0  4992.8    .048       0  5007.2     .14       0
Bank Sta=4992.8,5007.2
XS Rating Curve= 0
Exp/Cntr=.5,.3

Type RM Length L Ch R = 1 ,15157.8 ,87,87,87
BEGIN DESCRIPTION:
Upstream Section of Bridge/Culvert/Weir
END DESCRIPTION:
#Sta/Elev= 30
  4415.5   90.27  4535.5   81.69  4555.5   79.44  4595.5   76.77  4615.5   76.31
  4685.5   76.47  4715.5    77.8  4757.4   76.37  4857.4   75.52  4887.4   76.69
  4957.4   74.72  4977.4   75.08  4982.5   74.07    4984   71.07    5016   71.07
  5017.5   74.07  5027.5    75.2  5107.5   73.68  5127.5   73.99  5147.5   75.13
  5227.5   76.02  5247.5   76.95  5277.5   76.47  5407.5   76.94    5435   77.85
    5515   78.81    5535   79.99    5695   82.45    5735   85.13  6065.2    90.8
#Mann= 3 , 1 , 0
  4415.5     .14       0  4982.5    .048       0  5017.5     .14       0
#XS Ineff= 2 , 0
       0    4972    80.4    5028       0    80.2
Permanent Ineff=
       F       F
Bank Sta=4982.5,5017.5
XS Rating Curve= 0
Exp/Cntr=.5,.3

Type RM Length L Ch R = 2 ,15114.3 ,,,
BEGIN DESCRIPTION:
Bartee Bridge Rd-TOR
Structure ID: Bartee Bridge Rd
Approximate Survey Structure
END DESCRIPTION:
Bridge Culvert--1,0,-1,-1, 0
Deck Dist Width WeirC Skew NumUp NumDn MinLoCord MaxHiCord MaxSubmerge Is_Ogee
10,67,3,0, 47, 47, , , .95, 0, 1,1,,
  4415.5  4487.6  4515.5  4535.5  4537.6  4555.5  4595.5  4615.5  4685.5  4705.5
  4715.5  4737.4  4757.4  4857.4  4877.4  4887.4  4927.4  4947.4  4957.4  4977.4
  4982.5    4984  5011.6    5016  5017.5  5027.5  5107.5  5117.5  5127.5  5147.5
  5217.5  5227.5  5247.5  5277.5  5337.5  5357.5  5387.5  5407.5    5435    5515
    5535    5585    5605    5695    5715    5735  6065.2
    90.2   84.96   84.01   83.48   83.43   83.24   82.82   82.68   82.21   82.07
      82   81.86   81.72   81.05   80.91   80.85   80.58   80.44   80.37   80.24
    80.2   80.19   80.07   80.07   80.07   80.08   80.15   80.16   80.16   80.18
   80.24   80.24   80.26   80.29   80.33   80.35   80.42   80.48   80.57   80.83
    80.9   81.06   81.25   82.38   83.52   85.06   90.73
    90.2   84.87   82.81   81.62   81.38   79.37    76.7   76.24    76.4   77.53
   77.73   77.13    76.3   75.45   76.03   76.62   75.33   75.09   74.65   75.01
      74      71      71      71      74   75.13   73.61   74.12   73.92   75.06
   76.12   75.95   76.88    76.4   76.93   76.52   77.12   76.87   77.78   78.74
   79.92   80.38   81.25   82.38   83.52   85.06   90.73
  4415.5  4487.6  4515.5  4535.5  4537.6  4555.5  4595.5  4615.5  4685.5  4705.5
  4715.5  4737.4  4757.4  4857.4  4877.4  4887.4  4927.4  4947.4  4957.4  4977.4
  4982.5    4984  5011.6    5016  5017.5  5027.5  5107.5  5117.5  5127.5  5147.5
  5217.5  5227.5  5247.5  5277.5  5337.5  5357.5  5387.5  5407.5    5435    5515
    5535    5585    5605    5695    5715    5735  6065.2
   90.13   84.96   84.01   83.48   83.43   83.24   82.82   82.68   82.21   82.07
      82   81.86   81.72   81.05   80.91   80.85   80.58   80.44   80.37   80.24
    80.2   80.19   80.07   80.07   80.07   80.08   80.15   80.16   80.16   80.18
   80.24   80.24   80.26   80.29   80.33   80.35   80.42   80.48   80.57   80.83
    80.9   81.06   81.19   82.32   83.46      85   90.66
   90.05   84.72   82.66   81.47   81.23   79.22   76.55   76.09   76.25   77.38
   77.58   76.98   76.15    75.3   75.88   76.47   75.18   74.94    74.5   74.86
   73.85   70.85   70.85   70.85   73.85   74.98   73.46   73.97   73.77   74.91
   75.97    75.8   76.73   76.25   76.78   76.37   76.97   76.72   77.63   78.59
   79.77   80.23    81.1   82.23   83.37   84.91   90.58
BR Coef= 1 , 0 , 0 ,1.25, 0 ,,,.8,-1,2,0,
WSPro=,,,, 1 ,,,, 0 ,,,, 0 ,,,,-1 ,-1 ,-1 , 0 , 0 , 0 , 0 , 0
Culvert=3,7.5,10,67,.024,.7,1,34,2,71,4989,70.85,4989,Culvert #1  , 0 ,10
Culvert Bottom n=.024
Culvert=3,7.5,10,67,.024,.7,1,34,2,71,5000,70.85,5000,Culvert #2  , 0 ,10
Culvert Bottom n=.024
Culvert=3,7.5,10,67,.024,.7,1,34,2,71,5011,70.85,5011,Culvert #3  , 0 ,10
Culvert Bottom n=.024
BR U #Sta/Elev= 61
  4415.5    90.2  4427.6   89.31  4487.6   84.87  4515.5   82.81  4517.6   82.69
  4535.5   81.62  4537.6   81.38  4555.5   79.37  4595.5    76.7  4597.6   76.65
  4615.5   76.24  4685.5    76.4  4705.5   77.53  4715.5   77.73  4737.4   77.13
  4757.4    76.3  4857.4   75.45  4877.4   76.03  4887.4   76.62  4927.4   75.33
  4947.4   75.09  4957.4   74.65  4977.4   75.01  4982.5      74    4984      71
  4987.6      71  5011.6      71    5016      71  5017.5      74  5027.5   75.13
  5107.5   73.61  5117.5   74.12  5127.5   73.92  5147.5   75.06  5217.5   76.12
  5227.5   75.95  5247.5   76.88  5277.5    76.4  5337.5   76.93  5357.5   76.52
  5369.5   76.76  5387.5   77.12  5407.5   76.87    5435   77.78    5515   78.74
    5535   79.92  5559.5   80.15    5585   80.38    5605   81.25  5689.5   82.31
    5695   82.38  5699.5   82.64  5709.5   83.21    5715   83.52    5735   85.06
  5809.5   86.34  5839.5   86.85  5909.5   88.06  6049.5   90.46  6059.5   90.63
  6065.2   90.73
BR U #Mann= 3
  4415.5     .14  4982.5    .048  5017.5     .14
BR U Banks=4982.5,5017.5
BR D #Sta/Elev= 61
  4415.5   90.05  4427.6   89.16  4487.6   84.72  4515.5   82.66  4517.6   82.54
  4535.5   81.47  4537.6   81.23  4555.5   79.22  4595.5   76.55  4597.6    76.5
  4615.5   76.09  4685.5   76.25  4705.5   77.38  4715.5   77.58  4737.4   76.98
  4757.4   76.15  4857.4    75.3  4877.4   75.88  4887.4   76.47  4927.4   75.18
  4947.4   74.94  4957.4    74.5  4977.4   74.86  4982.5   73.85    4984   70.85
  4987.6   70.85  5011.6   70.85    5016   70.85  5017.5   73.85  5027.5   74.98
  5107.5   73.46  5117.5   73.97  5127.5   73.77  5147.5   74.91  5217.5   75.97
  5227.5    75.8  5247.5   76.73  5277.5   76.25  5337.5   76.78  5357.5   76.37
  5369.5   76.61  5387.5   76.97  5407.5   76.72    5435   77.63    5515   78.59
    5535   79.77  5559.5      80    5585   80.23    5605    81.1  5689.5   82.16
    5695   82.23  5699.5   82.49  5709.5   83.06    5715   83.37    5735   84.91
  5809.5   86.19  5839.5    86.7  5909.5   87.91  6049.5   90.31  6059.5   90.48
  6065.2   90.58
BR D #Mann= 3
  4415.5     .14  4982.5    .048  5017.5     .14
BR D Banks=4982.5,5017.5
BC Design=,, 0 ,, 0 ,,,,,,

Type RM Length L Ch R = 1 ,15070.8 ,269.6,269.6,269.6
BEGIN DESCRIPTION:
Downstream Section of Bridge/Culvert/Weir
END DESCRIPTION:
#Sta/Elev= 30
  4415.5   90.04  4535.5   81.46  4555.5   79.21  4595.5   76.54  4615.5   76.08
  4685.5   76.24  4715.5   77.57  4757.4   76.14  4857.4   75.29  4887.4   76.46
  4957.4   74.49  4977.4   74.85  4982.5   73.84    4984   70.84    5016   70.84
  5017.5   73.84  5027.5   74.97  5107.5   73.45  5127.5   73.76  5147.5    74.9
  5227.5   75.79  5247.5   76.72  5277.5   76.24  5407.5   76.71    5435   77.62
    5515   78.58    5535   79.76    5695   82.22    5735    84.9  6065.2   90.57
#Mann= 3 , 1 , 0
  4415.5     .14       0  4982.5    .048       0  5017.5     .14       0
#XS Ineff= 2 , 0
       0    4972    77.7    5028       0    77.7
Permanent Ineff=
       F       F
Bank Sta=4982.5,5017.5
XS Rating Curve= 0
Exp/Cntr=.5,.3

Type RM Length L Ch R = 1 ,14801.2 ,570.4,570.4,570.4
BEGIN DESCRIPTION:
Goss Swamp 17.5
END DESCRIPTION:
#Sta/Elev= 30
  4617.6   94.13  4627.6   93.18  4647.6   93.03  4677.6   89.43  4717.6   85.53
  4727.6   84.01  4747.6   79.16  4757.6   77.72  4837.6   73.41  4867.6   72.77
  4917.6   73.27  4957.6   75.25  4987.6   74.56  4992.4   73.63  4993.9   70.63
  5006.2   70.63  5007.7   73.63  5009.7    73.4  5029.7    74.7  5049.7   73.54
  5089.7   73.95  5099.7   73.22  5139.7   73.26  5189.7   72.24  5239.7   73.89
  5359.7    75.8  5399.7    77.7  5539.7   82.35  6139.7   90.33  6179.3   92.26
#Mann= 3 , 1 , 0
  4617.6     .14       0  4992.4    .048       0  5007.7     .14       0
Bank Sta=4992.4,5007.7
XS Rating Curve= 0
Exp/Cntr=.3,.1

Type RM Length L Ch R = 1 ,14230.8 ,521.2,521.2,521.2
BEGIN DESCRIPTION:
Goss Swamp 17.0
END DESCRIPTION:
#Sta/Elev= 30
  4537.5   89.83  4557.5   89.04  4577.5   87.59  4607.5   86.62  4687.5   80.65
  4697.5   79.44  4717.5   75.28  4777.5    73.5  4827.5   73.54  4837.5      74
  4867.5   73.14  4977.5   73.29  4992.3   72.45  4993.8   69.45  5006.2   69.45
  5007.7   72.45  5013.9   73.61  5033.9   72.51  5063.9   72.93  5093.9   71.92
  5103.9   72.79  5153.9   71.59  5183.9   71.39  5203.9   71.97  5223.9   71.57
  5343.9   73.22  5403.9   76.68  5733.9   82.48  5783.9   82.78  6223.6   89.49
#Mann= 3 , 1 , 0
  4537.5     .14       0  4992.3    .048       0  5007.7     .14       0
Bank Sta=4992.3,5007.7
XS Rating Curve= 0
Exp/Cntr=.3,.1

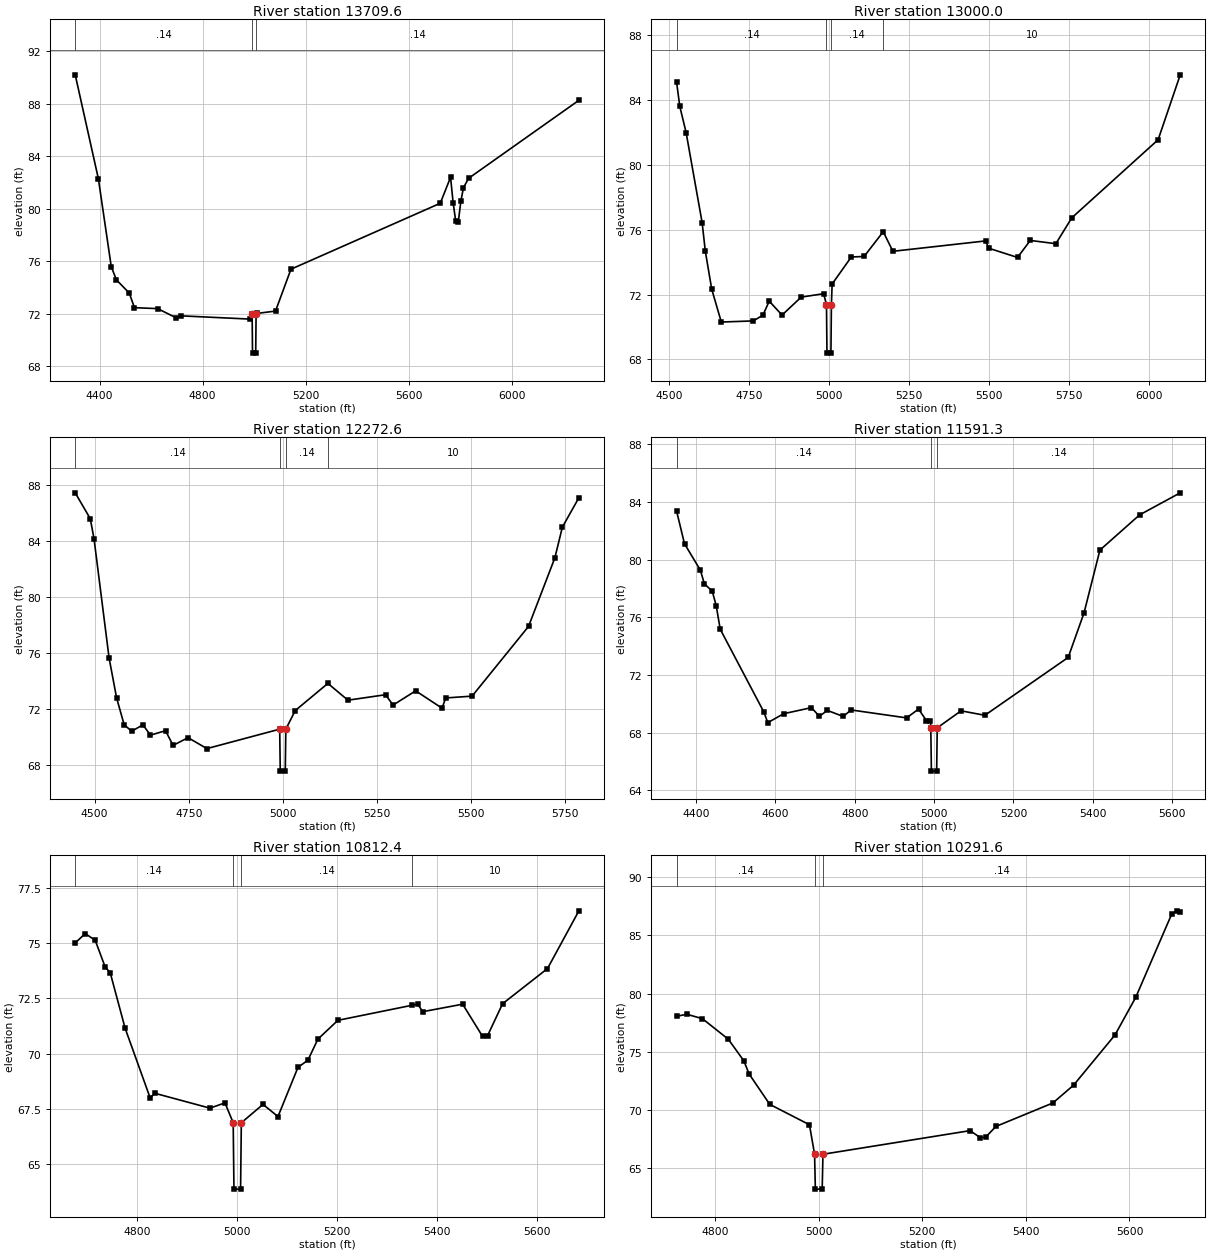
Type RM Length L Ch R = 1 ,13709.6 ,709.6,709.6,709.6
BEGIN DESCRIPTION:
Goss Swamp 16.0
END DESCRIPTION:
#Sta/Elev= 26
  4305.1   90.19  4395.1   82.27  4445.1   75.58  4465.1   74.58  4515.1   73.57
  4535.1   72.46  4625.1   72.39  4695.1   71.71  4715.1   71.84  4985.1   71.59
  4992.3      72  4993.8      69  5006.2      69  5007.7      72  5013.1   72.03
  5083.1    72.2  5143.1   75.39  5723.1   80.41  5763.1   82.39  5773.1   80.45
  5783.1   79.06  5793.1   78.98  5803.1   80.56  5813.1   81.59  5833.1   82.31
  6261.6   88.25
#Mann= 3 , 1 , 0
  4305.1     .14       0  4992.3    .048       0  5007.7     .14       0
Bank Sta=4992.3,5007.7
XS Rating Curve= 0
Exp/Cntr=.3,.1

Type RM Length L Ch R = 1 ,13000.0 ,727.4,727.4,727.4
BEGIN DESCRIPTION:
Goss Swamp 15.0
END DESCRIPTION:
#Sta/Elev= 30
  4523.2   85.13  4533.2   83.63  4553.2   81.99  4603.2   76.44  4613.2   74.67
  4633.2   72.33  4663.2    70.3  4763.2   70.37  4793.2   70.72  4813.2   71.59
  4853.2   70.73  4913.2   71.84  4983.2   72.05  4992.3   71.38  4993.8   68.38
  5006.2   68.38  5007.7   71.38    5010   72.65    5070   74.32    5110   74.35
  5169.9   75.88    5200   74.67    5490   75.31    5500   74.86    5590   74.29
    5630   75.34    5710   75.14    5760   76.74    6030   81.56  6099.2   85.57
#Mann= 4 , 1 , 0
  4523.2     .14       0  4992.3    .048       0  5007.7     .14       0
  5169.9      10       0
Bank Sta=4992.3,5007.7
XS Rating Curve= 0
Exp/Cntr=.3,.1

Type RM Length L Ch R = 1 ,12272.6 ,681.3,681.3,681.3
BEGIN DESCRIPTION:
Goss Swamp 14.0
END DESCRIPTION:
#Sta/Elev= 30
  4448.3   87.43  4488.3   85.58  4498.3   84.14  4538.3   75.63  4558.3   72.77
  4578.3   70.86  4598.3   70.39  4628.3   70.85  4648.3   70.11  4688.3   70.43
  4708.3   69.38  4748.3   69.93  4798.3   69.15  4991.8   70.54  4993.3   67.54
  5006.6   67.54  5008.1   70.54  5033.2   71.87  5119.9   73.81  5173.2   72.61
  5273.2      73  5293.2   72.26  5353.2   73.28  5423.2   72.04  5433.2   72.77
  5503.2    72.9  5653.2   77.88  5723.2   82.78  5743.2   84.98  5787.1   87.08
#Mann= 4 , 1 , 0
  4448.3     .14       0  4991.8    .048       0  5008.1     .14       0
  5119.9      10       0
Bank Sta=4991.8,5008.1
XS Rating Curve= 0
Exp/Cntr=.3,.1

Type RM Length L Ch R = 1 ,11591.3 ,778.9,778.9,778.9
BEGIN DESCRIPTION:
Goss Swamp 13.0
END DESCRIPTION:
#Sta/Elev= 30
  4350.9   83.37  4370.9    81.1  4410.9   79.27  4420.9   78.33  4440.9   77.81
  4450.9    76.8  4460.9   75.18  4570.9   69.44  4580.9    68.7  4620.9   69.32
  4690.9   69.74  4710.9   69.14  4730.9   69.55  4770.9   69.13  4790.9   69.58
  4930.9   69.03  4960.9   69.64  4980.9   68.84  4990.9   68.83  4991.8   68.34
  4993.3   65.34  5006.6   65.34    5008   68.34  5068.1   69.52  5128.1   69.21
  5338.1   73.22  5378.1   76.31  5418.1   80.66  5518.1    83.1  5620.6   84.63
#Mann= 3 , 1 , 0
  4350.9     .14       0  4991.8    .048       0    5008     .14       0
Bank Sta=4991.8,5008
XS Rating Curve= 0
Exp/Cntr=.3,.1

Type RM Length L Ch R = 1 ,10812.4 ,520.8,520.8,520.8
BEGIN DESCRIPTION:
Goss Swamp 12.0
END DESCRIPTION:
#Sta/Elev= 29
  4675.3      75  4695.3   75.42  4715.3   75.12  4735.3   73.91  4745.3   73.66
  4775.3   71.14  4825.3      68  4835.3    68.2  4945.3   67.53  4975.3   67.77
  4991.8   66.87  4993.3   63.87  5006.6   63.87  5008.1   66.87  5051.5    67.7
  5081.5   67.15  5121.5   69.37  5141.5    69.7  5161.5   70.65  5201.5    71.5
  5349.9   72.18  5361.5   72.23  5371.5   71.89  5451.5   72.23  5491.5   70.77
  5501.5   70.81  5531.5   72.25  5621.5   73.84  5684.4   76.45
#Mann= 4 , 1 , 0
  4675.3     .14       0  4991.8    .048       0  5008.1     .14       0
  5349.9      10       0
Bank Sta=4991.8,5008.1
XS Rating Curve= 0
Exp/Cntr=.3,.1

Type RM Length L Ch R = 1 ,10291.6 ,817.7,817.7,817.7
BEGIN DESCRIPTION:
Goss Swamp 11.0
END DESCRIPTION:
#Sta/Elev= 23
  4725.4   78.05  4745.4   78.22  4775.4   77.84  4825.4   76.07  4855.4   74.21
  4865.4   73.09  4905.4   70.47    4982   68.72  4991.9   66.18  4993.4   63.18
  5006.6   63.18  5008.1   66.18    5292   68.21    5312   67.61    5322   67.64
    5342   68.57    5452   70.59    5492   72.12    5572   76.44    5612   79.67
    5682   86.89    5692   87.12    5698   86.98
#Mann= 3 , 1 , 0
  4725.4     .14       0  4991.9    .048       0  5008.1     .14       0
Bank Sta=4991.9,5008.1
XS Rating Curve= 0
Exp/Cntr=.3,.1

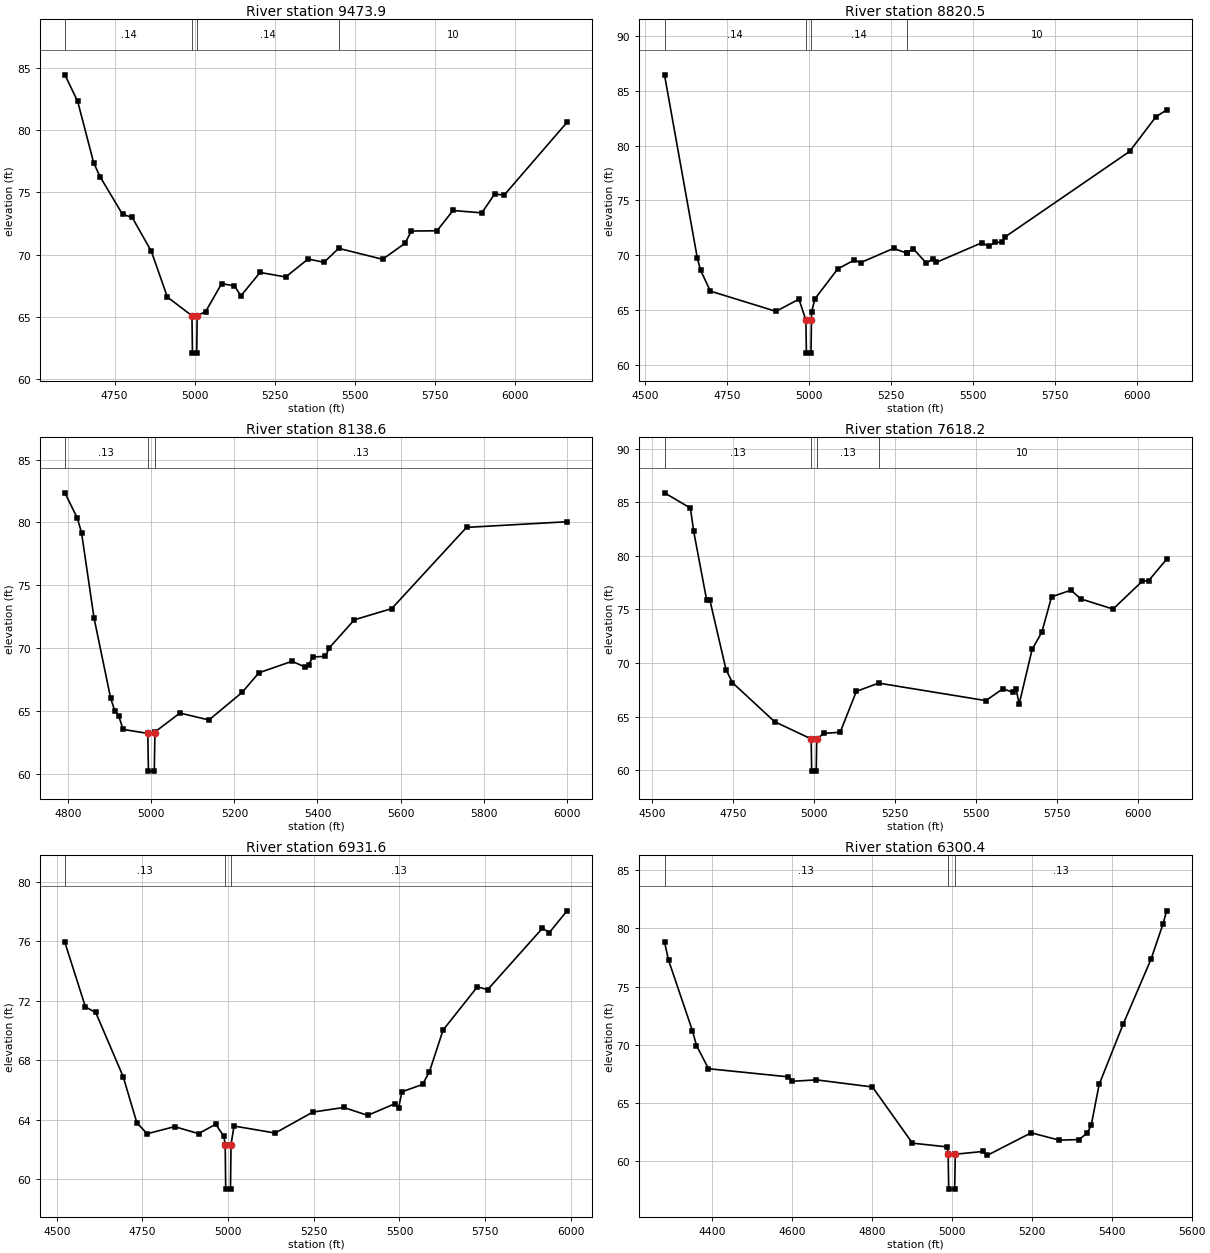
Type RM Length L Ch R = 1 ,9473.9  ,653.4,653.4,653.4
BEGIN DESCRIPTION:
Goss Swamp 10.0
END DESCRIPTION:
#Sta/Elev= 30
  4594.9   84.45  4634.9   82.31  4684.9   77.37  4704.9   76.26  4774.9   73.24
  4804.9      73  4864.9   70.27  4914.9    66.6  4991.8   65.09  4993.3   62.09
  5006.6   62.09  5008.1   65.09  5034.5   65.43  5084.5   67.67  5124.5    67.5
  5144.5   66.69  5204.5   68.57  5284.5   68.21  5354.5   69.65  5404.5   69.39
  5449.9   70.51  5587.1   69.63  5657.1   70.91  5677.1    71.9  5757.1   71.92
  5807.1   73.55  5897.1   73.36  5937.1   74.87  5967.1   74.79  6163.1   80.63
#Mann= 4 , 1 , 0
  4594.9     .14       0  4991.8    .048       0  5008.1     .14       0
  5449.9      10       0
Bank Sta=4991.8,5008.1
XS Rating Curve= 0
Exp/Cntr=.3,.1

Type RM Length L Ch R = 1 ,8820.5  ,681.9,681.9,681.9
BEGIN DESCRIPTION:
Goss Swamp 9.0
END DESCRIPTION:
#Sta/Elev= 30
  4560.3   86.43  4660.3   69.77  4670.3   68.65  4700.3   66.75  4900.3   64.91
  4970.3   66.02  4991.5   64.11    4993   61.11    5007   61.11  5008.5   64.11
  5008.8   64.84  5018.8   66.04  5088.8   68.78  5138.8   69.57  5158.8   69.35
  5258.8   70.64  5298.8   70.21  5299.9   70.23  5318.8   70.61  5358.8    69.3
  5378.8    69.7  5388.8   69.36  5528.8   71.16  5548.8   70.82  5568.8    71.2
  5588.8   71.19  5598.8   71.68  5978.8   79.46  6058.8   82.61  6091.5   83.23
#Mann= 4 , 1 , 0
  4560.3     .14       0  4991.5    .048       0  5008.5     .14       0
  5299.9      10       0
Bank Sta=4991.5,5008.5
XS Rating Curve= 0
Exp/Cntr=.3,.1

Type RM Length L Ch R = 1 ,8138.6  ,520.4,520.4,520.4
BEGIN DESCRIPTION:
Goss Swamp 8.0
END DESCRIPTION:
#Sta/Elev= 27
  4791.9   82.35  4821.9   80.33  4831.9   79.19  4861.9   72.42  4901.9   66.03
  4911.9   65.02  4921.9   64.56  4931.9   63.53  4991.5   63.21    4993   60.21
  5007.1   60.21  5008.6   63.21  5008.8   63.33  5068.8   64.83  5138.8   64.28
  5218.8   66.48  5258.8   68.03  5338.8   68.95  5368.8   68.51  5378.8   68.68
  5388.8   69.29  5418.8   69.34  5428.8   70.03  5488.8   72.25  5578.8   73.14
  5758.8    79.6  6000.7   80.05
#Mann= 3 , 1 , 0
  4791.9     .13       0  4991.5    .047       0  5008.6     .13       0
Bank Sta=4991.5,5008.6
XS Rating Curve= 0
Exp/Cntr=.3,.1

Type RM Length L Ch R = 1 ,7618.2  ,686.6,686.6,686.6
BEGIN DESCRIPTION:
Goss Swamp 7.5
END DESCRIPTION:
#Sta/Elev= 30
  4538.3   85.87  4618.3   84.45  4628.3   82.31  4668.3   75.92  4678.3    75.9
  4728.3    69.4  4748.3   68.18  4878.3   64.55  4991.5   62.94    4993   59.94
  5007.1   59.94  5008.6   62.94  5031.1   63.46  5081.1   63.56  5131.1   67.37
  5199.9   68.14  5531.1   66.51  5584.3   67.62  5614.3   67.28  5624.3   67.61
  5634.3   66.21  5674.3   71.29  5704.3   72.89  5734.3   76.18  5794.3    76.8
  5824.3   75.99  5924.3   75.04  6014.3   77.63  6034.3   77.69  6089.7   79.68
#Mann= 4 , 1 , 0
  4538.3     .13       0  4991.5    .047       0  5008.6     .13       0
  5199.9      10       0
Bank Sta=4991.5,5008.6
XS Rating Curve= 0
Exp/Cntr=.3,.1

Type RM Length L Ch R = 1 ,6931.6  ,631.2,631.2,631.2
BEGIN DESCRIPTION:
Goss Swamp 7.0
END DESCRIPTION:
#Sta/Elev= 30
  4523.8   75.93  4583.8   71.58  4613.8   71.21  4693.8   66.89  4733.8   63.78
  4763.8   63.04  4843.8   63.52  4913.8   63.05  4963.8   63.68  4987.3   62.88
  4991.5   62.31    4993   59.31    5007   59.31  5008.5   62.31  5017.3   63.56
  5137.3   63.09  5247.3    64.5  5337.3   64.81  5407.3   64.28  5487.3   65.07
  5497.3   64.76  5507.3   65.87  5567.3   66.36  5587.3   67.21  5627.3   70.03
  5727.3   72.94  5757.3   72.75  5917.3   76.89  5937.3   76.59  5988.8   78.06
#Mann= 3 , 1 , 0
  4523.8     .13       0  4991.5    .047       0  5008.5     .13       0
Bank Sta=4991.5,5008.5
XS Rating Curve= 0
Exp/Cntr=.3,.1

Type RM Length L Ch R = 1 ,6300.4  ,693.2,693.2,693.2
BEGIN DESCRIPTION:
Goss Swamp 6.0
END DESCRIPTION:
#Sta/Elev= 27
  4281.8   78.84  4291.8   77.28  4351.8   71.19  4361.8   69.93  4391.8   67.94
  4591.8   67.24  4601.8   66.86  4661.8   66.98  4801.8   66.37  4901.8   61.54
  4988.7   61.22    4991   60.59  4992.5   57.59  5007.4   57.59  5008.9   60.59
  5078.7   60.83  5088.7   60.49  5198.7   62.43  5268.7    61.8  5318.7   61.85
  5338.7   62.42  5348.7   63.06  5368.7   66.59  5428.7   71.77  5498.7   77.38
  5528.7   80.42  5537.3   81.51
#Mann= 3 , 1 , 0
  4281.8     .13       0    4991    .047       0  5008.9     .13       0
Bank Sta=4991,5008.9
XS Rating Curve= 0
Exp/Cntr=.3,.1

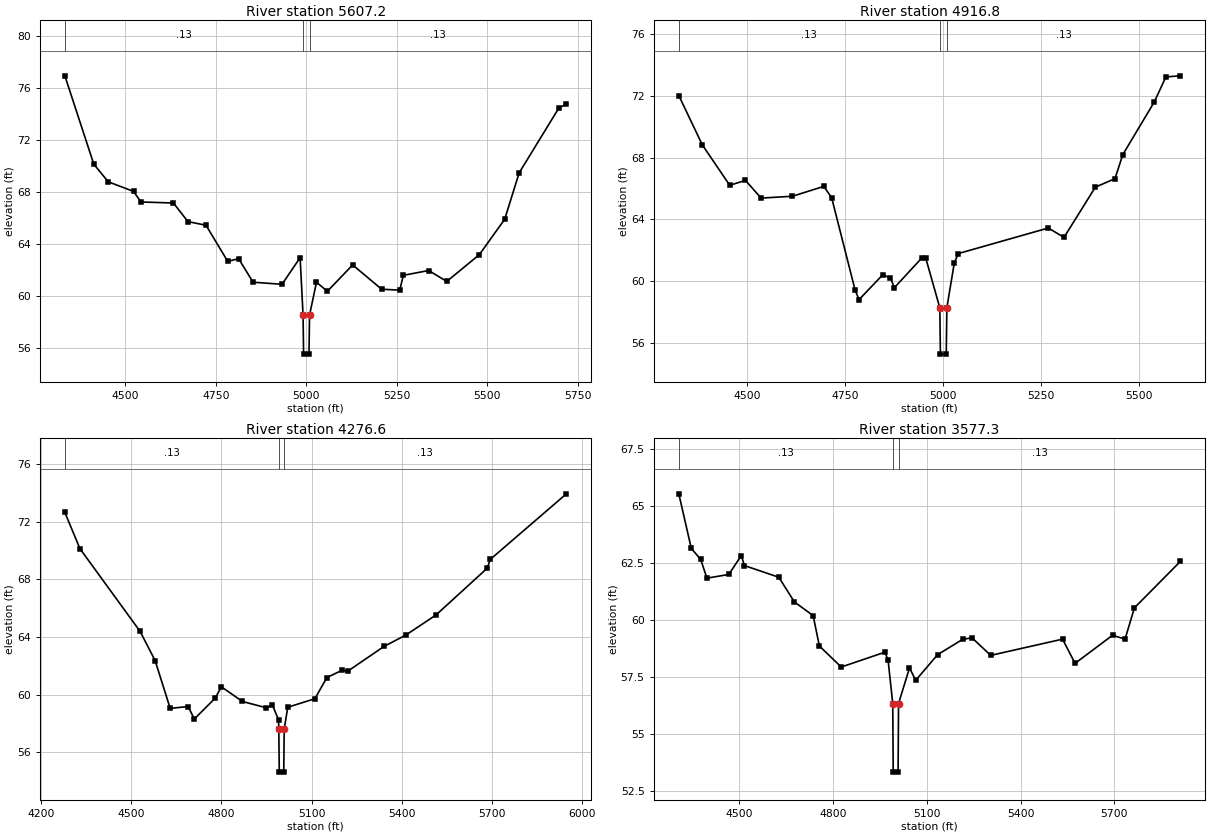
Type RM Length L Ch R = 1 ,5607.2  ,690.4,690.4,690.4
BEGIN DESCRIPTION:
Goss Swamp 5.0
END DESCRIPTION:
#Sta/Elev= 30
  4332.9    76.9  4412.9    70.1  4452.9   68.75  4522.9   68.01  4542.9    67.2
  4632.9   67.12  4672.9   65.69  4722.9   65.41  4782.9   62.63  4812.9   62.84
  4852.9   61.03  4932.9   60.87  4982.9   62.92    4991    58.5  4992.5    55.5
  5007.4    55.5  5008.9    58.5  5028.1   61.03  5058.1   60.33  5128.1   62.36
  5208.1   60.49  5258.1   60.42  5268.1   61.56  5338.1   61.93  5388.1   61.09
  5478.1   63.15  5548.1   65.87  5588.1   69.44  5698.1   74.44  5718.6   74.72
#Mann= 3 , 1 , 0
  4332.9     .13       0    4991    .047       0  5008.9     .13       0
Bank Sta=4991,5008.9
XS Rating Curve= 0
Exp/Cntr=.3,.1

Type RM Length L Ch R = 1 ,4916.8  ,640.2,640.2,640.2
BEGIN DESCRIPTION:
Goss Swamp 4.0
END DESCRIPTION:
#Sta/Elev= 29
  4325.1   72.02  4385.1   68.82  4455.1    66.2  4495.1   66.52  4535.1   65.37
  4615.1   65.49  4695.1   66.13  4715.1   65.39  4775.1   59.38  4785.1   58.79
  4845.1   60.39  4865.1   60.19  4875.1   59.56  4945.1   61.49  4955.1   61.48
    4991   58.25  4992.5   55.25  5007.4   55.25  5008.9   58.25  5027.8   61.14
  5037.8   61.77  5267.8   63.43  5307.8   62.82  5387.8   66.08  5437.8   66.63
  5457.8   68.19  5537.8   71.59  5567.8   73.23  5604.6    73.3
#Mann= 3 , 1 , 0
  4325.1     .13       0    4991    .047       0  5008.9     .13       0
Bank Sta=4991,5008.9
XS Rating Curve= 0
Exp/Cntr=.3,.1

Type RM Length L Ch R = 1 ,4276.6  ,699.3,699.3,699.3
BEGIN DESCRIPTION:
Goss Swamp 3.0
END DESCRIPTION:
#Sta/Elev= 28
  4280.1   72.64  4330.1   70.13  4530.1   64.39  4580.1   62.36  4630.1   59.05
  4690.1   59.18  4710.1   58.31  4780.1   59.77  4800.1   60.55  4870.1   59.53
  4950.1   59.09  4970.1   59.28  4990.1   58.26  4991.1   57.63  4992.6   54.63
  5007.5   54.63    5009   57.63  5020.9   59.13  5110.9   59.72  5150.9   61.19
  5200.9   61.69  5220.9   61.64  5340.9   63.35  5413.6   64.14  5513.6   65.53
  5683.6   68.77  5693.6   69.38  5946.8   73.93
#Mann= 3 , 1 , 0
  4280.1     .13       0  4991.1    .047       0    5009     .13       0
Bank Sta=4991.1,5009
XS Rating Curve= 0
Exp/Cntr=.3,.1

Type RM Length L Ch R = 1 ,3577.3  ,0,0,0
BEGIN DESCRIPTION:
Goss Swamp 1.0
END DESCRIPTION:
#Sta/Elev= 30
  4305.9   65.52  4345.9   63.13  4375.9   62.65  4395.9   61.83  4465.9   61.99
  4505.9   62.82  4515.9   62.38  4625.9   61.87  4675.9   60.79  4735.9   60.19
  4755.9   58.86  4825.9   57.94  4965.9   58.59  4975.9   58.23  4990.7   56.34
  4992.2   53.34  5007.8   53.34  5009.3   56.34  5044.3    57.9  5064.3   57.36
  5134.3   58.48  5214.3   59.15  5244.3   59.22  5304.3   58.45  5534.3   59.16
  5574.3    58.1  5694.3   59.33  5734.3   59.16  5764.3   60.53  5911.3   62.56
#Mann= 3 , 1 , 0
  4305.9     .13       0  4990.7    .047       0  5009.3     .13       0
Bank Sta=4990.7,5009.3
XS Rating Curve= 0
Exp/Cntr=.3,.1

Chan Stop Cuts=-1