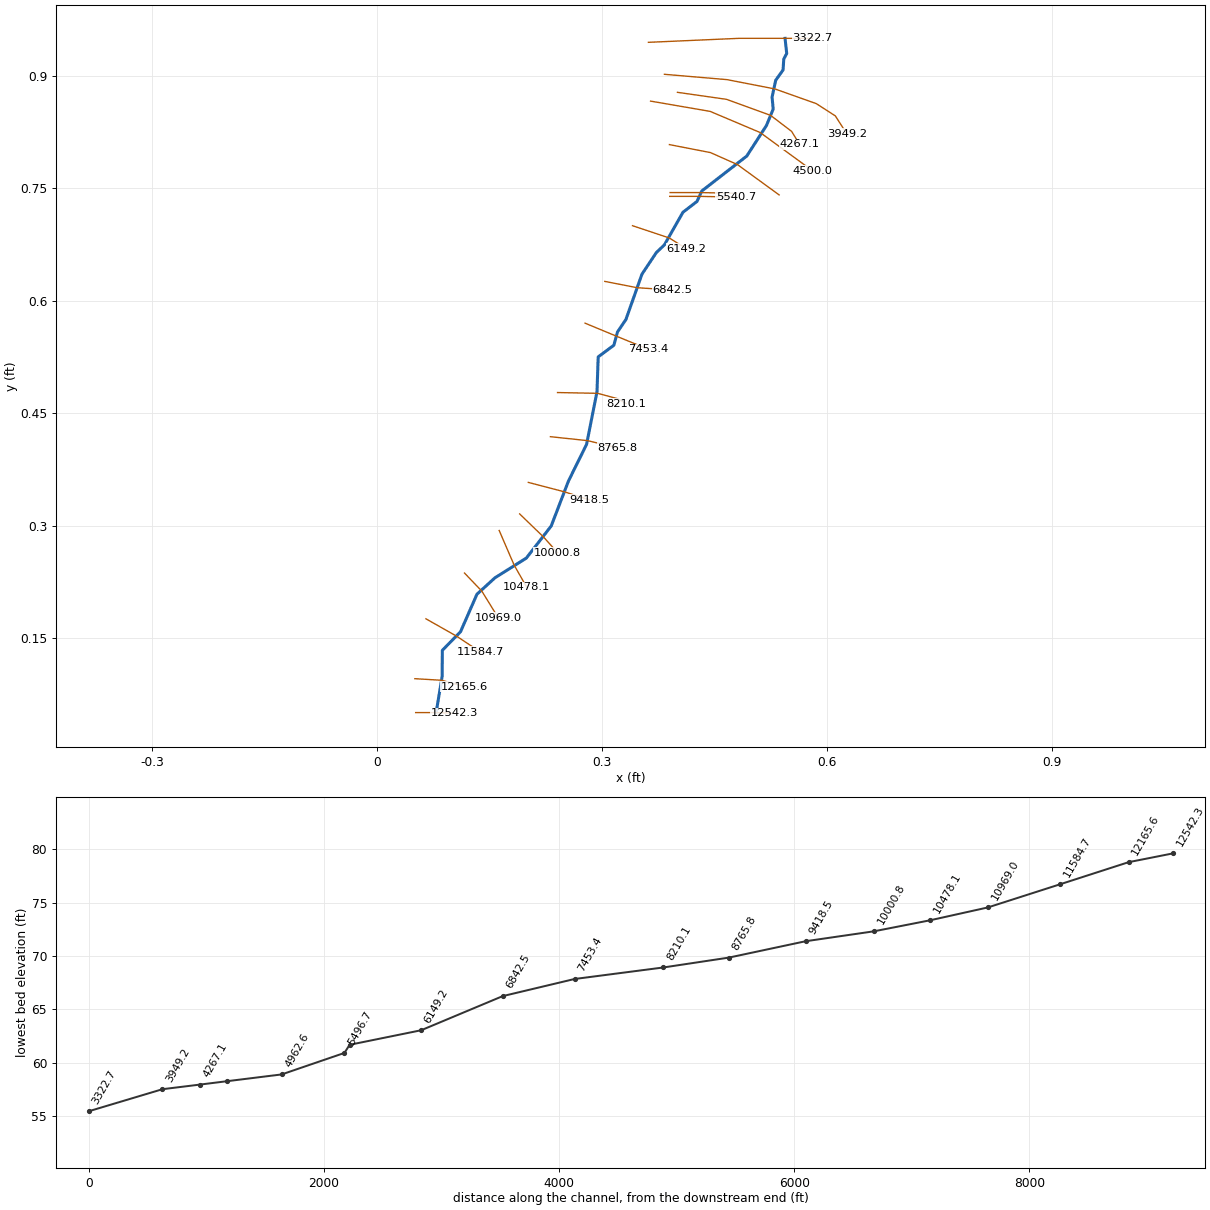
--- Ivy_Branch_021220.prj (project) ---

Proj Title=Ivy Branch
Current Plan=p02
Default Exp/Contr=0.3,0.1
English Units
Geom File=g01
Flow File=f02
Flow File=f01
Plan File=p02
Plan File=p01
Y Axis Title=Elevation
X Axis Title(PF)=Main Channel Distance
X Axis Title(XS)=Station
BEGIN DESCRIPTION:
NEUSE RIVER BASIN
Little Contentnea Creek Sub-basin
IVY BRANCH
(Flood Hazard, Floodway) Model
Prepared by: Andrew J. Bonner   Date: 11/26/2002
Watershed Concepts
3333 Regency Pkwy
Cary, North Carolina 27511
END DESCRIPTION:
DSS Export Rating Curves= 0
DSS Export Rating Curve Sorted= 0
DSS Export Volume Flow Curves= 0
DXF OffsetX= 0
DXF OffsetY= 0
DXF ScaleX= 1
DXF ScaleY= 10

--- Ivy_Branch_021220.p02 (plan) ---

Plan Title=Multi Profile
Program Version=4.00
Short Identifier=Multi Plan
Geom File=g01
Flow File=f02
Subcritical Flow
K Sum by GR= 0
Std Step Tol= 0.01
Critical Tol= 0.01
Num of Std Step Trials= 20
Max Error Tol= 0.3
Flow Tol Ratio= 0.001
Split Flow NTrial= 30
Split Flow Tol= 0.02
Split Flow Ratio= 0.02
Log Output Level= 0
Friction Slope Method= 1
Unsteady Friction Slope Method= 2
Unsteady Bridges Friction Slope Method= 1
Parabolic Critical Depth
Global Vel Dist= 0 , 0 , 0
Global Log Level= 0
CheckData=True
Encroach Param=-1 ,10,10, 2
Computation Interval=1HOUR
Output Interval=1HOUR
Run HTab= 0
Run UNet= 0
Run PostProcess= 0
Run WQNet= 0
UNET Theta= 1
UNET Theta Warmup= 1
UNET ZTol= 0.02
UNET ZSATol= 0.1
UNET MxIter= 20
UNET MaxInSteps= 20
UNET DtIC= 0
UNET DtMin= 0
UNET MaxCRTS= 20
UNET WFStab= 2
UNET SFStab= 1
UNET WFX= 1
UNET SFX= 1
UNET DSS MLevel= 4
UNET DZMax Abort= 100
UNET Convert EG Bridges=-1
UNET Use Existing IB Tables=-1
UNET Froude Reduction=False
UNET Froude Limit= 1
UNET Froude Power= 10
UNET Time Slicing=0,0, 5
Instantaneous Interval=1HOUR
Write IC File= 0
Echo Input=False
Echo Output=False
Write Detailed= 0
Detailed Automatic Start=False, 10
WQ ULTIMATE=-1
WQ Max Comp Step=1HOUR
WQ Output Interval=15MIN
WQ Output Selected Increments= 0
WQ Output face flow=0
WQ Output face velocity=0
WQ Output face area=0
WQ Output face dispersion=0
WQ Output cell volume=0
WQ Output cell surface area=0
WQ Output cell continuity=0
WQ Output face conc=0
WQ Output face dconc_dx=0
WQ Output face courant=0
WQ Output face peclet=0
WQ Output face adv mass=0
WQ Output face disp mass=0
WQ Output cell mass=0
WQ Output cell source sink temp=0
WQ Output cell source sink nsm=0
WQ Output MaxMinRange=-1
WQ Daily Max Min Mean=-1
WQ Daily Range=0
WQ Daily Time=0
WQ Create Restart=0
WQ Fixed Restart=0
WQ System Summary=False
Sorting and Armoring Iterations= 10
XS Update Threshold= 0.02
Hydraulics Update Threshold= 0.02
Energy Slope Method= 1
Volume Change Method= 0
XS Weighting Method= 0
Number of US Weighted Cross Sections= 1
Number of DS Weighted Cross Sections= 1
Upstream XS Weight=0.25
Main XS Weight=0.5
Downstream XS Weight=0.25
Number of DS XS's Weighted with US Boundary= 1
Upstream Boundary Weight= 1
Weight of XSs Associated with US Boundary= 0
Number of US XS's Weighted with DS Boundary= 1
Downstream Boundary Weight= 0.5
Weight of XSs Associated with DS Boundary= 0.5
Sediment Output Level= 4
Mass or Volume Output= 0
Output Increment Type= 1
Profile and TS Output Increment= 10
XS Output Flag= 0
XS Output Increment= 10
Disregard all LS=0
Disregard all Conn=0
Disregard all Breaches=0
Disregard all Pumps=0

--- Ivy_Branch_021220.p01 (plan) ---

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Plan Title=100 Year Single
Version=Version 3.0.1  Mar 2001
Short Identifier=Plan01
Geom File=g01
Flow File=f01
Encroach River=Ivy Branch
Encroach Reach=Reach - 1
Encroach Node=12542.3
       4      .7
Encroach Node=12165.6
       4      .7
Encroach Node=11584.7
       4      .7
Encroach Node=10969.0
       4      .7
Encroach Node=10478.1
       4      .7
Encroach Node=10000.8
       4      .7
Encroach Node=9418.5
       4      .7
Encroach Node=8765.8
       4      .7
Encroach Node=8210.1
       4      .7
Encroach Node=7453.4
       4      .7
Encroach Node=6842.5
       4      .7
Encroach Node=6149.2
       4      .7
Encroach Node=5540.7
       4      .7
Encroach Node=5518.7
       4      .7
Encroach Node=5496.7
       4      .7
Encroach Node=4962.6
       4      .7
Encroach Node=4500.0
       4      .7
Encroach Node=4267.1
       1    4950    5220
Encroach Node=3949.2
       1    4885    5275
Encroach Node=3322.7
       1    4875    5140
Write Velocity= 0

--- Ivy_Branch_021220.f02 (steady flow) ---

Flow Title=Multi Profile
Program Version=4.00
Number of Profiles= 7
Profile Names=10yr,25yr,50yr,500yr,100yr-10%,100yr-20%,100yr-35%
River Rch & RM=Ivy Branch,Reach - 1       ,12542.3
     446     631     794    1510    1104    1416    1730
River Rch & RM=Ivy Branch,Reach - 1       ,9418.5
     587     825    1035    1943    1414    1812    2214
River Rch & RM=Ivy Branch,Reach - 1       ,6842.5
     882    1226    1528    2817    2035    2608    3187
Boundary for River Rch & Prof#=Ivy Branch,Reach - 1       , 1
Up Type= 0
Dn Type= 3
Dn Slope=0.0033
Boundary for River Rch & Prof#=Ivy Branch,Reach - 1       , 2
Up Type= 0
Dn Type= 3
Dn Slope=0.0033
Boundary for River Rch & Prof#=Ivy Branch,Reach - 1       , 3
Up Type= 0
Dn Type= 3
Dn Slope=0.0033
Boundary for River Rch & Prof#=Ivy Branch,Reach - 1       , 4
Up Type= 0
Dn Type= 3
Dn Slope=0.0033
Boundary for River Rch & Prof#=Ivy Branch,Reach - 1       , 5
Up Type= 0
Dn Type= 3
Dn Slope=0.0033
Boundary for River Rch & Prof#=Ivy Branch,Reach - 1       , 6
Up Type= 0
Dn Type= 3
Dn Slope=0.0033
Boundary for River Rch & Prof#=Ivy Branch,Reach - 1       , 7
Up Type= 0
Dn Type= 3
Dn Slope=0.0033
DSS Import GetInterval= 0
DSS Import GetPeak= 0
DSS Import FillOption= 0

--- Ivy_Branch_021220.f01 (steady flow) ---

Flow Title= 100 Year Single
Version=Version 3.0.1  Mar 2001
Number of Profiles= 2
Profile Names=100-Year,AFW
River Rch & RM=Ivy Branch,Reach - 1       ,12542.3
     978     978
River Rch & RM=Ivy Branch,Reach - 1       ,9418.5
    1269    1269
River Rch & RM=Ivy Branch,Reach - 1       ,6842.5
    1863    1863
Boundary for River Rch & Prof#=Ivy Branch,Reach - 1       , 1
Up Type= 0
Dn Type= 3
Dn Slope=.0033
Boundary for River Rch & Prof#=Ivy Branch,Reach - 1       , 2
Up Type= 0
Dn Type= 1
Dn Known WS=64.62
DSS Import GetInterval= 0
DSS Import GetPeak= 0
DSS Import FillOption= 0

--- Ivy_Branch_021220.g01 (geometry) ---

Geom Title=Geom 01 by CodeH2 for Windows

River Reach=Ivy Branch,Reach - 1
Reach XY= 30
   .078362678382   .051044419620   .086467034655   .099777705518
   .086572829580   .134012245637   .110902174540   .158854289079
   .132779634925   .208837159433   .156875300986   .230790187621
   .198639882071   .257027328973   .231838561991   .299863810285
   .254862327825   .359834419090   .278957993886   .408560538744
   .292879908441   .478704899053   .294485433619   .525288380834
   .315368886743   .540816983149   .320187787439   .558487060755
   .331432276590   .575086400715   .352850517246   .635591797052
   .372126120029   .664506363808   .382835821648   .674680115314
   .407466275241   .718051384158   .426207090492   .732509248827
   .432632678947   .746430000801   .492603287752   .793014645163
   .518840429104   .833708488603   .527844623528   .855628964507
   .526380933305   .871723744056   .531257963080   .894158081023
   .541012022631   .907814926976   .541987428586   .922446016302
   .545889052407   .929762142256   .543670504935   .950000000000

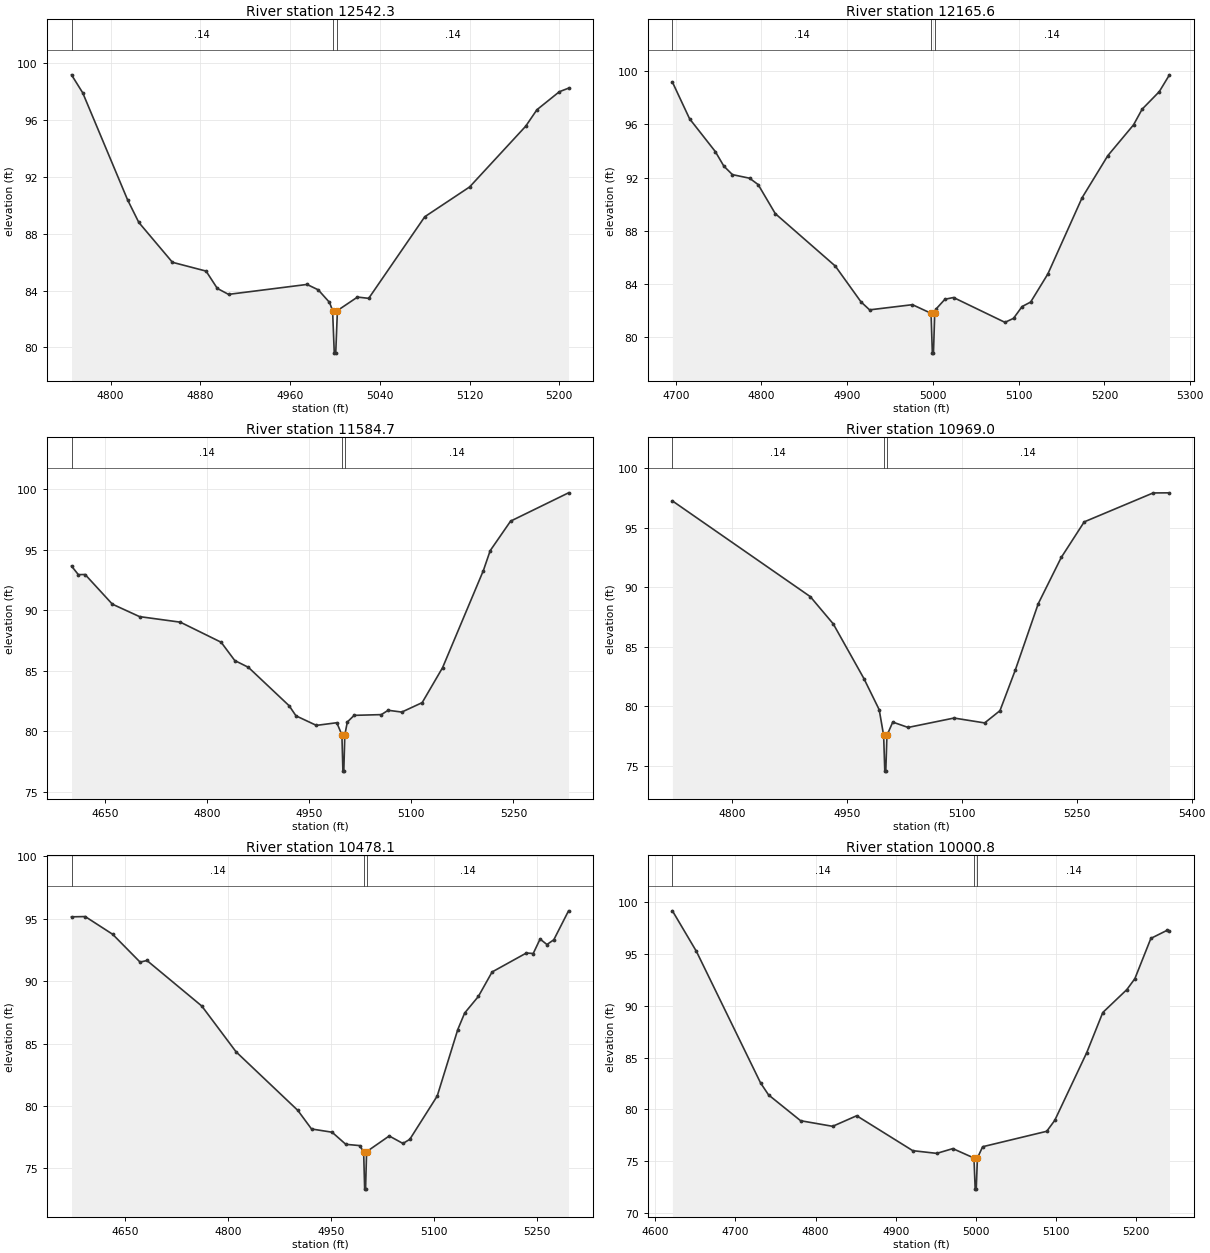
Type RM Length L Ch R = 1 ,12542.3,376.7,376.7,376.7
XS GIS Cut Line= 3
   .051050984461   .051050984461   .078376580451   .051050984461
   .102549223057   .050000000000
BEGIN DESCRIPTION:
Ivy Branch 13.0
END DESCRIPTION:
#Sta/Elev= 23
  4765.1    99.2  4775.1   97.93  4815.1   90.39  4825.1    88.8  4855.1   85.99
  4885.1   85.37  4895.1   84.15  4905.1   83.73  4975.1   84.43  4985.1   84.05
  4995.1   83.17  4997.9   82.59  4999.4   79.59  5000.7   79.59  5002.2   82.59
  5020.1   83.54  5030.1   83.45  5080.1    89.2  5120.1    91.3  5170.1   95.58
  5180.1   96.74  5200.1   98.01  5208.3   98.26
#Mann= 3 , 1 , 0
 4765.10    0.14       0  4997.9   0.047       0  5002.2    0.14       0
Bank Sta=4997.90,5002.20
Exp/Cntr=0.3,0.1

Type RM Length L Ch R = 1 ,12165.6,580.9,580.9,580.9
XS GIS Cut Line= 3
   .050000000000   .096243316290   .085733471679   .094141347368
   .116212021051   .085733471679
BEGIN DESCRIPTION:
Ivy Branch 12.0
END DESCRIPTION:
#Sta/Elev= 30
  4696.1   99.19  4716.1   96.43  4746.1   93.96  4756.1   92.86  4766.1   92.22
  4786.1   91.95  4796.1   91.47  4816.1   89.28  4886.1   85.33  4916.1   82.63
  4926.1   82.03  4976.1   82.42  4997.8   81.77  4999.3   78.77  5000.6   78.77
  5002.1   81.77    5004   82.12    5014   82.83    5024   82.96    5084   81.09
    5094   81.39    5104   82.28    5114   82.62    5134   84.73    5174   90.48
    5204   93.65    5234   95.97    5244   97.15    5264   98.47  5275.9   99.74
#Mann= 3 , 1 , 0
 4696.10    0.14       0  4997.8   0.047       0  5002.1    0.14       0
Bank Sta=4997.80,5002.10
Exp/Cntr=0.3,0.1

Type RM Length L Ch R = 1 ,11584.7,615.7,615.7,615.7
XS GIS Cut Line= 3
   .064713782456   .176118135336   .105723995190   .152875503605
   .137231710275   .131976787969
BEGIN DESCRIPTION:
Ivy Branch 11.0
END DESCRIPTION:
#Sta/Elev= 28
  4600.4   93.66  4610.4   92.95  4620.4   92.96  4660.4   90.51  4700.4   89.48
  4760.4   89.02  4820.4   87.36  4840.4   85.85  4860.4   85.29  4920.4   82.11
  4930.4   81.28  4960.4   80.49  4990.4   80.71  4997.9   79.71  4999.4   76.71
  5000.7   76.71  5002.2   79.71  5005.9   80.77  5015.9   81.32  5055.9   81.38
  5065.9   81.74  5085.9   81.59  5115.9   82.37  5145.9   85.26  5205.9   93.29
  5215.9   94.93  5245.9   97.37  5331.1   99.71
#Mann= 3 , 1 , 0
 4600.40    0.14       0  4997.9   0.047       0  5002.2    0.14       0
Bank Sta=4997.90,5002.20
Exp/Cntr=0.3,0.1

Type RM Length L Ch R = 1 ,10969.0,490.9,490.9,490.9
XS GIS Cut Line= 3
   .116212021051   .237075234081   .139333679196   .212902591475
   .161404352880   .177169119798
BEGIN DESCRIPTION:
Ivy Branch 10.0
END DESCRIPTION:
#Sta/Elev= 20
    4722   97.24    4902    89.2    4932   86.91    4972   82.32    4992    79.7
  4997.8   77.54  4999.3   74.54  5000.6   74.54  5002.1   77.54  5009.7   78.66
  5029.7   78.21  5089.7      79  5129.7   78.59  5149.7   79.62  5169.7   83.03
  5199.7   88.61  5229.7   92.49  5259.7   95.48  5349.7   97.91    5371   97.92
#Mann= 3 , 1 , 0
 4722.00    0.14       0  4997.8   0.047       0  5002.1    0.14       0
Bank Sta=4997.80,5002.10
Exp/Cntr=0.3,0.1

Type RM Length L Ch R = 1 ,10478.1,477.3,477.3,477.3
XS GIS Cut Line= 3
   .162455337341   .293828394983   .182424042104   .247585078693
   .199239793481   .218157513781
BEGIN DESCRIPTION:
Ivy Branch 9.0
END DESCRIPTION:
#Sta/Elev= 30
  4571.9   95.16  4591.9   95.18  4631.9   93.76  4671.9   91.53  4681.9   91.66
  4761.9   88.01  4811.9   84.34  4901.9   79.65  4921.9   78.16  4951.9    77.9
  4971.9   76.93  4991.9   76.83  4997.9   76.34  4999.4   73.34  5000.7   73.34
  5002.2   76.34  5035.2    77.6  5055.2      77  5065.2   77.33  5105.2    80.8
  5135.2   86.13  5145.2   87.45  5165.2   88.78  5185.2   90.74  5235.2   92.26
  5245.2   92.22  5255.2   93.38  5265.2   92.94  5275.2   93.32  5296.7   95.64
#Mann= 3 , 1 , 0
 4571.90    0.14       0  4997.9   0.047       0  5002.2    0.14       0
Bank Sta=4997.90,5002.20
Exp/Cntr=0.3,0.1

Type RM Length L Ch R = 1 ,10000.8,582.3,582.3,582.3
XS GIS Cut Line= 3
   .189780933331   .315899068666   .221310467165   .285420519294
   .240228187466   .264400830071
BEGIN DESCRIPTION:
Ivy Branch 8.5
END DESCRIPTION:
#Sta/Elev= 24
  4621.4   99.16  4651.4   95.24  4731.4   82.56  4741.4    81.4  4781.4   78.91
  4821.4   78.37  4851.4   79.39  4921.4   76.02  4951.4   75.76  4971.4   76.22
  4997.8   75.31  4999.3   72.31  5000.6   72.31  5002.1   75.31  5008.6    76.4
  5088.6   77.89  5098.6   78.94  5138.6   85.49  5158.6   89.35  5188.6   91.56
  5198.6   92.61  5218.6    96.5  5238.6   97.27  5241.8   97.18
#Mann= 3 , 1 , 0
 4621.40    0.14       0  4997.8   0.047       0  5002.1    0.14       0
Bank Sta=4997.80,5002.10
Exp/Cntr=0.3,0.1

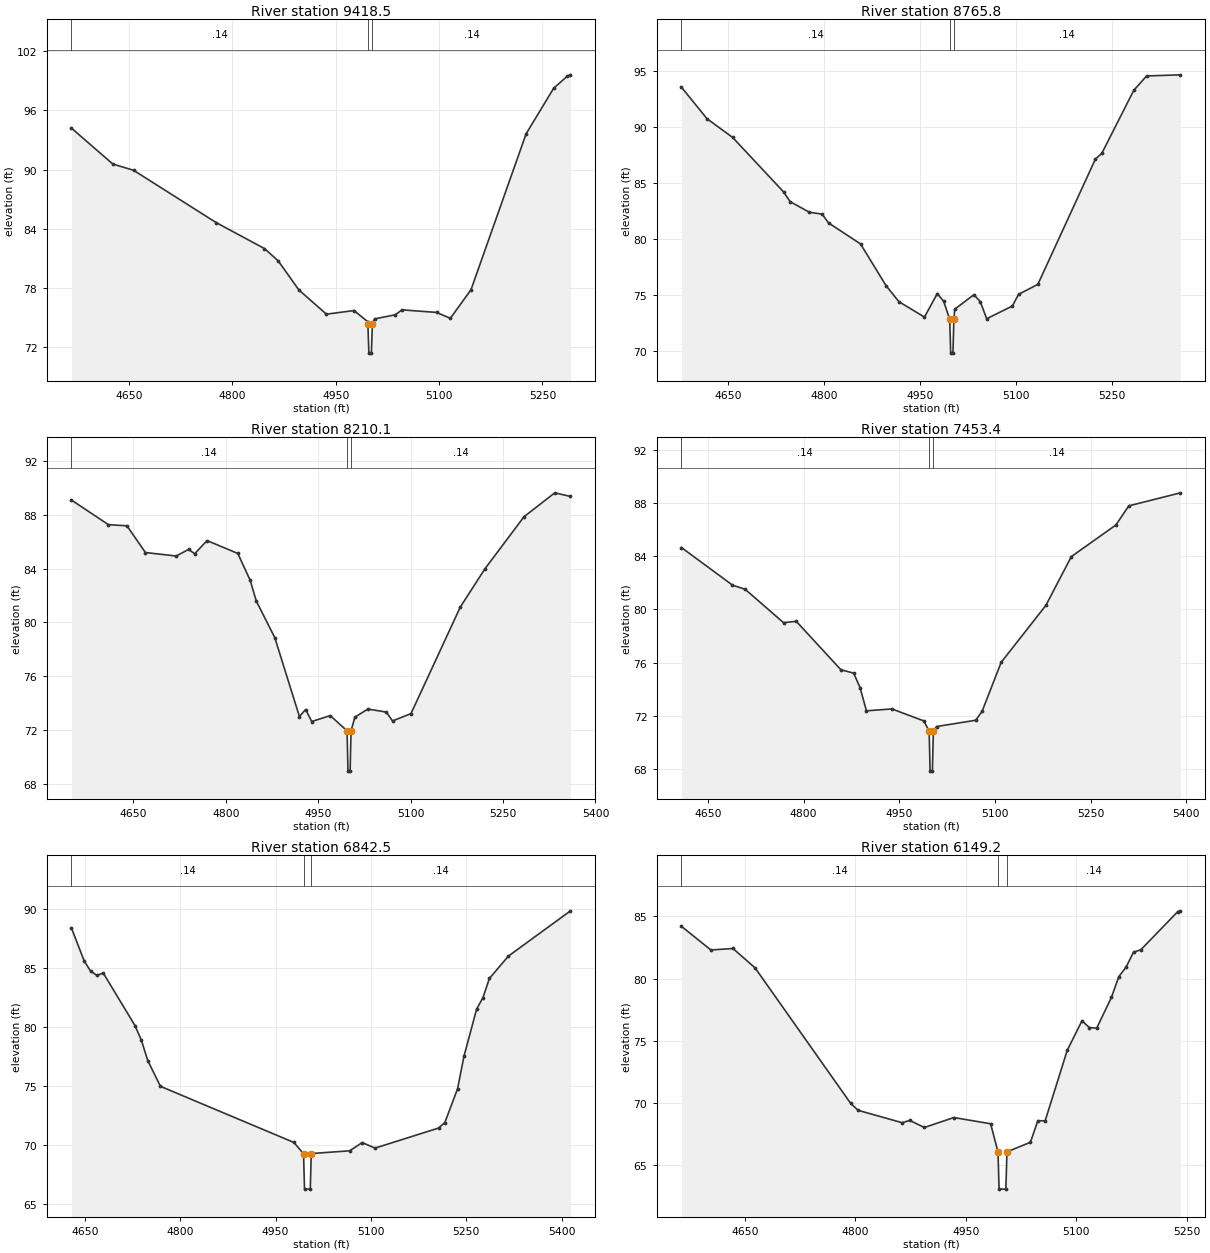
Type RM Length L Ch R = 1 ,9418.5,652.7,652.7,652.7
XS GIS Cut Line= 3
   .201341762404   .357938447113   .249687047616   .345326633579
   .282267565911   .334816788968
BEGIN DESCRIPTION:
Ivy Branch 8.0
END DESCRIPTION:
#Sta/Elev= 24
  4566.6    94.2  4626.6   90.56  4656.6   89.93  4776.6   84.62  4846.6   81.99
  4866.6   80.74  4896.6   77.79  4936.6   75.33  4976.6    75.7  4996.4   74.58
  4996.7   74.38  4998.2   71.38  5001.8   71.38  5003.3   74.38  5006.4   74.85
  5036.4   75.27  5046.4   75.77  5096.4   75.51  5116.4   74.91  5146.4   77.81
  5226.4   93.63  5266.4   98.25  5286.4   99.49  5290.8   99.61
#Mann= 3 , 1 , 0
 4566.60    0.14       0  4996.7   0.047       0  5003.3    0.14       0
Bank Sta=4996.70,5003.30
Exp/Cntr=0.3,0.1

Type RM Length L Ch R = 1 ,8765.8,555.7,555.7,555.7
XS GIS Cut Line= 3
   .230769327315   .418895545858   .280165596989   .413640623553
   .320103006512   .404181763403
BEGIN DESCRIPTION:
Ivy Branch 7.0
END DESCRIPTION:
#Sta/Elev= 30
  4577.2   93.52  4617.2   90.71  4657.2   89.05  4737.2   84.18  4747.2   83.33
  4777.2   82.39  4797.2   82.22  4807.2   81.44  4857.2   79.57  4897.2   75.85
  4917.2   74.43  4957.2   73.06  4977.2   75.15  4987.2   74.47  4996.7   72.85
  4998.2   69.85  5001.7   69.85  5003.2   72.85  5004.5   73.76  5034.5   75.05
  5044.5   74.43  5054.5   72.91  5094.5   74.04  5104.5   75.09  5134.5   75.97
  5224.5   87.12  5234.5   87.63  5284.5   93.24  5304.5   94.52  5357.5   94.62
#Mann= 3 , 1 , 0
 4577.20    0.14       0  4996.7   0.047       0  5003.2    0.14       0
Bank Sta=4996.70,5003.20
Exp/Cntr=0.3,0.1

Type RM Length L Ch R = 1 ,8210.1,756.7,756.7,756.7
XS GIS Cut Line= 4
   .240228187466   .477750675681   .293828394984   .476699691220
   .321153990973   .469342799993   .331663835585   .463036893225
BEGIN DESCRIPTION:
Ivy Branch 6.0
END DESCRIPTION:
#Sta/Elev= 30
  4549.5   89.09  4609.5   87.26  4639.5   87.18  4669.5   85.19  4719.5   84.93
  4739.5   85.42  4749.5    85.1  4769.5   86.08  4819.5   85.12  4839.5   83.13
  4849.5   81.58  4879.5   78.86  4919.5   72.99  4929.5   73.51  4939.5   72.62
  4969.5   73.06  4996.8   71.93  4998.3   68.93  5001.8   68.93  5003.3   71.93
  5009.5   72.94  5030.6   73.55  5060.6   73.32  5070.6   72.66  5100.6   73.21
  5180.6   81.13  5220.6   83.98    5284   87.85    5334   89.63  5359.5   89.36
#Mann= 3 , 1 , 0
 4549.50    0.14       0  4996.8   0.047       0  5003.3    0.14       0
Bank Sta=4996.80,5003.30
Exp/Cntr=0.3,0.1

Type RM Length L Ch R = 1 ,7453.4,610.9,610.9,610.9
XS GIS Cut Line= 3
   .277012643605   .570237308261   .320103006512   .552370572423
   .361091400496   .535554821044
BEGIN DESCRIPTION:
Ivy Branch 5.0
END DESCRIPTION:
#Sta/Elev= 24
  4608.4   84.64  4688.4   81.82  4708.4    81.5  4768.4      79  4788.4    79.1
  4858.4   75.46  4878.4   75.21  4888.4   74.12  4898.4   72.38  4938.4   72.52
  4988.4   71.62  4996.7   70.85  4998.2   67.85  5001.8   67.85  5003.3   70.85
  5008.4    71.2  5069.6   71.67  5079.6   72.33  5109.6   76.02  5179.6   80.29
  5219.6   83.96  5289.6   86.34  5309.6   87.77  5390.7   88.75
#Mann= 3 , 1 , 0
 4608.40    0.14       0  4996.7   0.047       0  5003.3    0.14       0
Bank Sta=4996.70,5003.30
Exp/Cntr=0.3,0.1

Type RM Length L Ch R = 1 ,6842.5,693.3,693.3,693.3
XS GIS Cut Line= 3
   .303287255134   .625939484701   .346377618040   .617531609013
   .393671918791   .614378655629
BEGIN DESCRIPTION:
Ivy Branch 4.0
END DESCRIPTION:
#Sta/Elev= 27
  4628.8   88.39  4648.8   85.61  4658.8   84.75  4668.8   84.38  4678.8   84.58
  4728.8   80.12  4738.8   78.88  4748.8   77.16  4768.8   74.97  4978.8   70.21
    4994   69.25  4995.5   66.25  5004.6   66.25  5006.1   69.25  5006.4   69.27
  5066.4    69.5  5086.4    70.2  5106.4   69.73  5206.4   71.43  5216.4    71.9
  5236.4   74.77  5246.4   77.51  5266.4   81.53  5276.4    82.5  5286.4   84.12
  5316.4   86.02  5414.1   89.86
#Mann= 3 , 1 , 0
 4628.80    0.14       0    4994   0.047       0  5006.1    0.14       0
Bank Sta=4994.00,5006.10
Exp/Cntr=0.3,0.1

Type RM Length L Ch R = 1 ,6149.2,608.5,608.5,608.5
XS GIS Cut Line= 3
   .340240365086   .700190982195   .389219043599   .683864756023
   .412267833489   .669459262342
BEGIN DESCRIPTION:
Ivy Branch 3.0
END DESCRIPTION:
#Sta/Elev= 30
  4563.9    84.2  4603.9    82.3  4633.9   82.42  4663.9   80.86  4793.9   69.95
  4803.9    69.4  4863.9    68.4  4873.9   68.59  4893.9   68.02  4933.9   68.82
  4983.9   68.32  4993.8   66.08  4993.9   66.06  4995.4   63.06  5004.6   63.06
  5006.1   66.06    5038   66.83    5048   68.56    5058   68.56    5088   74.23
    5108    76.6    5118   76.06    5128   76.01    5148   78.48    5158   80.15
    5168   80.93    5178   82.12    5188   82.32    5238   85.38  5241.8   85.45
#Mann= 3 , 1 , 0
 4563.90    0.14       0  4993.8   0.047       0  5006.1    0.14       0
Bank Sta=4993.80,5006.10
Exp/Cntr=0.5,0.3

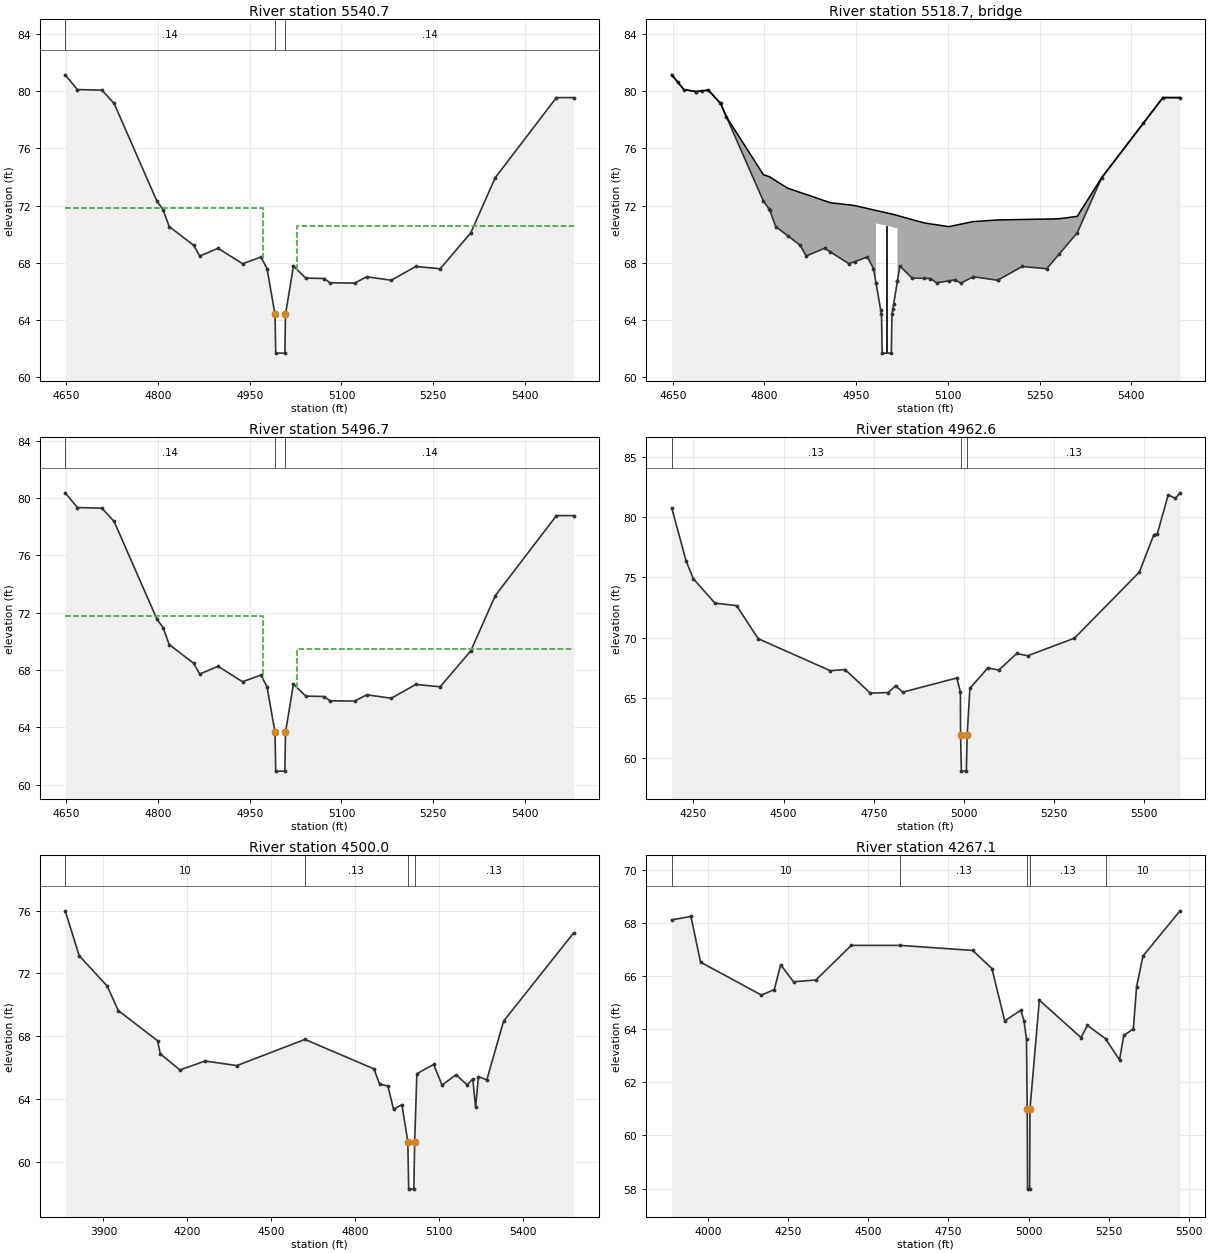
Type RM Length L Ch R = 1 ,5540.7,44,44,44
XS GIS Cut Line= 3
   .389840417057   .739282053303   .429777488307   .739282053303
   .478375611152   .738319714236
BEGIN DESCRIPTION:
Upstream Section of Bridge/Culvert/Weir
END DESCRIPTION:
#Sta/Elev= 30
  4648.3   81.13  4668.3    80.1  4708.3   80.06  4728.3   79.13  4798.3   72.31
  4808.3   71.72  4818.3   70.54  4858.3   69.23  4868.3   68.48  4898.3   69.02
  4938.3   67.94  4968.3   68.41  4978.3    67.6  4991.4    64.4  4992.5    61.7
  5007.5    61.7  5008.5    64.4  5021.5   67.78  5041.5   66.94  5071.5   66.91
  5081.5   66.61  5121.5   66.59  5141.4   67.03  5181.5   66.79  5221.5   67.75
  5261.5   67.59  5311.5    70.1  5351.5   73.95  5451.5   79.54  5479.5   79.54
#Mann= 3 , 1 , 0
 4648.30    0.14       0  4991.4   0.047       0  5008.5    0.14       0
#XS Ineff= 2 , 0
       0    4972    71.8    5028       0    70.6
Bank Sta=4991.40,5008.50
Exp/Cntr=0.5,0.3

Type RM Length L Ch R = 3 ,5518.7,,,
BEGIN DESCRIPTION:
Red Hill Rd-TOR
Structure ID: Red Hill Rd
Approximate Survey Structure
END DESCRIPTION:
Bridge Culvert--1,0,-1,-1, 0
Deck Dist Width WeirC Skew NumUp NumDn MinLoCord MaxHiCord MaxSubmerge Is_Ogee
10,24,2.6,,54,54,,,0.95,0,1,1,,
  4648.3  4657.9  4668.3  4687.9  4688.3  4697.9  4708.3  4727.9  4728.3  4737.9
  4798.3  4807.9  4808.3  4818.3  4837.9  4858.3  4868.3  4898.3  4907.9  4938.3
  4947.9  4968.3  4978.3 4982.41  4982.5    4990  4991.4  4992.5  5007.5  5008.5
    5010  5011.4 5017.39  5017.5  5021.5  5041.5  5061.4  5071.5  5081.5  5101.4
  5111.5  5121.5  5141.4  5141.5  5181.4  5181.5  5221.5  5261.5  5281.4  5311.5
  5351.5  5419.5  5451.5  5479.5
   81.13   80.64    80.1   79.96   79.96   80.01   80.06   79.15   79.13   78.19
   74.16   74.02   74.01   73.74   73.22   72.92   72.78   72.34    72.2   72.05
      72    71.8    71.7   71.66   71.66   71.59   71.58   71.56   71.42   71.41
   71.39   71.38   71.31   71.31   71.26   71.02   70.79   70.72   70.66   70.53
   70.62   70.71   70.88   70.88      71      71   71.03   71.06   71.08   71.25
   73.95   77.75   79.54   79.54
   81.13   80.64    80.1   79.96   79.96   80.01   80.06   79.15   79.13   78.19
   72.31   71.74   71.72   70.54    69.9   69.23   68.48   69.02   68.76   67.94
   68.09   68.41    67.6    66.6   70.76   70.69   70.68   70.66   70.52   70.51
   70.49   70.48   70.41   66.74   67.78   66.94   66.92   66.91   66.61   66.74
   66.81   66.59   67.03   67.03   66.79   66.79   67.75   67.59   68.59    70.1
   73.95   77.75   79.54   79.54
  4648.3  4657.9  4668.3  4687.9  4688.3  4697.9  4708.3  4727.9  4728.3  4737.9
  4798.3  4807.9  4808.3  4818.3  4837.9  4858.3  4868.3  4898.3  4907.9  4938.3
  4947.9  4968.3  4978.3 4982.41  4982.5    4990  4991.4  4992.5  5007.5  5008.5
    5010  5011.4 5017.39  5017.5  5021.5  5041.5  5061.4  5071.5  5081.5  5101.4
  5111.5  5121.5  5141.4  5141.5  5181.4  5181.5  5221.5  5261.5  5281.4  5311.5
  5351.5  5419.5  5451.5  5479.5
   81.03   80.55   80.01   79.87   79.87   79.92   79.97   79.06   79.04    78.1
   74.16   74.02   74.01   73.74   73.22   72.92   72.78   72.34    72.2   72.05
      72    71.8    71.7   71.66   71.66   71.59   71.58   71.56   71.42   71.41
   71.39   71.38   71.31   71.31   71.26   71.02   70.79   70.72   70.66   70.53
   70.62   70.71   70.88   70.88      71      71   71.03   71.06   71.08   71.25
   73.86   77.66   79.44   79.44
   80.93   80.44    79.9   79.76   79.76   79.81   79.86   78.95   78.93   77.99
   72.11   71.54   71.52   70.34    69.7   69.03   68.28   68.82   68.56   67.74
   67.89   68.21    67.4    66.4   70.56   70.49   70.48   70.46   70.32   70.31
   70.29   70.28   70.21   66.54   67.58   66.74   66.72   66.71   66.41   66.54
   66.61   66.39   66.83   66.83   66.59   66.59   67.55   67.39   68.39    69.9
   73.75   77.55   79.34   79.34
Pier Skew, UpSta & Num, DnSta & Num=,5000.0, 2 ,5000.0, 2 , 0 , 0 , 0 ,,
       1       1
    60.7   71.59
       1       1
    60.5   71.39
Abutment Skew #Up #Dn=, 2 , 2
 4982.30 4990.00
   70.76   64.74
 4982.30 4990.00
   70.56   64.54
Abutment Skew #Up #Dn=, 2 , 2
 5010.00 5017.59
   64.79   70.41
 5010.00 5017.59
   64.59   70.21
BR Coef= 1 , 1 , 0 ,1.25, 0 ,,,0.8,0,2,0,
Wspro=,,,, 1 ,,,, 0 ,,,, 0 ,,,,-1 ,-1 ,-1 , 0 , 0 , 0 , 0 , 0
BC Design=,, 0 ,, 0 ,,,,,,
BR U #Sta/Elev= 54
  4648.3   81.13  4657.9   80.64  4668.3    80.1  4687.9   79.96  4688.3   79.96
  4697.9   80.01  4708.3   80.06  4727.9   79.15  4728.3   79.13  4737.9   78.19
  4798.3   72.31  4807.9   71.74  4808.3   71.72  4818.3   70.54  4837.9    69.9
  4858.3   69.23  4868.3   68.48  4898.3   69.02  4907.9   68.76  4938.3   67.94
  4947.9   68.09  4968.3   68.41  4978.3    67.6 4982.41    66.6  4982.5   66.57
    4990   64.74  4991.4    64.4  4992.5    61.7  5007.5    61.7  5008.5    64.4
    5010   64.79  5011.4   65.15 5017.39   66.71  5017.5   66.74  5021.5   67.78
  5041.5   66.94  5061.4   66.92  5071.5   66.91  5081.5   66.61  5101.4   66.74
  5111.5   66.81  5121.5   66.59  5141.4   67.03  5141.5   67.03  5181.4   66.79
  5181.5   66.79  5221.5   67.75  5261.5   67.59  5281.4   68.59  5311.5    70.1
  5351.5   73.95  5419.5   77.75  5451.5   79.54  5479.5   79.54
BR U #Mann= 3
 4648.30    0.14  4991.4   0.047  5008.5    0.14
BR U Banks=4991.40,5008.50
BR D #Sta/Elev= 54
  4648.3   80.93  4657.9   80.44  4668.3    79.9  4687.9   79.76  4688.3   79.76
  4697.9   79.81  4708.3   79.86  4727.9   78.95  4728.3   78.93  4737.9   77.99
  4798.3   72.11  4807.9   71.54  4808.3   71.52  4818.3   70.34  4837.9    69.7
  4858.3   69.03  4868.3   68.28  4898.3   68.82  4907.9   68.56  4938.3   67.74
  4947.9   67.89  4968.3   68.21  4978.3    67.4 4982.41    66.4  4982.5   66.37
    4990   64.54  4991.4    64.2  4992.5    61.5  5007.5    61.5  5008.5    64.2
    5010   64.59  5011.4   64.95 5017.39   66.51  5017.5   66.54  5021.5   67.58
  5041.5   66.74  5061.4   66.72  5071.5   66.71  5081.5   66.41  5101.4   66.54
  5111.5   66.61  5121.5   66.39  5141.4   66.83  5141.5   66.83  5181.4   66.59
  5181.5   66.59  5221.5   67.55  5261.5   67.39  5281.4   68.39  5311.5    69.9
  5351.5   73.75  5419.5   77.55  5451.5   79.34  5479.5   79.34
BR D #Mann= 3
 4648.30    0.14  4991.4   0.047  5008.5    0.14
BR D Banks=4991.40,5008.50

Type RM Length L Ch R = 1 ,5496.7,534.1,534.1,534.1
XS GIS Cut Line= 3
   .390349961479   .744371971003   .430287032728   .744371971003
   .478885155574   .743409631936
BEGIN DESCRIPTION:
Downstream Section of Bridge/Culvert/Weir
END DESCRIPTION:
#Sta/Elev= 30
  4648.3   80.37  4668.3   79.34  4708.3    79.3  4728.3   78.37  4798.3   71.55
  4808.3   70.96  4818.3   69.78  4858.3   68.47  4868.3   67.72  4898.3   68.26
  4938.3   67.18  4968.3   67.65  4978.3   66.84  4991.4   63.64  4992.5   60.94
  5007.5   60.94  5008.5   63.64  5021.5   67.02  5041.5   66.18  5071.5   66.15
  5081.5   65.85  5121.5   65.83  5141.4   66.27  5181.5   66.03  5221.5   66.99
  5261.5   66.83  5311.5   69.34  5351.5   73.19  5451.5   78.78  5479.5   78.78
#Mann= 3 , 1 , 0
 4648.30    0.14       0  4991.4   0.047       0  5008.5    0.14       0
#XS Ineff= 2 , 0
       0    4972    71.8    5028       0    69.5
Bank Sta=4991.40,5008.50
Exp/Cntr=0.5,0.3

Type RM Length L Ch R = 1 ,4962.6,462.6,462.6,462.6
XS GIS Cut Line= 4
   .389464853456   .808316858004   .444345031938   .797645712188
   .480073891963   .781764083403   .535811996076   .741241084304
BEGIN DESCRIPTION:
Ivy Branch 2.0
END DESCRIPTION:
#Sta/Elev= 30
  4189.5   80.79  4229.5   76.37  4249.5   74.89  4309.5   72.87  4369.5   72.66
  4429.5   69.92  4629.5   67.26  4670.4   67.36  4740.4    65.4  4790.4   65.45
  4810.4   66.02  4830.4   65.48  4980.4   66.66  4990.4    65.5 4990.85   61.93
  4993.1   58.93  5006.9   58.93 5009.15   61.93  5016.7    65.8  5066.7    67.5
  5096.7   67.31  5146.7   68.69  5176.7    68.5  5306.7   69.96  5486.7   75.44
  5526.7   78.53  5536.7   78.64  5566.7   81.85  5586.7   81.56  5599.5   82.02
#Mann= 3 , 1 , 0
 4189.50    0.13       0 4990.85   0.046       0 5009.15    0.13       0
Bank Sta=4990.85,5009.15
Exp/Cntr=0.3,0.1

Type RM Length L Ch R = 1 ,4500.0,232.9,232.9,232.9
XS GIS Cut Line= 4
   .364316768561   .866309898203   .443769365730   .852611174554
   .510520783954   .824411570573   .580756602229   .773158577384
BEGIN DESCRIPTION:
Ivy Branch 1.0
END DESCRIPTION:
#Sta/Elev= 30
  3763.2   75.98  3813.2   73.13  3913.2    71.2  3953.2   69.64  4093.2   67.73
  4103.2   66.89  4173.2   65.87  4263.2   66.44  4376.7   66.15  4619.9   67.81
  4866.7   65.94  4886.7   64.97  4916.7   64.85  4936.7   63.37  4966.7   63.67
  4987.8    61.3  4990.8    58.3  5009.2    58.3  5012.2    61.3    5020   65.63
    5080   66.22    5110   64.91    5160   65.57    5200   64.92    5220   65.31
    5230   63.49    5240   65.45    5270   65.24    5330   68.97    5580   74.57
#Mann= 4 , 1 , 0
 3763.20      10       0  4619.9    0.13       0  4987.8   0.046       0
  5012.2    0.13       0
Bank Sta=4987.80,5012.20
Exp/Cntr=0.3,0.1

Type RM Length L Ch R = 1 ,4267.1,317.9,317.9,317.9
XS GIS Cut Line= 5
   .400201074780   .878010591683   .465642726100   .868661784351
   .524406657898   .847293081880   .552453079892   .825924379408
   .563137431128   .808562308650
BEGIN DESCRIPTION:
Ivy Branch 0.8
END DESCRIPTION:
#Sta/Elev= 30
    3887   68.11    3947   68.24    3977   66.52    4167   65.28    4207   65.49
    4227   66.42    4267   65.78    4337   65.85    4447   67.15  4599.9   67.15
  4825.6   66.96  4885.6   66.28  4925.6   64.31  4975.6   64.71  4985.6   64.32
  4993.5   63.61 4995.73   60.98 4996.78   57.98 5003.15   57.98  5004.2   60.98
  5033.5   65.09  5163.5   63.68  5183.5   64.14  5239.9   63.64  5283.5   62.84
  5296.7   63.76  5326.7   64.01  5336.7   65.59  5356.7   66.75  5472.1   68.45
#Mann= 5 , 1 , 0
 3887.00      10       0  4599.9    0.13       0 4995.73   0.046       0
  5004.2    0.13       0  5239.9      10       0
Bank Sta=4995.73,5004.20
Exp/Cntr=0.3,0.1

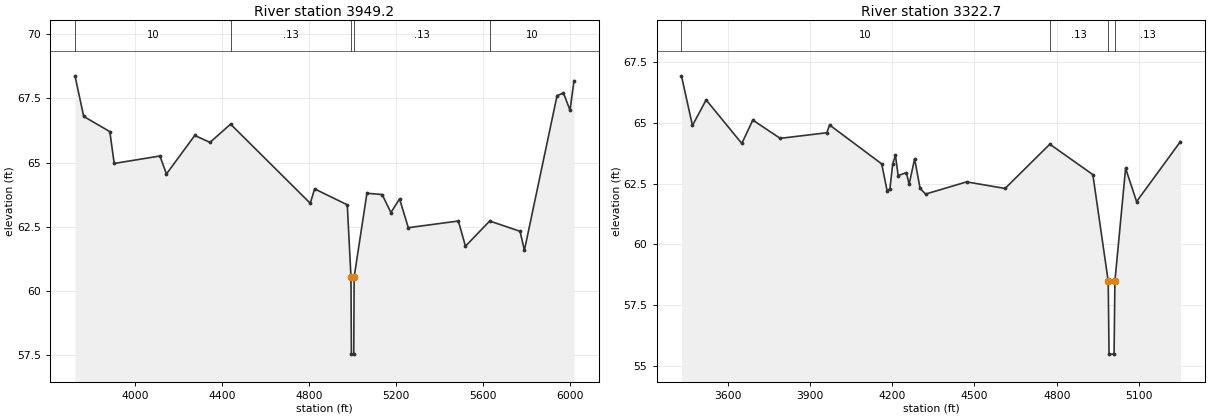
Type RM Length L Ch R = 1 ,3949.2,626.5,626.5,626.5
XS GIS Cut Line= 6
   .382819489521   .902048631494   .466286056302   .894945093896
   .530217894688   .882513903098   .585270311076   .862979174703
   .610756741767   .846571330615   .626052583475   .822671577947
BEGIN DESCRIPTION:
Ivy Branch 0.7
END DESCRIPTION:
#Sta/Elev= 30
  3725.3   68.38  3765.3    66.8  3885.3   66.21  3905.3   64.97  4115.3   65.26
  4145.3   64.56  4275.3   66.06  4345.3   65.79  4439.9    66.5  4805.8   63.42
  4825.8   63.98  4975.8   63.36  4992.8   60.55  4994.6   57.55 5005.52   57.55
 5007.32   60.55    5066   63.81    5136   63.76    5176   63.06    5216   63.59
    5256   62.47    5486   62.73  5518.5   61.75  5629.9   62.73  5769.2   62.33
  5789.2   61.59  5939.2   67.61  5968.7   67.71  5998.7   67.04    6017   68.19
#Mann= 5 , 1 , 0
 3725.30      10       0  4439.9    0.13       0  4992.8   0.046       0
 5007.32    0.13       0  5629.9      10       0
Bank Sta=4992.80,5007.32
Exp/Cntr=0.3,0.1

Type RM Length L Ch R = 1 ,3322.7,0,0,0
XS GIS Cut Line= 4
   .361508876726   .944669857084   .482269015899   .949997510283
   .542649085485   .949997510283   .579942657877   .949997510283
BEGIN DESCRIPTION:
Ivy Branch 0.3
END DESCRIPTION:
#Sta/Elev= 30
  3432.1   66.93  3472.1   64.89  3522.1   65.94  3652.1   64.15  3692.1   65.11
  3792.1   64.36  3962.1   64.59  3972.1   64.91  4162.1   63.31  4182.1   62.19
  4192.1   62.29  4202.1    63.3  4212.1   63.66  4222.1   62.83  4252.1   62.95
  4262.1   62.47  4282.1   63.52  4302.1    62.3  4322.1   62.07  4471.8   62.57
  4611.8    62.3  4774.9   64.12  4931.8   62.87  4987.8   58.49  4990.8   55.49
  5009.2   55.49  5012.2   58.49  5051.2   63.13  5091.2   61.76  5251.2   64.23
#Mann= 4 , 1 , 0
 3432.10      10       0  4774.9    0.13       0  4987.8   0.046       0
  5012.2    0.13       0
Bank Sta=4987.80,5012.20
Exp/Cntr=0.3,0.1

Chan Stop Cuts=-1