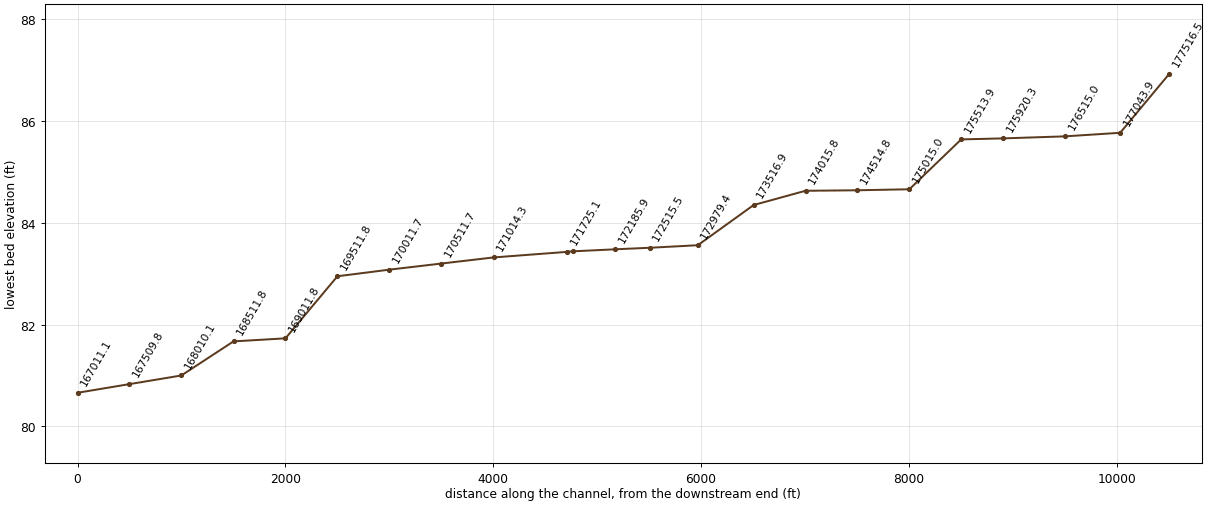
--- Town_Creek_FINAL.prj (project) ---

Proj Title=Town Creek
Current Plan=p02
Default Exp/Contr=0.3,0.1
English Units
Geom File=g01
Flow File=f02
Flow File=f01
Plan File=p01
Plan File=p02
Y Axis Title=Elevation
X Axis Title(PF)=Main Channel Distance
X Axis Title(XS)=Station
BEGIN DESCRIPTION:
NCFPM-Tar Pam Basin
END DESCRIPTION:
DSS Export Rating Curves= 0
DSS Export Rating Curve Sorted= 0
DSS Export Volume Flow Curves= 0
DXF OffsetX= 0
DXF OffsetY= 0
DXF ScaleX= 1
DXF ScaleY= 10

--- Town_Creek_FINAL.p02 (plan) ---

Plan Title=Multi_Profile
Program Version=4.00
Short Identifier=Base Plan
Geom File=g01
Flow File=f02
Subcritical Flow
K Sum by GR= 0
Std Step Tol= 0.01
Critical Tol= 0.01
Num of Std Step Trials= 20
Max Error Tol= 0.3
Flow Tol Ratio= 0.001
Split Flow NTrial= 30
Split Flow Tol= 0.02
Split Flow Ratio= 0.02
Log Output Level= 0
Friction Slope Method= 1
Unsteady Friction Slope Method= 2
Unsteady Bridges Friction Slope Method= 1
Parabolic Critical Depth
Global Vel Dist= 0 , 0 , 0
Global Log Level= 0
CheckData=True
Encroach Param=-1 ,10,10, 2
Computation Interval=1HOUR
Output Interval=1HOUR
Run HTab= 0
Run UNet= 0
Run PostProcess= 0
Run WQNet= 0
UNET Theta= 1
UNET Theta Warmup= 1
UNET ZTol= 0.02
UNET ZSATol= 0.1
UNET MxIter= 20
UNET MaxInSteps= 20
UNET DtIC= 0
UNET DtMin= 0
UNET MaxCRTS= 20
UNET WFStab= 2
UNET SFStab= 1
UNET WFX= 1
UNET SFX= 1
UNET DSS MLevel= 4
UNET DZMax Abort= 100
UNET Convert EG Bridges=-1
UNET Use Existing IB Tables=-1
UNET Froude Reduction=False
UNET Froude Limit= 1
UNET Froude Power= 10
UNET Time Slicing=0,0, 5
Instantaneous Interval=1HOUR
Write IC File= 0
Echo Input=False
Echo Output=False
Write Detailed= 0
Detailed Automatic Start=False, 10
WQ ULTIMATE=-1
WQ Max Comp Step=1HOUR
WQ Output Interval=15MIN
WQ Output Selected Increments= 0
WQ Output face flow=0
WQ Output face velocity=0
WQ Output face area=0
WQ Output face dispersion=0
WQ Output cell volume=0
WQ Output cell surface area=0
WQ Output cell continuity=0
WQ Output face conc=0
WQ Output face dconc_dx=0
WQ Output face courant=0
WQ Output face peclet=0
WQ Output face adv mass=0
WQ Output face disp mass=0
WQ Output cell mass=0
WQ Output cell source sink temp=0
WQ Output cell source sink nsm=0
WQ Output MaxMinRange=-1
WQ Daily Max Min Mean=-1
WQ Daily Range=0
WQ Daily Time=0
WQ Create Restart=0
WQ Fixed Restart=0
WQ System Summary=False
Sorting and Armoring Iterations= 10
XS Update Threshold= 0.02
Hydraulics Update Threshold= 0.02
Energy Slope Method= 1
Volume Change Method= 0
XS Weighting Method= 0
Number of US Weighted Cross Sections= 1
Number of DS Weighted Cross Sections= 1
Upstream XS Weight=0.25
Main XS Weight=0.5
Downstream XS Weight=0.25
Number of DS XS's Weighted with US Boundary= 1
Upstream Boundary Weight= 1
Weight of XSs Associated with US Boundary= 0
Number of US XS's Weighted with DS Boundary= 1
Downstream Boundary Weight= 0.5
Weight of XSs Associated with DS Boundary= 0.5
Sediment Output Level= 4
Mass or Volume Output= 0
Output Increment Type= 1
Profile and TS Output Increment= 10
XS Output Flag= 0
XS Output Increment= 10
Disregard all LS=0
Disregard all Conn=0
Disregard all Breaches=0
Disregard all Pumps=0

--- Town_Creek_FINAL.p01 (plan) ---

Plan Title=Town Creek-Tie-in (10-15)
Version=Version 3.0.1  Mar 2001
Short Identifier=Base Plan
Geom File=g01
Flow File=f01
Subcritical Flow
K Sum by GR= 0
Std Step Tol= 0.01
Critical Tol= 0.01
Num of Std Step Trials= 20
Max Error Tol= 0.3
Flow Tol Ratio= 0.001
Split Flow NTrial= 30
Split Flow Tol= 0.02
Split Flow Ratio= 0.02
Log Output Level= 0
Friction Slope Method= 1
Unsteady Friction Slope Method= 2
Parabolic Critical Depth
Global Vel Dist= 0 , 0 , 0
Global Log Level= 0
CheckData=True
Encroach Param=-1 ,10,10, 2
Encroach River=Main Stem
Encroach Reach=Reach - 1
Encroach Node=177516.5
       4      .7
Encroach Node=177043.9
       4      .7
Encroach Node=176515.0
       4      .7
Encroach Node=175920.3
       4      .7
Encroach Node=175513.9
       4      .7
Encroach Node=175015.0
       4      .7
Encroach Node=174514.8
       4      .7
Encroach Node=174015.8
       4      .7
Encroach Node=173516.9
       4      .7
Encroach Node=172979.4
       4      .7
Encroach Node=172515.5
       4      .7
Encroach Node=172185.9
       4      .7
Encroach Node=171775.1
       4      .7
Encroach Node=171750.1
       4      .7
Encroach Node=171725.1
       4      .7
Encroach Node=171014.3
       4      .7
Encroach Node=170511.7
       4      .7
Encroach Node=170011.7
       4      .7
Encroach Node=169511.8
       4      .7
Encroach Node=169011.8
       4      .7
Encroach Node=168511.8
       4      .7
Encroach Node=168010.1
       4      .7
Encroach Node=167509.8
       4      .7
Encroach Node=167011.1
       4      .7
Encroach Node=166509.9
       4      .7
Encroach Node=166008.7
       4      .7
Encroach Node=165508.2
       4      .7
Encroach Node=165007.3
       4      .7
Encroach Node=164506.3
       4      .7
Encroach Node=164007.1
       4      .7
Encroach Node=163363.8
       4      .7
Encroach Node=163006.4
       4      .7
Encroach Node=162505.6
       4      .7
Encroach Node=162006.4
       4      .7
Encroach Node=161505.0
       4      .7
Encroach Node=161004.7
       4      .7
Encroach Node=160505.3
       4      .7
Encroach Node=160005.9
       4      .7
Encroach Node=159505.9
       4      .7
Encroach Node=159007.6
       4      .7
Encroach Node=158506.7
       4      .7
Encroach Node=158006.9
       4      .7
Encroach Node=157507.8
       4      .7
Encroach Node=157006.3
       4      .7
Encroach Node=156505.1
       4      .7
Encroach Node=156007.0
       4      .7
Encroach Node=155406.8
       4      .7
Encroach Node=154835.3
       4      .7
Encroach Node=154146.9
       4      .7
Encroach Node=153513.1
       4      .7
Encroach Node=152934.6
       4      .7
Encroach Node=152017.5
       4      .7
Encroach Node=151518.0
       4      .7
Encroach Node=150732.1
       4      .7
Encroach Node=150018.2
       4      .7
Encroach Node=149631.2
       4      .7
Encroach Node=149205.8
       4      .7
Encroach Node=149183.3
       4      .7
Encroach Node=149160.8
       4      .7
Encroach Node=148516.6
       4      .7
Encroach Node=148017.3
       4      .7
Encroach Node=147517.5
       4      .7
Encroach Node=147018.1
       4      .7
Encroach Node=146329.4
       4      .7
Encroach Node=145252.7
       4      .7
Encroach Node=144672.0
       4      .7
Encroach Node=143966.2
       4      .7
Encroach Node=143513.6
       4      .7
Encroach Node=143014.3
       4      .7
Encroach Node=142513.8
       4      .7
Encroach Node=142012.9
       4      .7
Encroach Node=141512.5
       4      .7
Encroach Node=140960.8
       4      .7
Encroach Node=140513.9
       4      .7
Encroach Node=140015.1
       4      .7
Encroach Node=139515.7
       4      .7
Encroach Node=139016.7
       4      .7
Encroach Node=138517.3
       4      .7
Encroach Node=138016.7
       4      .7
Encroach Node=137517.3
       4      .7
Encroach Node=137018.1
       4      .7
Encroach Node=136518.3
       4      .7
Encroach Node=135807.2
       4      .7
Encroach Node=135272.9
       4      .7
Encroach Node=134517.0
       4      .7
Encroach Node=134017.0
       4      .7
Encroach Node=133517.0
       4      .7
Encroach Node=133017.9
       4      .7
Encroach Node=132518.7
       4      .7
Encroach Node=132019.1
       4      .7
Encroach Node=131519.6
       4      .7
Encroach Node=131018.8
       4      .7
Encroach Node=130519.3
       4      .7
Encroach Node=129520.2
       4      .7
Encroach Node=128677.0
       4      .7
Encroach Node=127901.0
       4      .7
Encroach Node=126517.9
       4      .7
Encroach Node=126016.6
       4      .5
Encroach Node=125141.7
       4      .5
Encroach Node=123893.8
       4      .5
Encroach Node=123207.7
       4      .5
Encroach Node=122532.5
       4      .5
Encroach Node=121891.9
       4      .5
Encroach Node=121863.4
       4      .5
Encroach Node=121834.9
       4      .5
Encroach Node=121222.0
       4      .5
Encroach Node=120362.4
       4      .7
Encroach Node=120017.8
       4      .7
Encroach Node=119518.0
       4      .7
Encroach Node=119019.0
       4      .7
Encroach Node=118177.5
       4      .7
Encroach Node=117365.4
       4      .7
Encroach Node=116705.3
       4      .7
Encroach Node=115643.1
       4      .7
Encroach Node=114281.2
       4      .7
Encroach Node=113369.3
       4      .7
Encroach Node=113346.8
       4      .7
Encroach Node=113324.3
       4      .7
Encroach Node=112511.3
       4      .7
Encroach Node=111807.1
       4      .7
Encroach Node=111164.6
       4      .7
Encroach Node=110620.4
       4      .7
Encroach Node=110010.4
       4      .7
Encroach Node=109047.1
       4      .7
Encroach Node=108510.3
       4      .7
Encroach Node=107508.0
       4      .7
Encroach Node=106506.0
       4      .7
Encroach Node=105457.9
       4      .7
Encroach Node=104559.4
       4      .7
Encroach Node=103807.0
       4      .7
Encroach Node=102954.3
       4      .7
Encroach Node=102123.6
       4      .7
Encroach Node=100663.8
       4      .7
Encroach Node=99498.7
       4      .7
Encroach Node=98998.0
       4      .7
Encroach Node=97860.4
       4      .7
Encroach Node=96783.2
       4      .7
Encroach Node=95997.8
       1    4500    5676
Encroach Node=95013.2
       1    4580    5190
Computation Interval=1HOUR
Output Interval=1HOUR
Run HTab= 0
Run UNet= 0
Run PostProcess= 0
UNET Theta= 1
UNET ZTol= 0.02
UNET ZSATol= 0.1
UNET MxIter= 20
UNET MaxInSteps= 20
UNET DtIC= 0
UNET DtMin= 0
UNET MaxCRTS= 20
UNET WFStab= 2
UNET SFStab= 1
UNET WFX= 1
UNET SFX= 1
UNET Convert EG Bridges=-1
UNET Use Existing IB Tables=-1
Instantaneous Interval=1HOUR
Write IC File= 0
Write Velocity= 0
Write Detailed= 0

--- Town_Creek_FINAL.f02 (steady flow) ---

Flow Title=Multi-Profile
Program Version=4.00
Number of Profiles= 7
Profile Names=10-yr,25-yr,50-yr,500-yr,100-yr 10%,100-yr 20%,100-yr 35%
River Rch & RM=Main Stem,Reach - 1       ,177516.5
     748    1065    1348    2594    2829    3625    4430
River Rch & RM=Main Stem,Reach - 1       ,175015
    1134    1590    1993    3735    4094    5247    6411
River Rch & RM=Main Stem,Reach - 1       ,170011.7
    1200    1678    2101    3923    4303    5515    6738
River Rch & RM=Main Stem,Reach - 1       ,164506.3
    1279    1785    2231    4149    4555    5837    7132
River Rch & RM=Main Stem,Reach - 1       ,151518
    2191    2999    3704    6650    7353    9424   11514
River Rch & RM=Main Stem,Reach - 1       ,145252.7
    2400    3275    4037    7205    7975   10221   12488
River Rch & RM=Main Stem,Reach - 1       ,135807.2
    2549    3471    4272    7595    8414   10783   13175
Boundary for River Rch & Prof#=Main Stem,Reach - 1       , 1
Up Type= 0
Dn Type= 1
Dn Known WS=59.4
Boundary for River Rch & Prof#=Main Stem,Reach - 1       , 2
Up Type= 0
Dn Type= 1
Dn Known WS=60.1
DSS Import GetInterval= 0
DSS Import GetPeak= 0
DSS Import FillOption= 0

--- Town_Creek_FINAL.f01 (steady flow) ---

Flow Title=Town Creek-Tie-in (10-15)
Version=Version 3.0.1  Mar 2001
Number of Profiles= 2
Profile Names=100-YEAR,AFW
River Rch & RM=Main Stem,Reach - 1       ,177516.5
    1669    1669
River Rch & RM=Main Stem,Reach - 1       ,175015
    2447    2447
River Rch & RM=Main Stem,Reach - 1       ,170011.7
    2576    2576
River Rch & RM=Main Stem,Reach - 1       ,164506.3
    2732    2732
River Rch & RM=Main Stem,Reach - 1       ,151518
    4485    4485
River Rch & RM=Main Stem,Reach - 1       ,145252.7
    4878    4878
River Rch & RM=Main Stem,Reach - 1       ,135807.2
    5156    5156
River Rch & RM=Main Stem,Reach - 1       ,126517.9
    5646    5646
River Rch & RM=Main Stem,Reach - 1       ,108510.3
    6102    6102
Boundary for River Rch & Prof#=Main Stem,Reach - 1       , 1
Up Type= 0
Dn Type= 1
Dn Known WS=59.4
Boundary for River Rch & Prof#=Main Stem,Reach - 1       , 2
Up Type= 0
Dn Type= 1
Dn Known WS=60.1
DSS Import GetInterval= 0
DSS Import GetPeak= 0
DSS Import FillOption= 0

--- Town_Creek_FINAL.g01 (geometry) ---

Geom Title=Geom 01 by CodeH2 for Windows

River Reach=Main Stem,Reach - 1
Reach XY= 2
              .5             .95              .5             .05

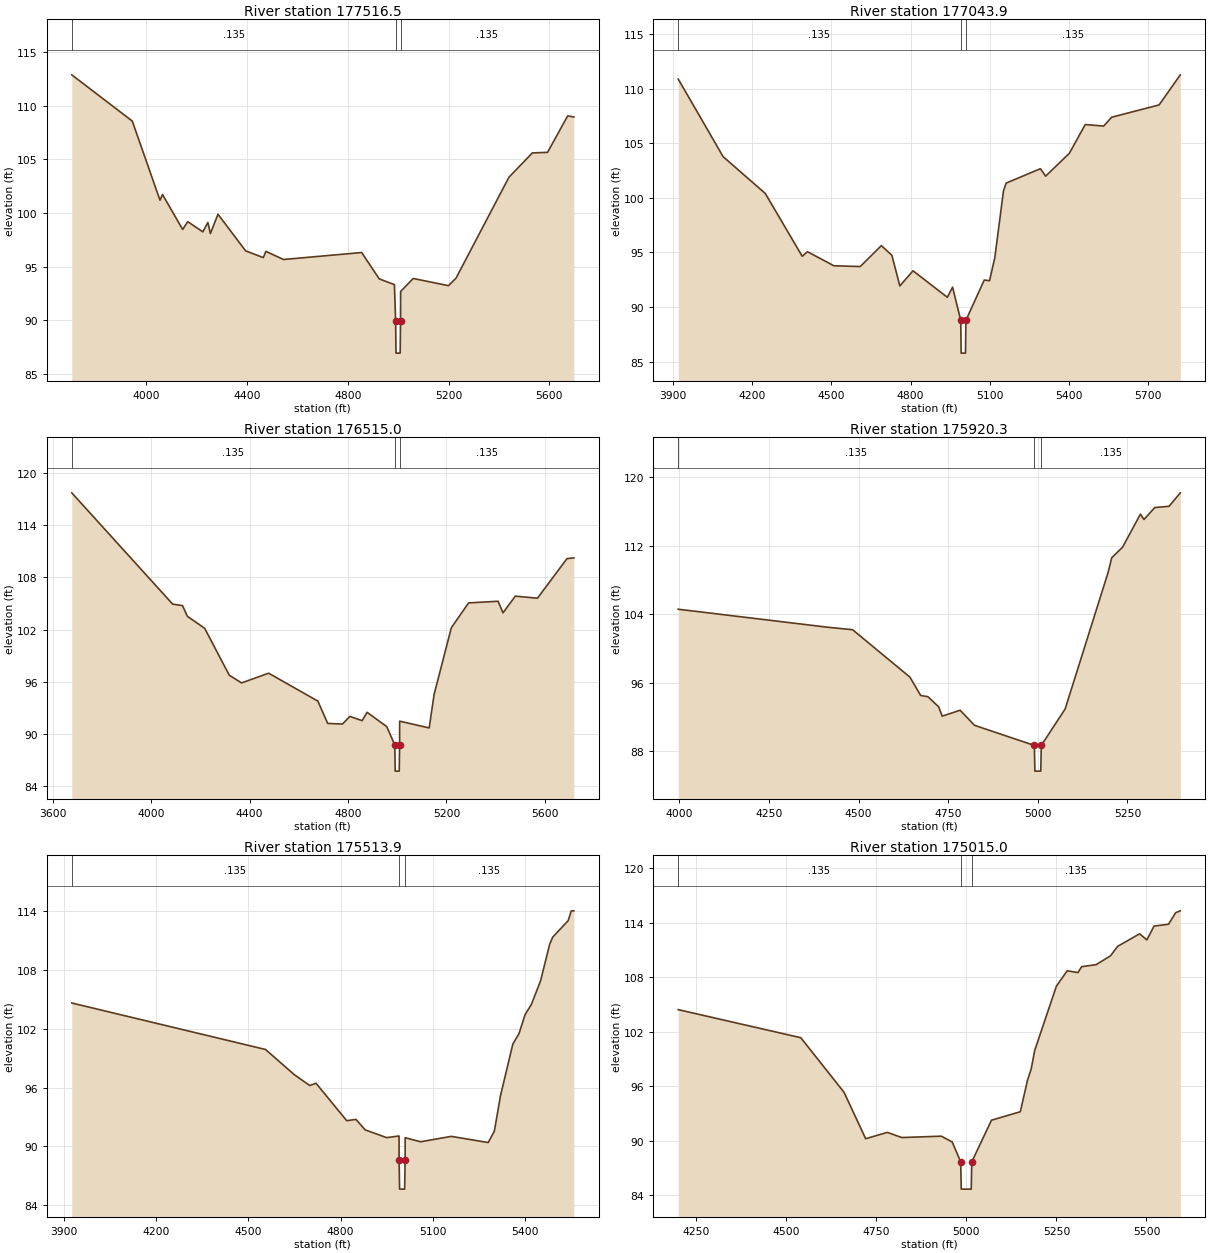
Type RM Length L Ch R = 1 ,177516.5,472.6,472.6,472.6
BEGIN DESCRIPTION:
Town Creek 353.0
END DESCRIPTION:
#Sta/Elev= 30
  3705.4  112.88  3945.4  108.57  4055.4  101.19  4065.4  101.72  4145.4   98.46
  4165.4   99.19  4225.4   98.24  4245.4   99.11  4255.4   98.08  4285.4   99.88
  4395.4   96.46  4465.4   95.84  4475.4   96.42  4545.4   95.66  4855.4   96.31
  4925.4   93.85  4985.4   93.32  4990.2   89.93  4991.7   86.93  5008.2   86.93
  5009.7   89.93    5010   92.68    5060   93.89    5200   93.22    5230   93.93
    5440  103.34  5532.8   105.6  5592.8  105.65  5672.8  109.05  5697.2  108.95
#Mann= 3 , 1 , 0
 3705.40   0.135       0  4990.2    0.05       0  5009.7   0.135       0
Bank Sta=4990.20,5009.70
Exp/Cntr=0.3,0.1

Type RM Length L Ch R = 1 ,177043.9,528.9,528.9,528.9
BEGIN DESCRIPTION:
Town Creek 352.0
END DESCRIPTION:
#Sta/Elev= 30
  3919.3   110.9  4089.3  103.79  4249.3  100.41  4389.3   94.65  4409.3   95.07
  4509.3   93.78  4609.3   93.71  4689.3   95.63  4729.3   94.74  4759.3   91.93
  4809.3   93.32  4939.3   90.89  4959.3   91.82  4990.2   88.77  4991.7   85.77
  5008.2   85.77  5009.7   88.77  5079.3   92.47  5099.3   92.41  5119.3   94.51
  5152.1  100.63  5162.1  101.36  5292.1  102.68  5312.1     102  5402.1   104.1
  5462.1  106.73  5532.1  106.59  5562.1   107.4  5742.1  108.53  5822.5  111.29
#Mann= 3 , 1 , 0
 3919.30   0.135       0  4990.2    0.05       0  5009.7   0.135       0
Bank Sta=4990.20,5009.70
Exp/Cntr=0.3,0.1

Type RM Length L Ch R = 1 ,176515.0,594.7,594.7,594.7
BEGIN DESCRIPTION:
Town Creek 351.0
END DESCRIPTION:
#Sta/Elev= 30
  3677.6  117.73  4087.6  104.92  4127.6  104.75  4147.6  103.51  4217.6  102.14
  4317.6   96.74  4367.6   95.85  4477.6   96.97  4677.6   93.76  4717.6   91.19
  4777.6   91.12  4807.6      92  4857.6   91.51  4877.6   92.47  4957.6   90.82
  4990.3    88.7  4991.8    85.7  5008.3    85.7  5009.8    88.7    5010   91.45
    5130   90.67    5150   94.53    5220   102.2    5290  105.06    5410  105.25
    5430  103.92    5480  105.84    5570   105.6    5690  110.16  5717.8  110.24
#Mann= 3 , 1 , 0
 3677.60   0.135       0  4990.3    0.05       0  5009.8   0.135       0
Bank Sta=4990.30,5009.80
Exp/Cntr=0.3,0.1

Type RM Length L Ch R = 1 ,175920.3,406.4,406.4,406.4
BEGIN DESCRIPTION:
Town Creek 350.0
END DESCRIPTION:
#Sta/Elev= 23
  3996.6  104.56  4413.2  102.46  4483.2  102.17  4643.2   96.63  4673.2   94.49
  4693.2   94.35  4723.2   93.17  4733.2   92.08  4783.2   92.77  4823.2   91.01
  4990.3   88.66  4991.8   85.66  5008.2   85.66  5009.7   88.66  5076.3   92.92
  5196.3  108.88  5206.3  110.58  5236.3  111.79  5286.3  115.66  5296.3  115.04
  5326.3  116.43  5366.3  116.58  5397.6  118.15
#Mann= 3 , 1 , 0
 3996.60   0.135       0  4990.3    0.05       0  5009.7   0.135       0
Bank Sta=4990.30,5009.70
Exp/Cntr=0.3,0.1

Type RM Length L Ch R = 1 ,175513.9,498.9,498.9,498.9
BEGIN DESCRIPTION:
Town Creek 349.0
END DESCRIPTION:
#Sta/Elev= 30
  3925.9  104.62  4555.9   99.88    4650    97.3    4700    96.2    4720   96.44
    4820   92.62    4850   92.75    4880   91.68    4950   90.89    4990   91.06
  4990.3   88.64  4991.8   85.64  5008.3   85.64  5009.8   88.64    5010   90.88
    5060   90.47    5160   91.02    5280   90.39    5300   91.56    5320   95.18
    5360  100.43    5380  101.49    5400  103.45    5420  104.45    5450  106.86
    5480  110.63    5490  111.35    5540  113.02    5550  114.01  5558.4  114.02
#Mann= 3 , 1 , 0
 3925.90   0.135       0  4990.3    0.05       0  5009.8   0.135       0
Bank Sta=4990.30,5009.80
Exp/Cntr=0.3,0.1

Type RM Length L Ch R = 1 ,175015.0,500.2,500.2,500.2
BEGIN DESCRIPTION:
Town Creek 348.0
END DESCRIPTION:
#Sta/Elev= 30
    4201  104.42    4541  101.33    4661   95.32    4721   90.21    4781   90.91
    4821   90.34    4931   90.49    4961   89.85  4984.6   87.66  4986.1   84.66
  5013.8   84.66  5015.3   87.66    5070   92.25    5150   93.18    5170   96.67
    5180   97.87    5190   99.94    5250     107    5280   108.7    5310   108.5
    5320  109.15    5360  109.37    5400  110.34    5420  111.39    5481  112.77
    5501   112.1    5521  113.62    5561  113.82    5581   115.1  5593.8   115.3
#Mann= 3 , 1 , 0
 4201.00   0.135       0  4984.6    0.05       0  5015.3   0.135       0
Bank Sta=4984.60,5015.30
Exp/Cntr=0.3,0.1

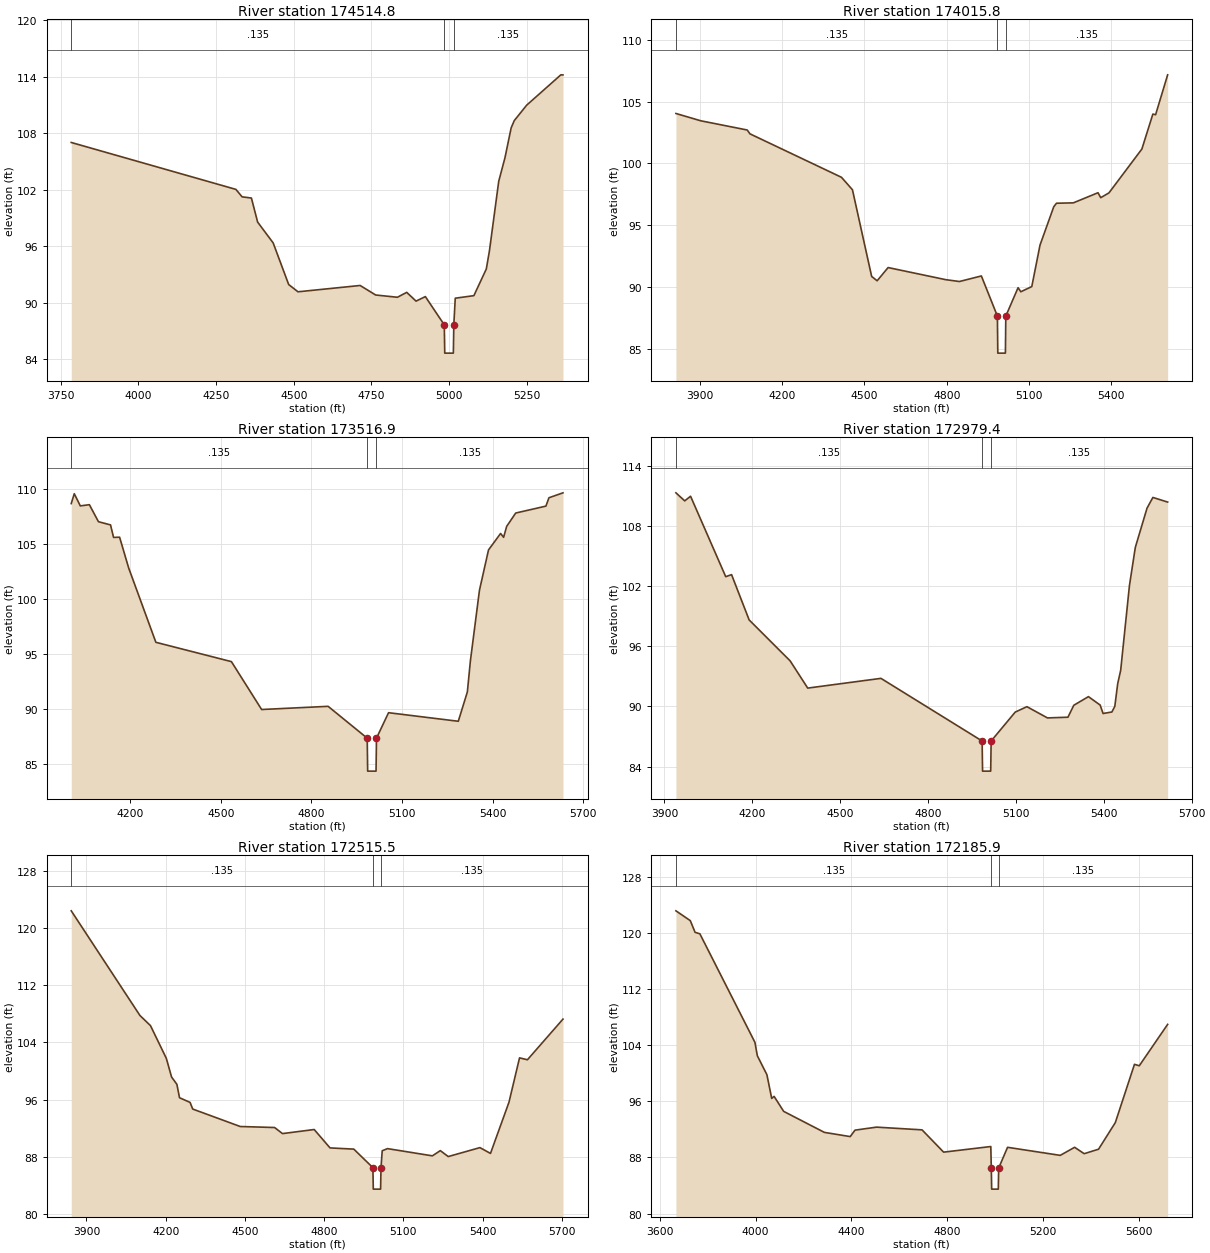
Type RM Length L Ch R = 1 ,174514.8,499,499,499
BEGIN DESCRIPTION:
Town Creek 347.0
END DESCRIPTION:
#Sta/Elev= 29
  3783.8     107  4313.8  102.02  4333.8  101.23  4363.8   101.1  4383.8   98.55
  4433.8   96.34  4483.8   91.92  4513.8   91.15  4713.8   91.82  4763.8   90.81
  4833.8   90.57  4863.8   91.09  4893.8   90.16  4923.8   90.64  4984.7   87.64
  4986.2   84.64  5013.9   84.64  5015.4   87.64    5020   90.47    5080   90.74
    5120   93.57    5130   95.48    5160  102.88    5180  105.37    5200  108.55
    5210  109.32    5250  110.96    5360  114.18  5366.8  114.17
#Mann= 3 , 1 , 0
 3783.80   0.135       0  4984.7    0.05       0  5015.4   0.135       0
Bank Sta=4984.70,5015.40
Exp/Cntr=0.3,0.1

Type RM Length L Ch R = 1 ,174015.8,498.9,498.9,498.9
BEGIN DESCRIPTION:
Town Creek 346.0
END DESCRIPTION:
#Sta/Elev= 30
  3812.6  104.04  3902.6  103.45  4072.6   102.7  4082.6  102.39  4416.2   98.87
  4456.2   97.86  4526.2   90.84  4546.2   90.49  4586.2   91.56  4796.2   90.58
  4846.2   90.43  4926.2   90.88  4984.6   87.63  4986.1   84.63  5013.8   84.63
  5015.3   87.63    5060   89.93    5070    89.6    5110   90.02    5140   93.38
    5190   96.48    5200   96.77  5261.4    96.8  5351.4   97.62  5361.4   97.22
  5391.4   97.61  5511.4  101.16  5551.4  103.99  5561.4  103.94  5605.3  107.17
#Mann= 3 , 1 , 0
 3812.60   0.135       0  4984.6    0.05       0  5015.3   0.135       0
Bank Sta=4984.60,5015.30
Exp/Cntr=0.3,0.1

Type RM Length L Ch R = 1 ,173516.9,537.5,537.5,537.5
BEGIN DESCRIPTION:
Town Creek 345.0
END DESCRIPTION:
#Sta/Elev= 30
  4005.2  108.71  4015.2  109.61  4035.2   108.5  4065.2  108.61  4095.2  107.06
  4135.2  106.77  4145.2  105.63  4165.2  105.65  4195.2  102.85  4285.2   96.08
  4535.2   94.32  4635.2   89.96  4855.2   90.25  4984.6   87.35  4986.1   84.35
  5013.8   84.35  5015.3   87.35  5055.2   89.67    5286   88.89    5316   91.56
    5326   94.38    5356  100.81    5386  104.49    5426  105.99    5436  105.64
    5446  106.63    5476  107.85    5576  108.48    5586  109.24  5632.4  109.69
#Mann= 3 , 1 , 0
 4005.20   0.135       0  4984.6    0.05       0  5015.3   0.135       0
Bank Sta=4984.60,5015.30
Exp/Cntr=0.3,0.1

Type RM Length L Ch R = 1 ,172979.4,463.9,463.9,463.9
BEGIN DESCRIPTION:
Town Creek 344.0
END DESCRIPTION:
#Sta/Elev= 30
  3939.2  111.28  3969.2  110.48  3989.2  110.94  4109.2  102.93  4129.2  103.13
  4189.2   98.62  4329.2   94.54  4389.2   91.83  4639.2    92.8  4984.6   86.56
  4986.1   83.56  5013.9   83.56  5015.4   86.56  5097.6   89.44  5137.6   89.98
  5207.6   88.86  5277.6   88.93  5297.6   90.12  5347.6   90.98  5387.6   90.14
  5397.6    89.3  5427.6   89.45  5437.6   90.01  5447.6   92.29  5457.6   93.59
  5487.6  102.05  5507.6  105.84  5547.6  109.75  5567.6  110.82    5618  110.36
#Mann= 3 , 1 , 0
 3939.20   0.135       0  4984.6    0.05       0  5015.4   0.135       0
Bank Sta=4984.60,5015.40
Exp/Cntr=0.3,0.1

Type RM Length L Ch R = 1 ,172515.5,329.6,329.6,329.6
BEGIN DESCRIPTION:
Town Creek 343.0
END DESCRIPTION:
#Sta/Elev= 30
  3842.4   122.4  4102.4  107.78  4142.4  106.36  4202.4  101.79  4222.4   99.17
  4242.4   98.16  4252.4   96.28  4292.4   95.63  4302.4    94.7  4482.4   92.26
  4612.4   92.12  4642.4   91.27  4762.4   91.84  4822.4   89.27  4912.4    89.1
  4984.7   86.51  4986.2   83.51  5013.9   83.51  5015.4   86.51    5020   88.87
    5040   89.17    5210   88.16    5240   88.89    5270   88.06    5390   89.31
    5430    88.5    5500   95.65    5540  101.85    5570  101.59  5704.5  107.27
#Mann= 3 , 1 , 0
 3842.40   0.135       0  4984.7    0.05       0  5015.4   0.135       0
Bank Sta=4984.70,5015.40
Exp/Cntr=0.3,0.1

Type RM Length L Ch R = 1 ,172185.9,410.8,410.8,410.8
BEGIN DESCRIPTION:
Town Creek 342.0
END DESCRIPTION:
#Sta/Elev= 30
  3667.6  123.21  3727.6  121.81  3747.6  120.14  3767.6  119.93  3997.6  104.43
  4007.6  102.52  4047.6   99.81  4067.6   96.43  4077.6   96.72  4117.6   94.58
  4287.6   91.58  4395.5   90.98  4415.5    91.9  4505.5   92.33  4695.5   91.94
  4785.5   88.76  4982.6   89.56  4984.7   86.48  4986.2   83.48  5013.9   83.48
  5015.4   86.48  5052.6   89.45  5272.6    88.3  5332.6   89.45  5372.6   88.54
  5432.6   89.18  5502.6   92.98  5582.6   101.3  5602.6  101.09  5721.1     107
#Mann= 3 , 1 , 0
 3667.60   0.135       0  4984.7    0.05       0  5015.4   0.135       0
Bank Sta=4984.70,5015.40
Exp/Cntr=0.5,0.3

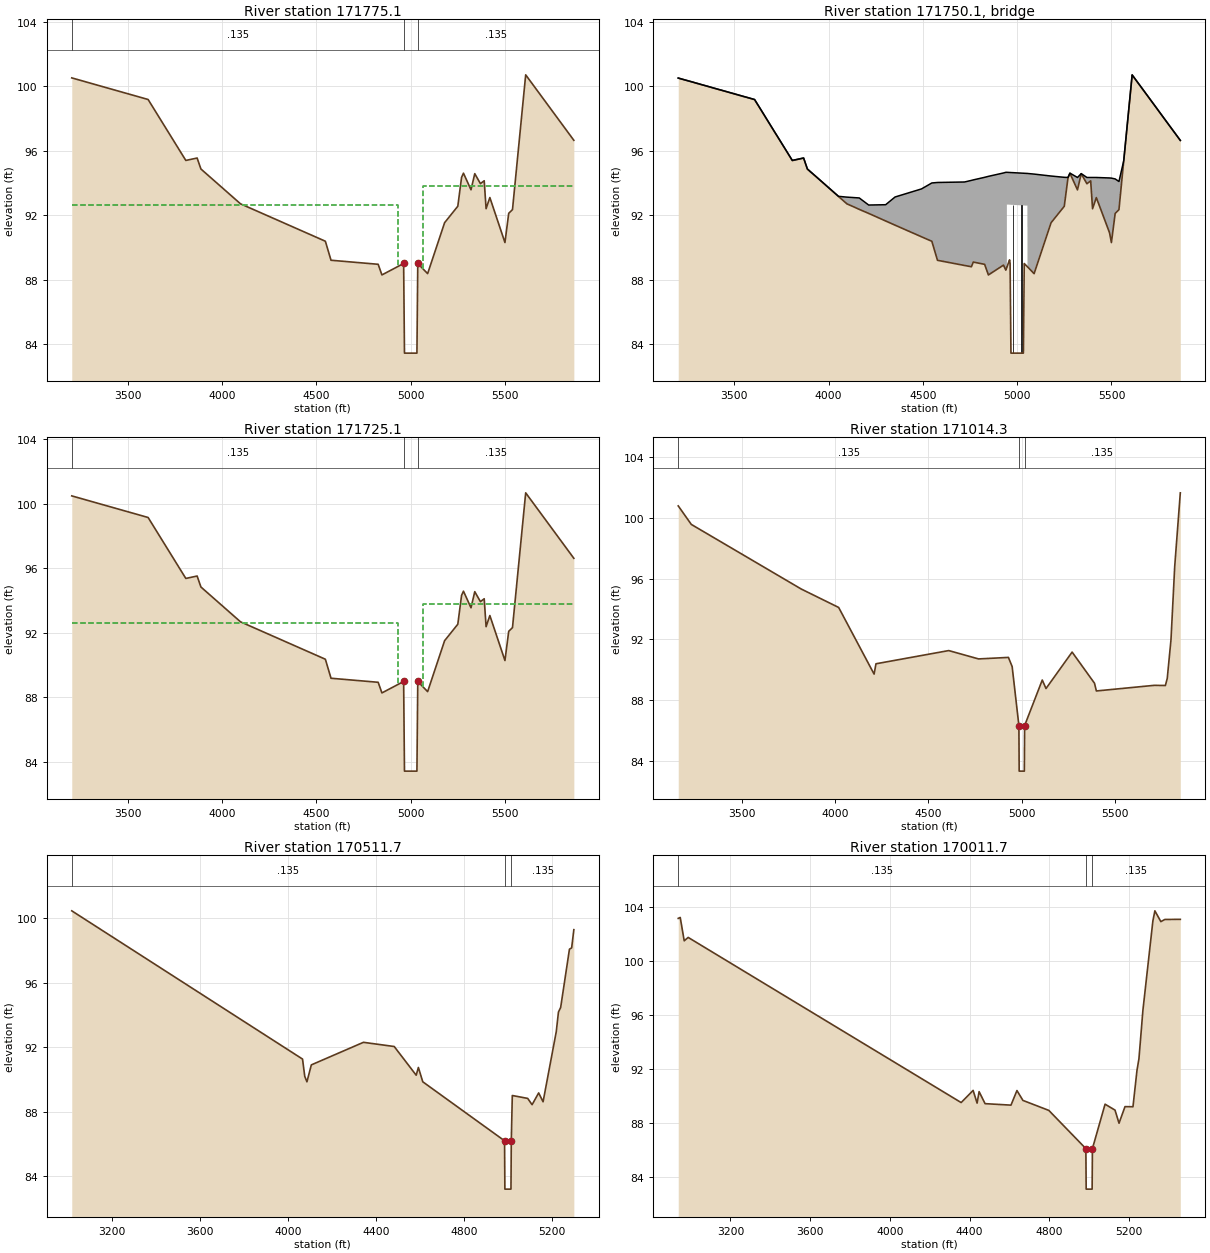
Type RM Length L Ch R = 1 ,171775.1,50,50,50
BEGIN DESCRIPTION:
Upstream Section of Bridge/Culvert/Weir
END DESCRIPTION:
#Sta/Elev= 30
  3202.5  100.51  3607.4   99.17  3807.4   95.39  3867.4   95.54  3887.4   94.86
  4097.4    92.7  4547.4   90.38  4577.4    89.2  4827.4   88.95  4847.4   88.29
  4962.5      89    4967   83.44    5033   83.44  5037.5      89  5089.8   88.37
  5179.8   91.53  5249.8   92.55  5269.8   94.34  5279.8    94.6  5319.8   93.57
  5339.8   94.57  5369.8   93.95  5389.8   94.13  5399.8    92.4  5419.8   93.09
  5499.8    90.3  5519.8   92.11  5539.8   92.34  5609.8   100.7  5865.2   96.64
#Mann= 3 , 1 , 0
 3202.50   0.135       0  4962.5    0.05       0  5037.5   0.135       0
#XS Ineff= 2 , 0
       0    4935    92.6    5065       0    93.8
Bank Sta=4962.50,5037.50
Exp/Cntr=0.5,0.3

Type RM Length L Ch R = 3 ,171750.1,,,
BEGIN DESCRIPTION:
E. Langley Road - TOR
Structure ID: E. Langley Road
Approximate Survey Structure
END DESCRIPTION:
Bridge Culvert--1,0,-1,-1, 0
Deck Dist Width WeirC Skew NumUp NumDn MinLoCord MaxHiCord MaxSubmerge Is_Ogee
10,30,2.6,, 43, 43,,,0.95,0,1,1,,
  3202.5  3607.4  3807.4  3867.4  3887.4  4052.5  4097.4  4162.5  4212.5  4302.5
  4352.5  4492.5  4547.4  4577.4  4720.7  4757.4  4767.4  4827.4  4847.4  4927.4
  4939.8 4945.41  4945.5 5054.39  5054.5  5089.8  5179.8  5249.8  5269.8  5279.8
  5319.8  5339.8  5369.8  5389.8  5399.8  5419.8  5489.8  5499.8  5519.8  5539.8
  5565.2  5609.8  5865.2
  100.51   99.18    95.4   95.55   94.87   93.17   93.12   93.07   92.63   92.65
   93.13   93.63      94   94.03   94.06   94.16   94.19   94.35   94.41   94.62
   94.66   94.66   94.66   94.59   94.59   94.55   94.43   94.35   94.34   94.61
   94.34   94.58   94.34   94.34   94.34   94.34   94.31    94.3   94.25   94.09
   95.38  100.71   96.64
  100.51   99.17   95.39   95.54   94.86   93.16    92.7   92.36   92.11   91.64
   91.38   90.66   90.38    89.2   88.88    88.8   89.09   88.95   88.29    88.9
   88.59   88.77   92.66   92.59    88.8   88.37   91.53   92.55   94.34    94.6
   93.57   94.57   93.95   94.13    92.4   93.09   90.91    90.3   92.11   92.34
   95.37   100.7   96.64
  3202.5  3607.4  3807.4  3867.4  3887.4  4052.5  4097.4  4162.5  4212.5  4302.5
  4352.5  4492.5  4547.4  4577.4  4720.7  4757.4  4767.4  4827.4  4847.4  4927.4
  4939.8 4945.41  4945.5 5054.39  5054.5  5089.8  5179.8  5249.8  5269.8  5279.8
  5319.8  5339.8  5369.8  5389.8  5399.8  5419.8  5489.8  5499.8  5519.8  5539.8
  5565.2  5609.8  5865.2
  100.51   99.18    95.4   95.55   94.87   93.17   93.12   93.07   92.63   92.65
   93.13   93.63      94   94.03   94.06   94.16   94.19   94.35   94.41   94.62
   94.66   94.66   94.66   94.59   94.59   94.55   94.43   94.35   94.34   94.61
   94.34   94.58   94.34   94.34   94.34   94.34   94.31    94.3   94.25   94.09
   95.38  100.71   96.64
  100.51   99.17   95.39   95.54   94.86   93.16    92.7   92.36   92.11   91.64
   91.38   90.66   90.38    89.2   88.88    88.8   89.09   88.95   88.29    88.9
   88.59   88.77   92.66   92.59    88.8   88.37   91.53   92.55   94.34    94.6
   93.57   94.57   93.95   94.13    92.4   93.09   90.91    90.3   92.11   92.34
   95.37   100.7   96.64
Pier Skew, UpSta & Num, DnSta & Num=,4977.5, 2 ,4977.5, 2 , 0 , 0 , 0 ,,
       1       1
   82.44   93.65
       1       1
   82.44   93.65
Pier Skew, UpSta & Num, DnSta & Num=,5022.5, 2 ,5022.5, 2 , 0 , 0 , 0 ,,
       1       1
   82.44   93.63
       1       1
   82.44   93.63
Abutment Skew #Up #Dn=, 2 , 2
 4945.30 4955.00
   92.66   89.08
 4945.30 4955.00
   92.66   89.08
Abutment Skew #Up #Dn=, 2 , 2
 5045.00 5054.59
   88.91   92.59
 5045.00 5054.59
   88.91   92.59
BR Coef= 1 , 1 , 0 ,1.25, 0 ,,,0.8,0,2,0,
Wspro=,,,, 1 ,,,, 0 ,,,, 0 ,,,,-1 ,-1 ,-1 , 0 , 0 , 0 , 0 , 0
BC Design=,, 0 ,, 0 ,,,,,,
BR U #Sta/Elev= 85
  3202.5  100.51  3222.5  100.44  3282.5  100.25  3292.5  100.21  3312.5  100.15
  3322.5  100.11  3332.5  100.08  3372.5   99.95  3382.5   99.91  3422.5   99.78
  3432.5   99.75  3462.5   99.65  3552.5   99.35  3572.5   99.29  3592.5   99.22
  3607.4   99.17  3642.5   98.51  3712.5   97.18  3742.5   96.62  3807.4   95.39
  3812.5    95.4  3862.5   95.53  3867.4   95.54  3872.5   95.37  3887.4   94.86
  3902.5    94.7  3932.5    94.4  3992.5   93.78  4052.5   93.16  4097.4    92.7
  4132.5   92.52  4162.5   92.36  4212.5   92.11  4302.5   91.64  4352.5   91.38
  4492.5   90.66  4547.4   90.38  4550.7   90.25  4577.4    89.2  4720.7   88.88
  4757.4    88.8  4767.4   89.09  4827.4   88.95  4847.4   88.29  4927.4    88.9
  4939.8   88.59  4940.7   88.62 4945.41   88.77  4945.5   88.77    4955   89.08
  4959.8   89.23  4962.5      89    4967   83.44  5015.2   83.44    5033   83.44
  5037.5      89    5045   88.91 5054.39    88.8  5054.5    88.8  5089.8   88.37
  5179.8   91.53  5249.8   92.55  5255.2   93.03  5269.8   94.34  5279.8    94.6
  5319.8   93.57  5339.8   94.57  5369.8   93.95  5389.8   94.13  5399.8    92.4
  5419.8   93.09  5455.2   91.99  5489.8   90.91  5499.8    90.3  5515.2   91.69
  5519.8   92.11  5539.8   92.34  5565.2   95.37  5609.8   100.7  5615.2  100.61
  5655.2   99.98  5725.2   98.87  5795.2   97.75  5845.2   96.96  5865.2   96.64
BR U #Mann= 3
 3202.50   0.135  4962.5    0.05  5037.5   0.135
BR U Banks=4962.50,5037.50
BR D #Sta/Elev= 85
  3202.5  100.51  3222.5  100.44  3282.5  100.25  3292.5  100.21  3312.5  100.15
  3322.5  100.11  3332.5  100.08  3372.5   99.95  3382.5   99.91  3422.5   99.78
  3432.5   99.75  3462.5   99.65  3552.5   99.35  3572.5   99.29  3592.5   99.22
  3607.4   99.17  3642.5   98.51  3712.5   97.18  3742.5   96.62  3807.4   95.39
  3812.5    95.4  3862.5   95.53  3867.4   95.54  3872.5   95.37  3887.4   94.86
  3902.5    94.7  3932.5    94.4  3992.5   93.78  4052.5   93.16  4097.4    92.7
  4132.5   92.52  4162.5   92.36  4212.5   92.11  4302.5   91.64  4352.5   91.38
  4492.5   90.66  4547.4   90.38  4550.7   90.25  4577.4    89.2  4720.7   88.88
  4757.4    88.8  4767.4   89.09  4827.4   88.95  4847.4   88.29  4927.4    88.9
  4939.8   88.59  4940.7   88.62 4945.41   88.77  4945.5   88.77    4955   89.08
  4959.8   89.23  4962.5      89    4967   83.44  5015.2   83.44    5033   83.44
  5037.5      89    5045   88.91 5054.39    88.8  5054.5    88.8  5089.8   88.37
  5179.8   91.53  5249.8   92.55  5255.2   93.03  5269.8   94.34  5279.8    94.6
  5319.8   93.57  5339.8   94.57  5369.8   93.95  5389.8   94.13  5399.8    92.4
  5419.8   93.09  5455.2   91.99  5489.8   90.91  5499.8    90.3  5515.2   91.69
  5519.8   92.11  5539.8   92.34  5565.2   95.37  5609.8   100.7  5615.2  100.61
  5655.2   99.98  5725.2   98.87  5795.2   97.75  5845.2   96.96  5865.2   96.64
BR D #Mann= 3
 3202.50   0.135  4962.5    0.05  5037.5   0.135
BR D Banks=4962.50,5037.50

Type RM Length L Ch R = 1 ,171725.1,710.8,710.8,710.8
BEGIN DESCRIPTION:
Downstream Section of Bridge/Culvert/Weir
END DESCRIPTION:
#Sta/Elev= 30
  3202.5   100.5  3607.4   99.16  3807.4   95.38  3867.4   95.53  3887.4   94.85
  4097.4   92.69  4547.4   90.37  4577.4   89.19  4827.4   88.94  4847.4   88.28
  4962.5   88.99    4967   83.43    5033   83.43  5037.5   88.99  5089.8   88.36
  5179.8   91.52  5249.8   92.54  5269.8   94.33  5279.8   94.59  5319.8   93.56
  5339.8   94.56  5369.8   93.94  5389.8   94.12  5399.8   92.39  5419.8   93.08
  5499.8   90.29  5519.8    92.1  5539.8   92.33  5609.8  100.69  5865.2   96.63
#Mann= 3 , 1 , 0
 3202.50   0.135       0  4962.5    0.05       0  5037.5   0.135       0
#XS Ineff= 2 , 0
       0    4935    92.6    5065       0    93.8
Bank Sta=4962.50,5037.50
Exp/Cntr=0.5,0.3

Type RM Length L Ch R = 1 ,171014.3,502.6,502.6,502.6
BEGIN DESCRIPTION:
Town Creek 340.0
END DESCRIPTION:
#Sta/Elev= 25
  3158.5  100.79  3228.5   99.57  3818.5   95.31  4018.5    94.1  4208.5   89.71
  4218.5   90.39  4608.5   91.26  4768.5   90.71  4928.5   90.81  4948.5   90.21
  4984.7   86.32  4986.2   83.32  5013.9   83.32  5015.4   86.32    5110   89.32
    5130   88.76    5270   91.16    5390   89.11    5400    88.6    5710   88.97
    5770   88.96    5780   89.43    5800   91.97    5820    96.8    5850  101.65
#Mann= 3 , 1 , 0
 3158.50   0.135       0  4984.7    0.05       0  5015.4   0.135       0
Bank Sta=4984.70,5015.40
Exp/Cntr=0.3,0.1

Type RM Length L Ch R = 1 ,170511.7,500,500,500
BEGIN DESCRIPTION:
Town Creek 339.0
END DESCRIPTION:
#Sta/Elev= 25
  3015.6  100.47  4065.6   91.27  4075.6    90.2  4085.6   89.86  4105.6   90.91
  4342.7   92.31  4482.7   92.05  4582.7   90.27  4592.7   90.75  4612.7   89.86
  4984.7    86.2  4986.2    83.2  5013.9    83.2  5015.4    86.2    5020   89.01
    5090   88.83    5110   88.44    5140   89.17    5160   88.62    5220   92.97
    5230   94.19    5240   94.47    5280   98.09    5290   98.17    5300    99.3
#Mann= 3 , 1 , 0
 3015.60   0.135       0  4984.7    0.05       0  5015.4   0.135       0
Bank Sta=4984.70,5015.40
Exp/Cntr=0.3,0.1

Type RM Length L Ch R = 1 ,170011.7,499.9,499.9,499.9
BEGIN DESCRIPTION:
Town Creek 338.0
END DESCRIPTION:
#Sta/Elev= 30
  2937.7  103.13  2947.7   103.2  2967.7  101.47  2987.7  101.72  4357.7   89.49
  4417.7   90.39  4437.7   89.45  4447.7    90.3  4477.7   89.41  4607.7    89.3
  4637.7   90.38  4667.7   89.65  4797.7   88.91  4983.6   86.08  4985.1   83.08
    5015   83.08  5016.5   86.08    5080   89.37    5130   88.93    5150   87.96
    5180   89.19    5220   89.18    5240   91.86    5250   92.74    5270   96.34
    5320  102.95    5330  103.69    5360  102.89    5380  103.05  5457.6  103.06
#Mann= 3 , 1 , 0
 2937.70   0.135       0  4983.6    0.05       0  5016.5   0.135       0
Bank Sta=4983.60,5016.50
Exp/Cntr=0.3,0.1

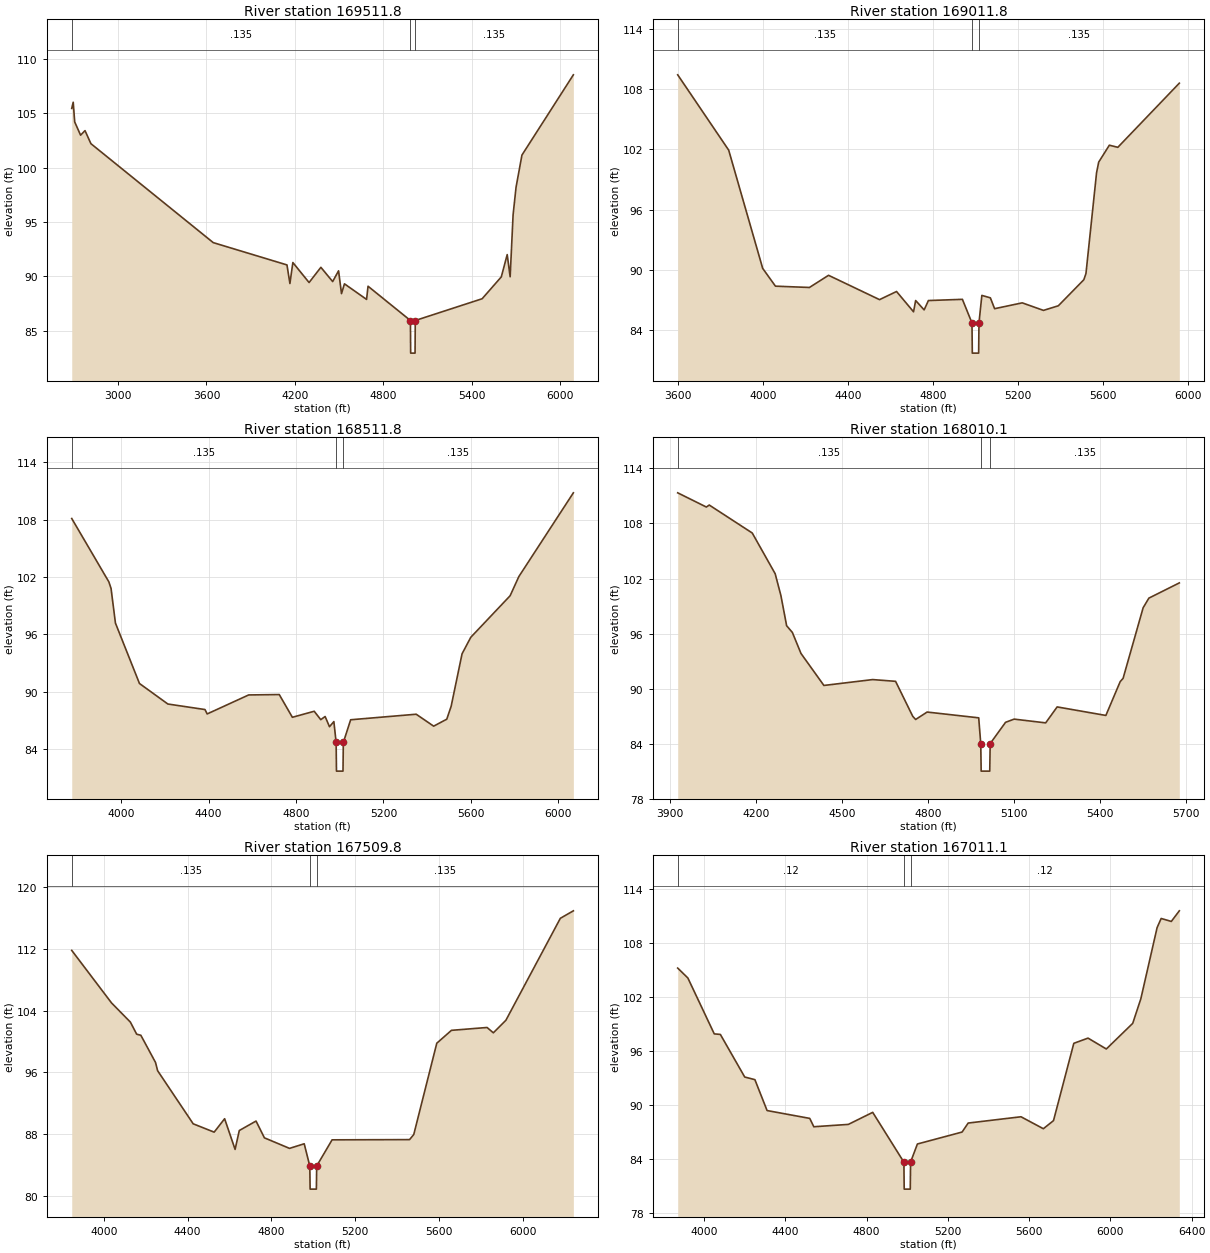
Type RM Length L Ch R = 1 ,169511.8,500,500,500
BEGIN DESCRIPTION:
Town Creek 337.0
END DESCRIPTION:
#Sta/Elev= 30
    2686  105.45    2696  106.02    2706  104.21    2746  102.99    2776  103.41
    2816  102.21    3646   93.11    4146   91.06    4166   89.35    4186   91.28
    4296   89.44    4376   90.84    4456   89.53    4496   90.52    4516   88.42
    4536   89.32    4686   87.89    4696    89.1  4983.5   85.95    4985   82.95
  5014.9   82.95  5016.4   85.95    5470   87.95    5600   89.96    5640   92.01
    5660   89.97    5680   95.67    5700    98.2    5740  101.16  6088.8  108.54
#Mann= 3 , 1 , 0
 2686.00   0.135       0  4983.5    0.05       0  5016.4   0.135       0
Bank Sta=4983.50,5016.40
Exp/Cntr=0.3,0.1

Type RM Length L Ch R = 1 ,169011.8,500,500,500
BEGIN DESCRIPTION:
Town Creek 336.0
END DESCRIPTION:
#Sta/Elev= 30
  3598.4  109.41  3838.4  101.92  3998.4   90.16  4058.4   88.39  4218.4   88.26
  4308.4   89.47  4548.4   87.05  4628.4   87.86  4708.4   85.84  4718.4   86.96
  4758.4   86.03  4778.4   86.96  4938.4   87.08  4983.5   84.73    4985   81.73
  5014.9   81.73  5016.4   84.73    5030   87.47    5070   87.23    5090   86.15
    5220   86.73    5320   85.98    5390   86.44    5510   89.03    5520   89.65
    5570   99.69    5580  100.73    5630  102.41    5670   102.2  5959.4  108.58
#Mann= 3 , 1 , 0
 3598.40   0.135       0  4983.5    0.05       0  5016.4   0.135       0
Bank Sta=4983.50,5016.40
Exp/Cntr=0.3,0.1

Type RM Length L Ch R = 1 ,168511.8,501.7,501.7,501.7
BEGIN DESCRIPTION:
Town Creek 335.0
END DESCRIPTION:
#Sta/Elev= 30
  3773.1  108.13  3943.1  101.49  3953.1   100.8  3973.1   97.18  4083.1   90.85
  4213.1    88.7  4383.1   88.12  4393.1   87.66  4583.1   89.65  4723.1   89.69
  4783.1   87.31  4883.1   87.94  4913.1   87.06  4933.1   87.39  4953.1   86.32
  4973.1   86.86  4983.5   84.67    4985   81.67  5014.9   81.67  5016.4   84.67
    5050   87.05    5350   87.63    5430   86.38    5490   87.11    5510   88.46
    5560   93.96    5600   95.69    5780  100.04    5820  102.05  6069.5  110.82
#Mann= 3 , 1 , 0
 3773.10   0.135       0  4983.5    0.05       0  5016.4   0.135       0
Bank Sta=4983.50,5016.40
Exp/Cntr=0.3,0.1

Type RM Length L Ch R = 1 ,168010.1,500.3,500.3,500.3
BEGIN DESCRIPTION:
Town Creek 334.0
END DESCRIPTION:
#Sta/Elev= 30
  3926.4  111.34  4026.4  109.79  4036.4  110.01  4186.4  106.96  4266.4  102.52
  4286.4  100.14  4306.4   96.85  4326.4   96.12  4356.4   93.83  4436.4   90.34
  4606.4   90.98  4686.4   90.79  4746.4   86.97  4756.4   86.63  4796.4   87.44
  4976.4   86.81  4983.5      84    4985      81  5014.9      81  5016.4      84
    5070   86.32    5100   86.67    5210   86.26    5250      88    5420   87.07
    5470   90.76    5480   91.11    5550   98.81    5570   99.86  5676.2  101.52
#Mann= 3 , 1 , 0
 3926.40   0.135       0  4983.5    0.05       0  5016.4   0.135       0
Bank Sta=4983.50,5016.40
Exp/Cntr=0.3,0.1

Type RM Length L Ch R = 1 ,167509.8,498.7,498.7,498.7
BEGIN DESCRIPTION:
Town Creek 333.0
END DESCRIPTION:
#Sta/Elev= 30
  3846.9  111.83  4036.9  105.01  4126.9  102.52  4156.9  100.95  4176.9  100.81
  4246.9   97.28  4256.9   96.21  4426.9   89.31  4526.9   88.23  4576.9   89.97
  4626.9   85.99  4646.9   88.44  4726.9   89.67  4766.9   87.49  4886.9   86.12
  4956.9   86.72  4983.6   83.83  4985.1   80.83    5015   80.83  5016.5   83.83
    5090   87.23    5460   87.26    5480   87.92    5590   99.78    5660  101.45
    5830  101.82    5860  101.13    5920  102.76    6180     116  6242.1  116.97
#Mann= 3 , 1 , 0
 3846.90   0.135       0  4983.6    0.05       0  5016.5   0.135       0
Bank Sta=4983.60,5016.50
Exp/Cntr=0.3,0.1

Type RM Length L Ch R = 1 ,167011.1,501.2,501.2,501.2
BEGIN DESCRIPTION:
Town Creek 332.0
END DESCRIPTION:
#Sta/Elev= 30
    3870  105.25    3920  104.15    4050   97.93    4080   97.87    4200   93.13
    4250   92.84    4310    89.4    4520   88.53    4540    87.6    4710   87.86
    4830    89.2  4983.5   83.66    4985   80.66  5014.9   80.66  5016.4   83.66
    5050   85.68    5270   87.01    5300   88.01    5560   88.71    5670   87.38
    5720   88.28    5820   96.88    5890   97.46    5980   96.25    6110    99.1
    6150  101.84    6230  109.75    6250  110.77    6300  110.44  6339.4  111.62
#Mann= 3 , 1 , 0
 3870.00    0.12       0  4983.5    0.05       0  5016.4    0.12       0
Bank Sta=4983.50,5016.40
Exp/Cntr=0.3,0.1