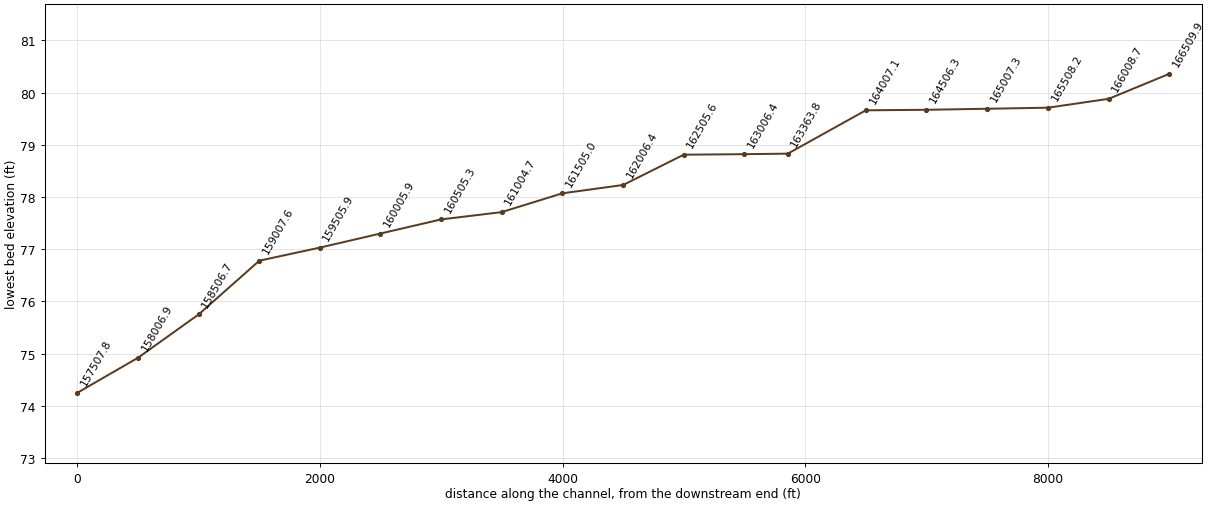
HEC-RAS study Town_Creek_FINAL.prj: Town Creek

--- Town_Creek_FINAL.g01 (geometry) --- (continued)

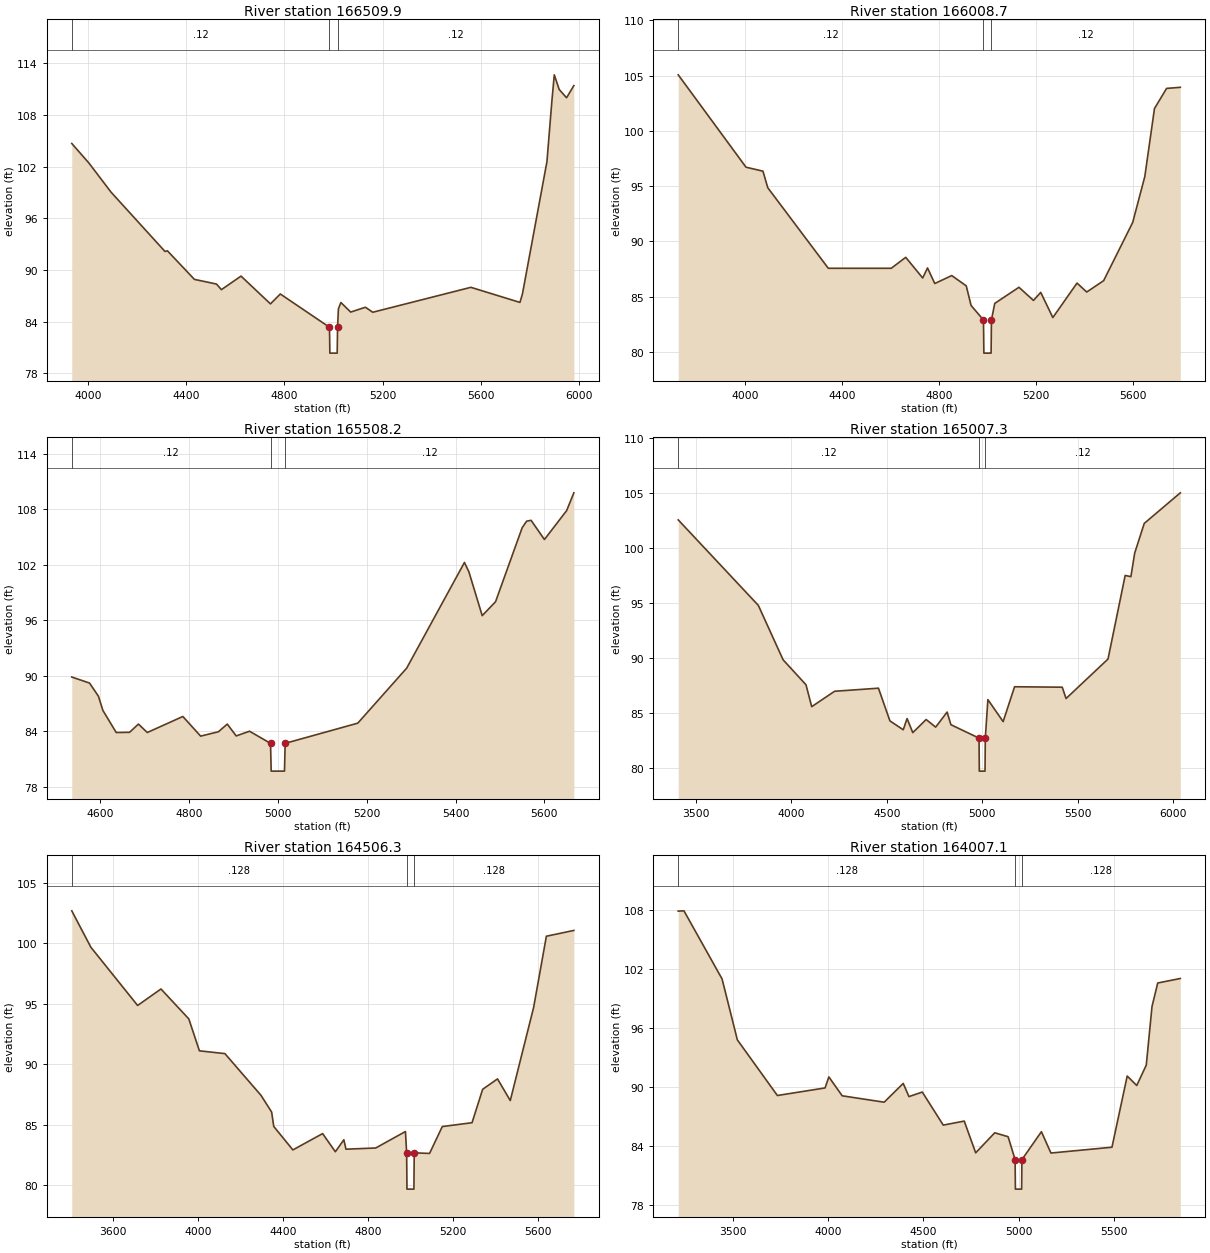
Type RM Length L Ch R = 1 ,166509.9,501.2,501.2,501.2
BEGIN DESCRIPTION:
Town Creek 331.0
END DESCRIPTION:
#Sta/Elev= 29
    3933  104.67    4003   102.4    4093   99.03    4313   92.15    4323   92.22
    4433   88.91    4523   88.37    4543   87.72    4623   89.29    4743   86.07
    4783   87.22  4983.6   83.36  4985.1   80.36    5015   80.36  5016.5   83.36
    5020   85.49    5030   86.23    5070   85.12    5130   85.68    5160    85.1
    5560   87.99    5760   86.24    5770    87.2    5870  102.55    5890  109.53
    5900  112.63    5920  110.93    5950  109.97  5979.7  111.38
#Mann= 3 , 1 , 0
 3933.00    0.12       0  4983.6    0.05       0  5016.5    0.12       0
Bank Sta=4983.60,5016.50
Exp/Cntr=0.3,0.1

Type RM Length L Ch R = 1 ,166008.7,500.5,500.5,500.5
BEGIN DESCRIPTION:
Town Creek 330.0
END DESCRIPTION:
#Sta/Elev= 30
  3722.3  105.07  4002.3   96.71  4072.3   96.35  4092.3   94.85  4342.3   87.56
  4602.3   87.56  4662.3   88.55  4732.3   86.68  4752.3   87.59  4782.3   86.18
  4852.3    86.9  4912.3   85.97  4932.3   84.19  4983.5   82.88    4985   79.88
  5014.9   79.88  5016.4   82.88    5030   84.38    5130   85.84    5190   84.65
    5220   85.38    5270    83.1    5370   86.22    5410   85.41    5480   86.44
    5600   91.71    5650   95.86    5690  102.02    5740  103.84  5796.7  103.94
#Mann= 3 , 1 , 0
 3722.30    0.12       0  4983.5    0.05       0  5016.4    0.12       0
Bank Sta=4983.50,5016.40
Exp/Cntr=0.3,0.1

Type RM Length L Ch R = 1 ,165508.2,500.9,500.9,500.9
BEGIN DESCRIPTION:
Town Creek 329.0
END DESCRIPTION:
#Sta/Elev= 30
  4536.3   89.87  4576.3   89.22  4596.3    87.8  4606.3   86.27  4636.3   83.88
  4666.3    83.9  4686.3   84.79  4706.3   83.88  4786.3   85.61  4826.3   83.49
  4866.3   83.96  4886.3   84.79  4906.3   83.51  4936.3   84.02  4983.6   82.71
  4985.1   79.71    5015   79.71  5016.5   82.71    5180   84.89    5290   90.83
    5420  102.24    5430  101.23    5460    96.5    5490      98    5550     106
    5560   106.7    5570  106.79    5600  104.72    5650  107.84  5666.2  109.76
#Mann= 3 , 1 , 0
 4536.30    0.12       0  4983.6    0.05       0  5016.5    0.12       0
Bank Sta=4983.60,5016.50
Exp/Cntr=0.3,0.1

Type RM Length L Ch R = 1 ,165007.3,501,501,501
BEGIN DESCRIPTION:
Town Creek 328.0
END DESCRIPTION:
#Sta/Elev= 30
  3406.2  102.53  3826.2   94.76  3956.2   89.81  4076.2   87.54  4106.2   85.55
  4226.2   86.95  4456.2   87.23  4516.2   84.26  4586.2   83.45  4606.2   84.47
  4636.2   83.19  4706.2   84.38  4756.2   83.69  4816.2   85.06  4836.2   83.91
  4983.6   82.69  4985.1   79.69    5015   79.69  5016.5   82.69    5030   86.19
    5110   84.19    5170   87.36    5420   87.32    5440   86.29    5660   89.88
    5750   97.48    5780   97.37    5800   99.52    5850  102.21  6039.1  104.99
#Mann= 3 , 1 , 0
 3406.20    0.12       0  4983.6    0.05       0  5016.5    0.12       0
Bank Sta=4983.60,5016.50
Exp/Cntr=0.3,0.1

Type RM Length L Ch R = 1 ,164506.3,499.2,499.2,499.2
BEGIN DESCRIPTION:
Town Creek 327.0
END DESCRIPTION:
#Sta/Elev= 30
  3405.5  102.67  3495.5   99.66  3715.5   94.85  3825.5   96.21  3956.5   93.74
  4006.5    91.1  4126.5   90.87  4296.5   87.42  4346.5   86.04  4356.5   84.85
  4446.5   82.91  4586.5   84.26  4646.5   82.76  4686.5   83.75  4696.5   82.97
  4836.5   83.07  4976.5   84.43  4982.1   82.67  4983.6   79.67  5016.3   79.67
  5017.8   82.67    5090   82.62    5150   84.84    5290   85.16    5340   87.92
    5410   88.78    5470   86.99    5580   94.69    5640  100.57  5769.3  101.05
#Mann= 3 , 1 , 0
 3405.50   0.128       0  4982.1    0.05       0  5017.8   0.128       0
Bank Sta=4982.10,5017.80
Exp/Cntr=0.3,0.1

Type RM Length L Ch R = 1 ,164007.1,643.3,643.3,643.3
BEGIN DESCRIPTION:
Town Creek 326.0
END DESCRIPTION:
#Sta/Elev= 30
  3215.3  107.93  3245.3  107.96  3445.3  101.03  3525.3   94.84  3735.3   89.18
  3985.3   89.95  4005.3   91.07  4075.3   89.15  4295.3    88.5  4395.3   90.41
  4425.3   89.07  4495.3   89.53  4605.3   86.17  4715.3   86.58  4775.3   83.35
  4875.3   85.39  4945.3   84.99  4982.1   82.66  4983.6   79.66  5016.3   79.66
  5017.8   82.66    5120    85.5    5170   83.33    5490   83.92    5570   91.16
    5620    90.2    5670   92.27    5700   98.22    5730  100.62  5848.5  101.08
#Mann= 3 , 1 , 0
 3215.30   0.128       0  4982.1    0.05       0  5017.8   0.128       0
Bank Sta=4982.10,5017.80
Exp/Cntr=0.3,0.1

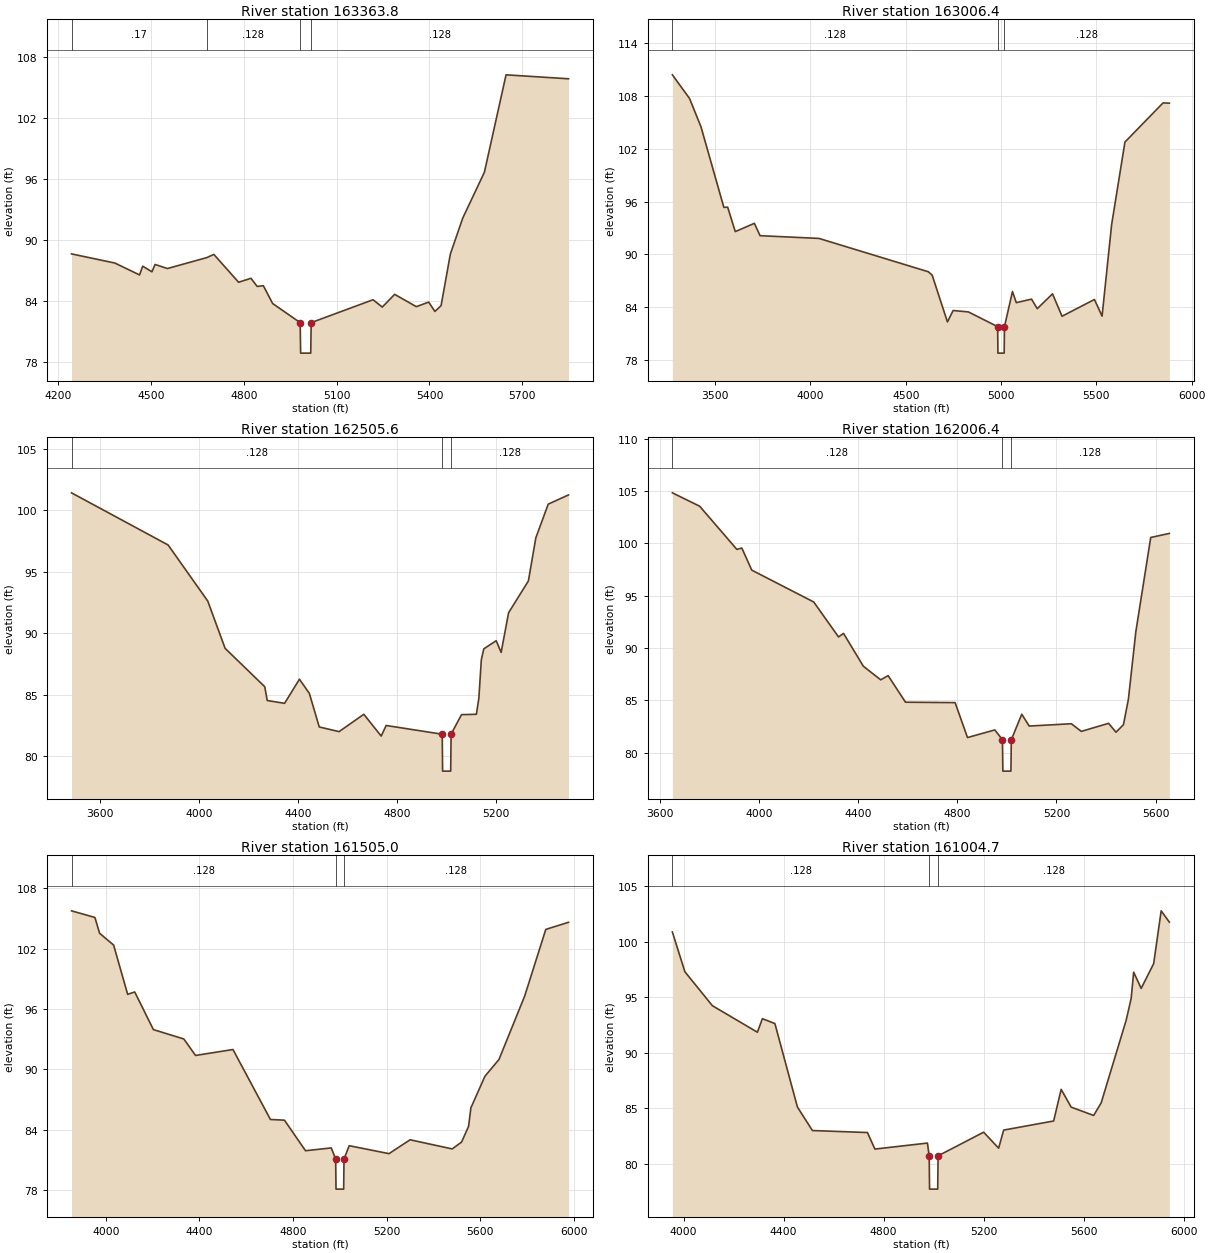
Type RM Length L Ch R = 1 ,163363.8,357.4,357.4,357.4
BEGIN DESCRIPTION:
Town Creek 325.0
END DESCRIPTION:
#Sta/Elev= 30
  4243.2   88.59  4383.2   87.69  4463.2   86.52  4473.2   87.38  4503.2   86.83
  4513.2   87.55  4553.2   87.15    4680   88.22  4703.2   88.54  4783.2    85.8
  4823.2   86.19  4843.2   85.39  4863.2   85.46  4893.2   83.71  4982.2   81.83
  4983.7   78.83  5016.3   78.83  5017.8   81.83  5217.6   84.08  5247.6   83.36
  5287.6   84.61  5357.6    83.4  5397.6   83.85  5417.6   82.93  5437.6    83.5
  5467.6   88.58  5507.6   92.11  5577.6   96.62  5647.6   106.2  5849.4  105.81
#Mann= 4 , 1 , 0
 4243.20    0.17       0    4680   0.128       0  4982.2    0.05       0
  5017.8   0.128       0
Bank Sta=4982.20,5017.80
Exp/Cntr=0.3,0.1

Type RM Length L Ch R = 1 ,163006.4,500.8,500.8,500.8
BEGIN DESCRIPTION:
Town Creek 324.0
END DESCRIPTION:
#Sta/Elev= 30
  3275.9  110.36  3365.9  107.68  3425.9  104.47  3545.9   95.34  3565.9   95.36
  3605.9   92.59  3705.9   93.53  3735.9   92.13  4044.9   91.82  4618.8   88.04
  4638.8   87.65  4718.8   82.36  4748.8   83.65  4828.8   83.49  4982.2   81.82
  4983.7   78.82  5016.4   78.82  5017.9   81.82    5060    85.8    5080   84.54
    5160   84.94    5190   83.86    5270   85.54    5320      83    5490    84.9
    5530   83.01    5580   93.36    5650  102.74    5850  107.18  5883.1  107.15
#Mann= 3 , 1 , 0
 3275.90   0.128       0  4982.2    0.05       0  5017.9   0.128       0
Bank Sta=4982.20,5017.90
Exp/Cntr=0.3,0.1

Type RM Length L Ch R = 1 ,162505.6,499.2,499.2,499.2
BEGIN DESCRIPTION:
Town Creek 323.0
END DESCRIPTION:
#Sta/Elev= 30
  3485.8  101.43  3875.8   97.19  4035.8   92.63  4105.8   88.79  4265.8   85.67
  4275.8   84.55  4345.8   84.32  4405.8   86.28  4445.8   85.13  4485.8    82.4
  4565.8   82.02  4665.8   83.43  4735.8   81.66  4755.8   82.52  4982.2   81.81
  4983.7   78.81  5016.4   78.81  5017.9   81.81    5060    83.4    5120   83.43
    5130   84.73    5140   87.86    5150   88.75    5200   89.41    5220   88.46
    5250   91.68    5330   94.27    5360   97.77    5410  100.51  5491.9  101.26
#Mann= 3 , 1 , 0
 3485.80   0.128       0  4982.2    0.05       0  5017.9   0.128       0
Bank Sta=4982.20,5017.90
Exp/Cntr=0.3,0.1

Type RM Length L Ch R = 1 ,162006.4,501.4,501.4,501.4
BEGIN DESCRIPTION:
Town Creek 322.0
END DESCRIPTION:
#Sta/Elev= 30
  3651.2  104.84  3761.2  103.56  3911.2   99.43  3931.2   99.56  3971.2   97.45
  4221.2    94.4  4321.2   91.06  4341.2    91.4  4421.2   88.26  4491.2   86.96
  4521.2   87.36  4591.2   84.82  4791.2   84.78  4841.2   81.44  4951.2   82.17
  4982.2   81.23  4983.7   78.23  5016.3   78.23  5017.8   81.23    5060   83.67
    5090   82.54    5260   82.76    5300   82.03    5410    82.8    5440   81.95
    5470   82.67    5490   85.11    5520   91.57    5580  100.57  5655.2  100.96
#Mann= 3 , 1 , 0
 3651.20   0.128       0  4982.2    0.05       0  5017.8   0.128       0
Bank Sta=4982.20,5017.80
Exp/Cntr=0.3,0.1

Type RM Length L Ch R = 1 ,161505.0,500.3,500.3,500.3
BEGIN DESCRIPTION:
Town Creek 321.0
END DESCRIPTION:
#Sta/Elev= 30
  3853.3  105.76  3953.3   105.1  3973.3  103.53  4033.3  102.35  4093.3   97.45
  4123.3   97.69  4203.3   93.94  4333.3   93.01  4383.3   91.37  4543.3   91.96
  4703.3      85  4763.3   84.93  4853.3   81.89  4963.3   82.17  4982.1   81.07
  4983.6   78.07  5016.3   78.07  5017.8   81.07    5040   82.39    5210    81.6
    5300   82.98    5480   82.07    5520   82.75    5550   84.31    5560   86.16
    5620    89.3    5680   90.97    5790   97.29    5880  103.91  5977.1  104.62
#Mann= 3 , 1 , 0
 3853.30   0.128       0  4982.1    0.05       0  5017.8   0.128       0
Bank Sta=4982.10,5017.80
Exp/Cntr=0.3,0.1

Type RM Length L Ch R = 1 ,161004.7,499.4,499.4,499.4
BEGIN DESCRIPTION:
Town Creek 320.0
END DESCRIPTION:
#Sta/Elev= 30
  3955.2  100.88  4005.2    97.3  4115.2   94.24  4295.2   91.85  4315.2   93.07
  4365.2   92.63  4455.2   85.11  4515.2   82.99  4735.2   82.81  4765.2   81.32
  4975.2   81.86  4982.2   80.71  4983.7   77.71  5016.3   77.71  5017.8   80.71
    5200   82.84    5260    81.4    5280   83.03    5480   83.85    5510    86.7
    5550    85.1    5640   84.35    5670   85.48    5770   92.93    5790    94.9
    5800   97.26    5830    95.8    5880   98.03    5910  102.79  5942.8  101.77
#Mann= 3 , 1 , 0
 3955.20   0.128       0  4982.2    0.05       0  5017.8   0.128       0
Bank Sta=4982.20,5017.80
Exp/Cntr=0.3,0.1

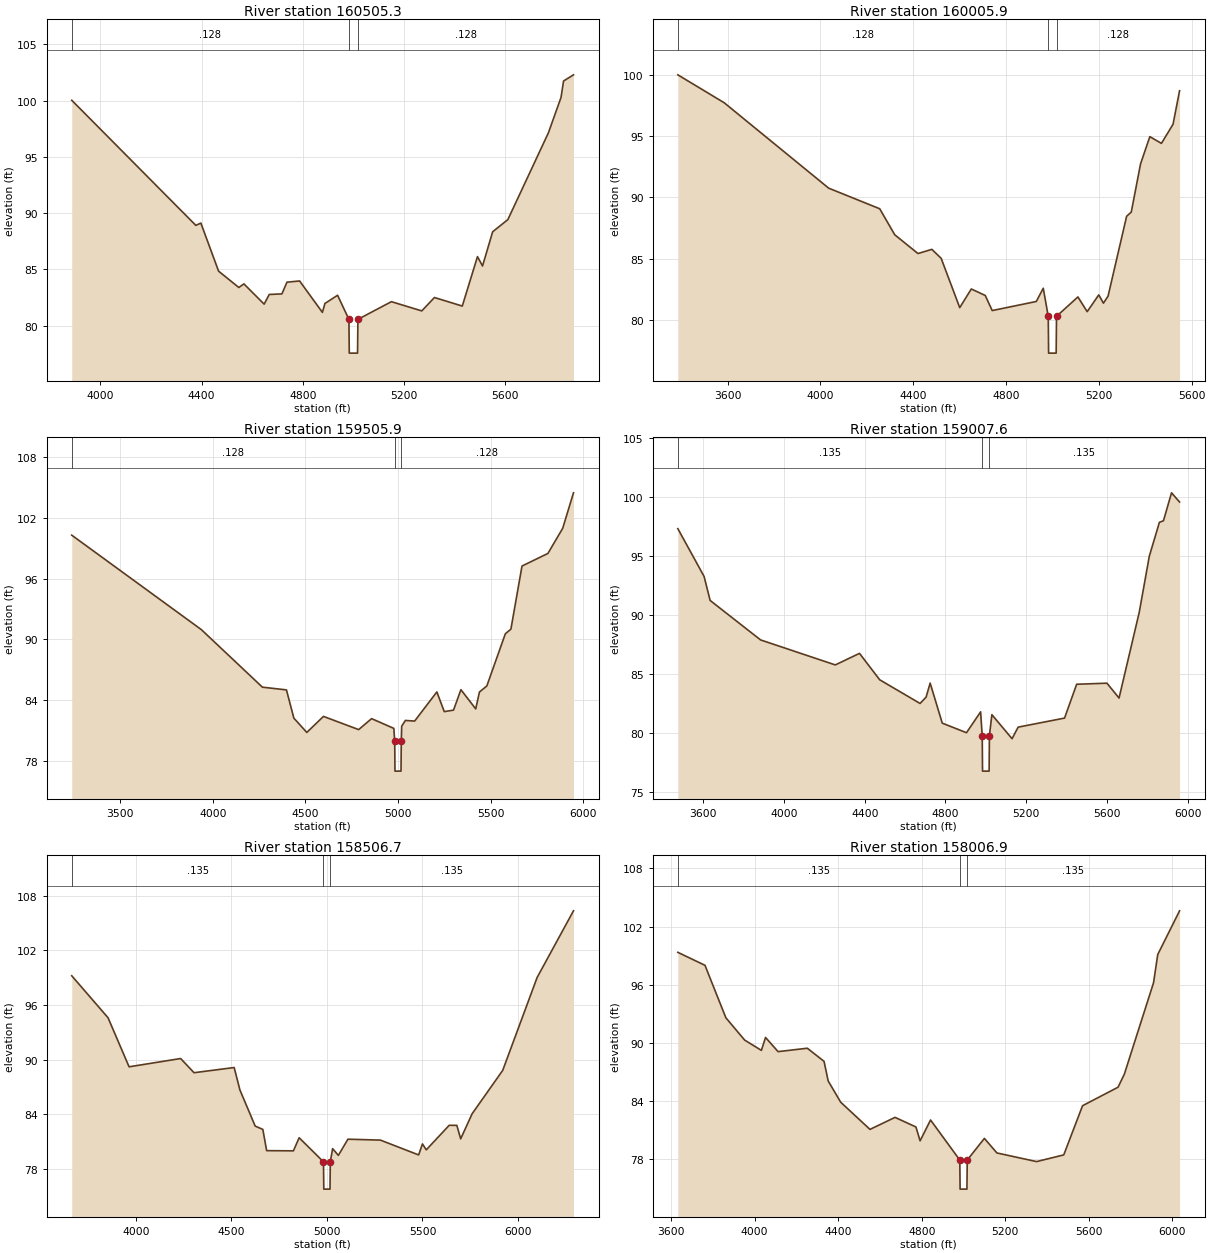
Type RM Length L Ch R = 1 ,160505.3,499.4,499.4,499.4
BEGIN DESCRIPTION:
Town Creek 319.0
END DESCRIPTION:
#Sta/Elev= 30
  3887.5  100.03  4377.5   88.92  4397.5   89.12  4467.5   84.85  4547.5    83.4
  4567.5   83.72  4647.5   81.92  4667.5   82.78  4717.5   82.83  4737.5   83.87
  4787.5   83.98  4877.5   81.19  4887.5   81.98  4937.5   82.71  4982.2   80.57
  4983.7   77.57  5016.3   77.57  5017.8   80.57    5150   82.14    5270   81.32
    5320   82.51    5430   81.75    5490   86.14    5510   85.31    5550   88.35
    5610   89.43    5770   97.13    5820  100.28    5830  101.74  5869.2  102.29
#Mann= 3 , 1 , 0
 3887.50   0.128       0  4982.2    0.05       0  5017.8   0.128       0
Bank Sta=4982.20,5017.80
Exp/Cntr=0.3,0.1

Type RM Length L Ch R = 1 ,160005.9,500,500,500
BEGIN DESCRIPTION:
Town Creek 318.0
END DESCRIPTION:
#Sta/Elev= 30
  3385.9   99.99  3585.9   97.71  4035.9   90.75  4255.9   89.07  4320.7   86.95
  4420.7   85.42  4480.7   85.76  4520.7   85.03  4600.7   81.01  4650.7   82.53
  4710.7      82  4740.7   80.77  4930.7   81.51  4960.7   82.59  4982.2    80.3
  4983.7    77.3  5016.3    77.3  5017.8    80.3    5110   81.88    5150   80.68
    5200   82.05    5220   81.37    5240   81.95    5320   88.46    5340    88.8
    5380   92.73    5420   94.95    5470    94.4    5520   95.96  5548.1   98.69
#Mann= 3 , 1 , 0
 3385.90   0.128       0  4982.2    0.05       0  5017.8   0.128       0
Bank Sta=4982.20,5017.80
Exp/Cntr=0.3,0.1

Type RM Length L Ch R = 1 ,159505.9,498.3,498.3,498.3
BEGIN DESCRIPTION:
Town Creek 317.0
END DESCRIPTION:
#Sta/Elev= 30
  3237.4  100.27  3937.4   90.97  4267.4    85.3  4397.4   85.03  4437.4   82.25
  4507.4   80.84  4597.4   82.42  4787.4   81.12  4857.4    82.2  4977.4   81.24
  4982.2   80.03  4983.7   77.03  5016.3   77.03  5017.8   80.03    5020   81.46
    5040   82.02    5090   81.96    5210   84.83    5250   82.89    5300   83.04
    5340   85.05    5420   83.16    5440   84.82    5480   85.42    5580   90.56
    5610   91.01    5670   97.23    5810   98.47    5890  100.95  5948.1  104.44
#Mann= 3 , 1 , 0
 3237.40   0.128       0  4982.2    0.05       0  5017.8   0.128       0
Bank Sta=4982.20,5017.80
Exp/Cntr=0.3,0.1

Type RM Length L Ch R = 1 ,159007.6,500.9,500.9,500.9
BEGIN DESCRIPTION:
Town Creek 316.0
END DESCRIPTION:
#Sta/Elev= 30
  3474.2   97.35  3604.2    93.3  3634.2   91.26  3884.2   87.91  4254.2   85.79
  4374.2   86.77  4474.2   84.53  4674.2   82.52  4704.2   83.06  4724.2   84.25
  4784.2   80.85  4904.2   80.04  4974.2   81.81  4982.2   79.78  4983.7   76.78
  5016.3   76.78  5017.8   79.78    5030   81.57    5130   79.53    5160   80.51
    5390   81.28    5450   84.15    5600   84.24    5660   82.98    5760   90.25
    5810   95.02    5860   97.89    5880   98.02    5920  100.39  5959.8   99.61
#Mann= 3 , 1 , 0
 3474.20   0.135       0  4982.2    0.05       0  5017.8   0.135       0
Bank Sta=4982.20,5017.80
Exp/Cntr=0.3,0.1

Type RM Length L Ch R = 1 ,158506.7,499.8,499.8,499.8
BEGIN DESCRIPTION:
Town Creek 315.0
END DESCRIPTION:
#Sta/Elev= 30
    3665   99.21    3855   94.59    3965    89.2  4234.8   90.11  4304.8   88.55
  4514.8   89.12  4544.8   86.66  4624.8   82.68  4664.8   82.32  4684.8   79.98
  4824.8   79.96  4854.8    81.4  4982.2   78.75  4983.7   75.75  5016.3   75.75
  5017.8   78.75    5030    80.2    5060   79.46    5110   81.24    5280   81.14
    5480   79.51    5500   80.72    5520   80.07    5640   82.77    5680   82.76
    5700   81.28    5760   84.04    5920   88.81    6100   99.02  6290.2  106.35
#Mann= 3 , 1 , 0
 3665.00   0.135       0  4982.2    0.05       0  5017.8   0.135       0
Bank Sta=4982.20,5017.80
Exp/Cntr=0.3,0.1

Type RM Length L Ch R = 1 ,158006.9,499.1,499.1,499.1
BEGIN DESCRIPTION:
Town Creek 314.0
END DESCRIPTION:
#Sta/Elev= 30
  3632.2   99.34  3762.2      98  3862.2   92.59  3952.2   90.29  4032.2   89.23
  4052.2   90.56  4112.2    89.1  4252.2   89.45  4332.2    88.1  4352.2   86.07
  4412.2   83.88  4552.2   81.08  4672.2   82.32  4772.2   81.33  4792.2    79.9
  4842.2   82.05  4982.2   77.92  4983.7   74.92  5016.4   74.92  5017.9   77.92
    5100   80.15    5160   78.65    5350   77.76    5480   78.45    5570   83.52
    5740   85.43    5770   86.77    5910   96.21    5930   99.11  6034.5  103.62
#Mann= 3 , 1 , 0
 3632.20   0.135       0  4982.2    0.05       0  5017.9   0.135       0
Bank Sta=4982.20,5017.90
Exp/Cntr=0.3,0.1

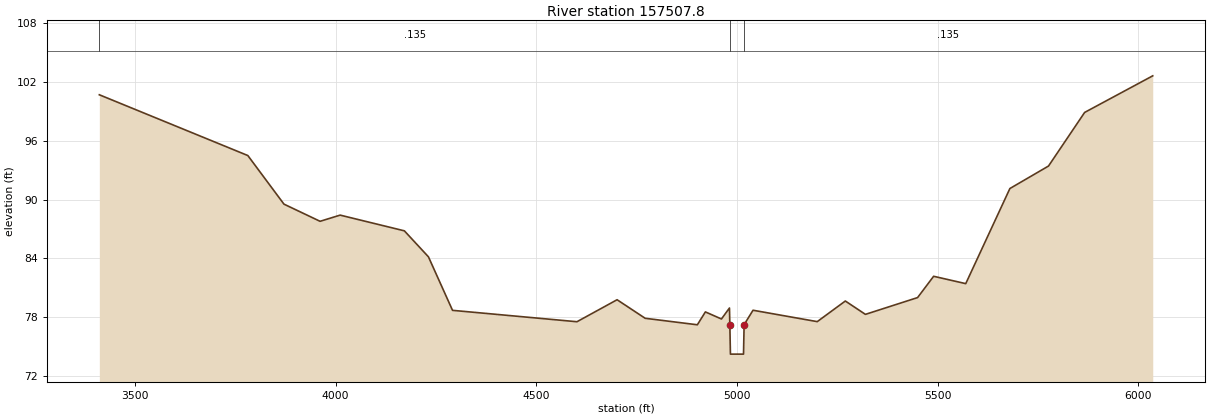
Type RM Length L Ch R = 1 ,157507.8,501.5,501.5,501.5
BEGIN DESCRIPTION:
Town Creek 313.0
END DESCRIPTION:
#Sta/Elev= 30
  3411.3  100.67  3781.3   94.48  3871.3   89.53  3961.3   87.78  4011.3   88.41
  4171.3   86.81  4231.3   84.16  4291.3   78.71  4601.3   77.55  4701.3   79.79
  4771.3    77.9  4901.3   77.24  4921.3   78.55  4961.3   77.83  4981.3   78.95
  4982.2   77.25  4983.7   74.25  5016.3   74.25  5017.8   77.25    5040   78.72
    5200   77.56    5270   79.66    5320    78.3    5450   80.01    5490   82.18
    5570   81.43    5680   91.12  5776.2   93.41  5866.2   98.87  6035.9   102.6
#Mann= 3 , 1 , 0
 3411.30   0.135       0  4982.2    0.05       0  5017.8   0.135       0
Bank Sta=4982.20,5017.80
Exp/Cntr=0.3,0.1