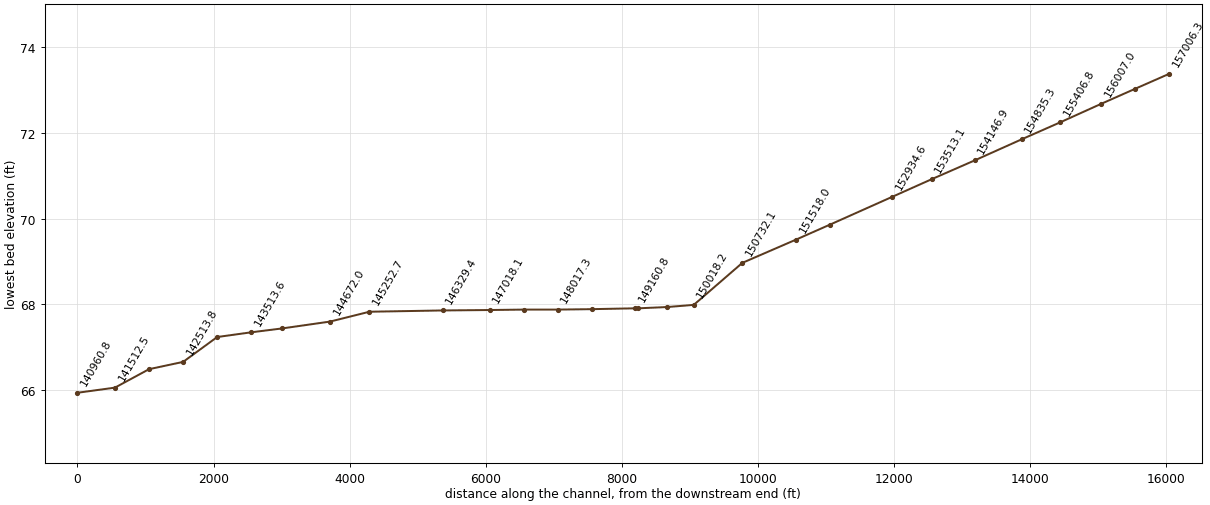
HEC-RAS study Town_Creek_FINAL.prj: Town Creek

--- Town_Creek_FINAL.g01 (geometry) --- (continued)

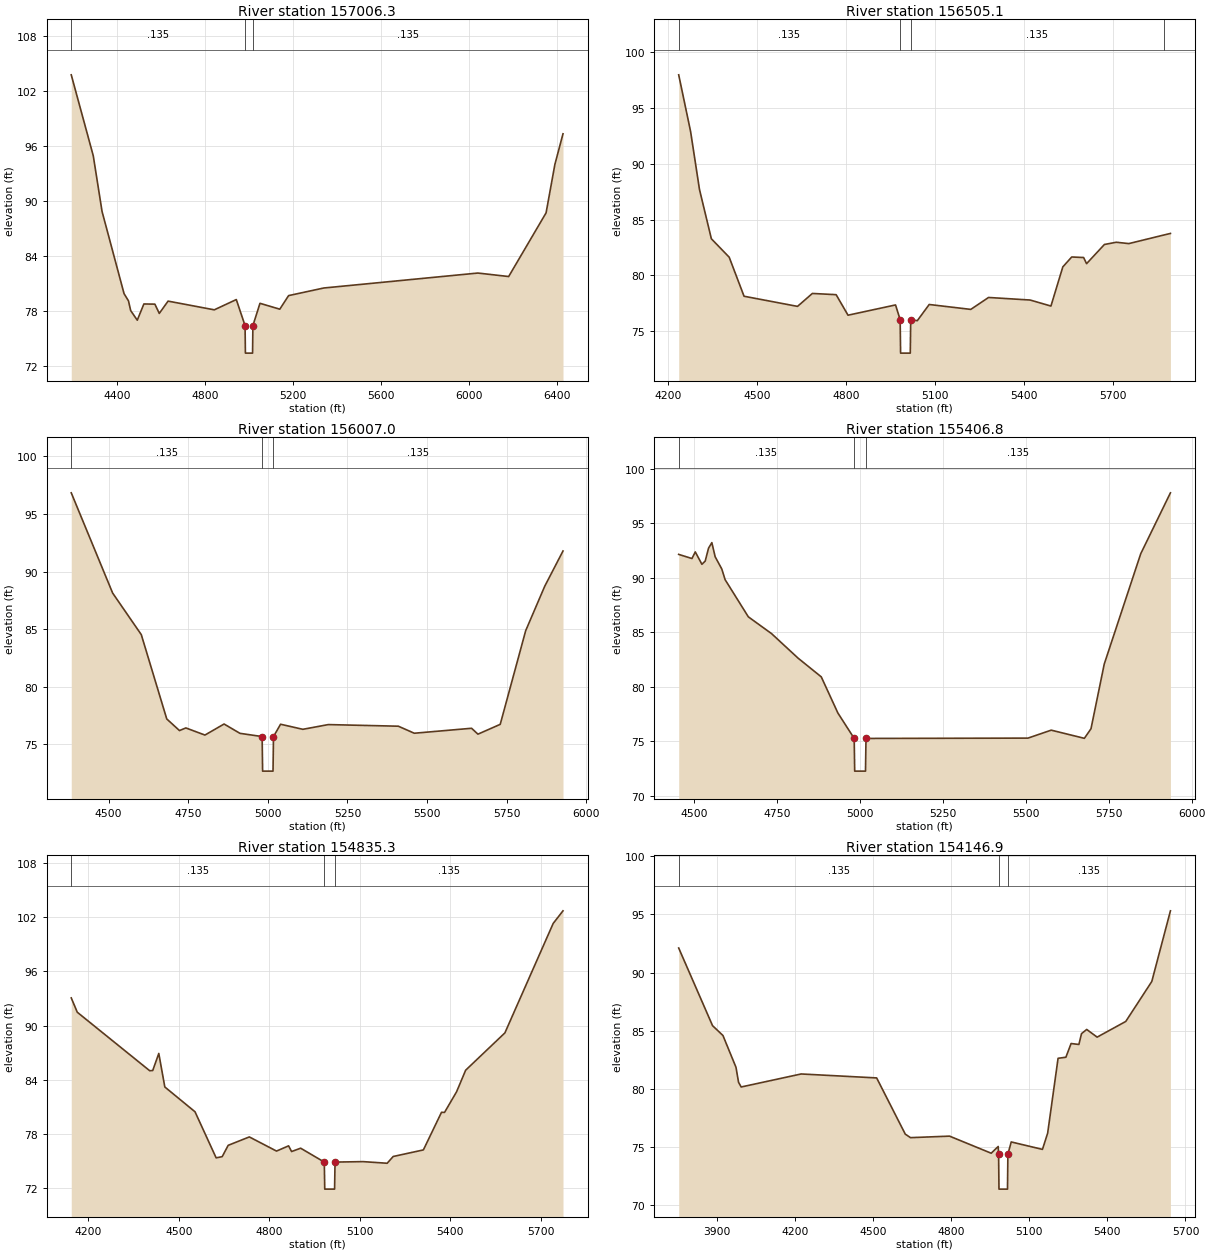
Type RM Length L Ch R = 1 ,157006.3,501.2,501.2,501.2
BEGIN DESCRIPTION:
Town Creek 312.0
END DESCRIPTION:
#Sta/Elev= 26
  4192.4  103.72  4292.4    94.9  4332.4   88.82  4432.4   79.86  4452.4   79.08
  4462.4   78.02  4492.4   76.97  4522.4   78.74  4572.4   78.72  4592.4   77.71
  4632.4   79.05  4842.4    78.1  4942.4   79.22  4982.2   76.38  4983.7   73.38
  5016.3   73.38  5017.8   76.38    5050   78.81    5140   78.17    5180   79.65
    5340   80.48    6040   82.11    6180   81.73    6350   88.67    6390   93.95
  6426.9   97.29
#Mann= 3 , 1 , 0
 4192.40   0.135       0  4982.2    0.05       0  5017.8   0.135       0
Bank Sta=4982.20,5017.80
Exp/Cntr=0.3,0.1

Type RM Length L Ch R = 1 ,156505.1,498.1,498.1,498.1
BEGIN DESCRIPTION:
Town Creek 311.0
END DESCRIPTION:
#Sta/Elev= 30
  4236.7   97.98  4276.7   92.91  4306.7    87.7  4346.7   83.28  4406.7   81.63
  4456.7   78.13  4636.7   77.22  4686.7   78.38  4766.7   78.27  4806.7   76.43
  4966.7   77.35  4982.2   76.03  4983.7   73.03  5016.3   73.03  5017.8   76.03
    5040   75.94    5080   77.39    5220   76.95  5279.8   78.02  5419.8   77.79
  5489.8   77.25  5529.8   80.76  5559.8   81.65  5599.8    81.6  5609.8   81.05
  5669.8   82.77  5709.8   82.97  5752.1   82.85    5870   83.62  5892.1   83.76
#Mann= 4 , 1 , 0
 4236.70   0.135       0  4982.2    0.05       0  5017.8   0.135       0
    5870    0.18       0
Bank Sta=4982.20,5017.80
Exp/Cntr=0.3,0.1

Type RM Length L Ch R = 1 ,156007.0,600.2,600.2,600.2
BEGIN DESCRIPTION:
Town Creek 310.0
END DESCRIPTION:
#Sta/Elev= 24
  4382.5   96.84  4512.5   88.14  4602.5   84.53  4682.5   77.21  4722.5    76.2
  4742.5   76.43  4802.5   75.81  4862.5   76.77  4912.5   75.96  4982.1   75.68
  4983.6   72.68  5016.3   72.68  5017.8   75.68    5040   76.75    5110   76.31
    5190   76.72    5410   76.58    5460   75.97    5640    76.4    5660   75.89
    5730   76.74    5810   84.87    5870   88.74  5927.2   91.79
#Mann= 3 , 1 , 0
 4382.50   0.135       0  4982.1    0.05       0  5017.8   0.135       0
Bank Sta=4982.10,5017.80
Exp/Cntr=0.3,0.1

Type RM Length L Ch R = 1 ,155406.8,571.5,571.5,571.5
BEGIN DESCRIPTION:
Town Creek 309.0
END DESCRIPTION:
#Sta/Elev= 26
  4452.9   92.14  4492.9   91.76  4502.9   92.37  4522.9   91.23  4532.9   91.53
  4542.9   92.71  4552.9   93.22  4562.9   91.92  4582.9    90.8  4592.9   89.82
  4662.9   86.41  4732.9   84.87  4812.9   82.62  4882.9    80.9  4932.9   77.59
  4982.2   75.25  4983.7   72.25  5016.3   72.25  5017.8   75.25  5506.4   75.28
  5576.4   76.01  5676.4   75.26  5696.4   76.14  5736.4   82.08  5846.4    92.2
    5936   97.79
#Mann= 3 , 1 , 0
 4452.90   0.135       0  4982.2    0.05       0  5017.8   0.135       0
Bank Sta=4982.20,5017.80
Exp/Cntr=0.3,0.1

Type RM Length L Ch R = 1 ,154835.3,688.4,688.4,688.4
BEGIN DESCRIPTION:
Town Creek 308.0
END DESCRIPTION:
#Sta/Elev= 30
  4143.9   93.06  4163.9   91.47  4403.9   84.98  4413.9   85.01  4433.9    86.9
  4453.9   83.18  4553.9   80.43  4623.9   75.32  4643.9   75.45  4663.9   76.71
  4733.9   77.64  4823.9   76.07  4863.9   76.65  4873.9   76.02  4903.9   76.39
  4982.2   74.85  4983.7   71.85  5016.3   71.85  5017.8   74.85  5110.5    74.9
  5190.5   74.72  5210.5   75.47  5310.5    76.2  5370.5   80.37  5380.5   80.36
  5420.5   82.65  5450.5   85.04  5580.5   89.18  5740.5  101.32    5773  102.72
#Mann= 3 , 1 , 0
 4143.90   0.135       0  4982.2    0.05       0  5017.8   0.135       0
Bank Sta=4982.20,5017.80
Exp/Cntr=0.3,0.1

Type RM Length L Ch R = 1 ,154146.9,633.8,633.8,633.8
BEGIN DESCRIPTION:
Town Creek 306.0
END DESCRIPTION:
#Sta/Elev= 30
  3753.4   92.11  3883.4   85.43  3923.4   84.58  3973.4   81.85  3983.4   80.55
  3993.4   80.15  4223.8   81.27  4513.8   80.93  4623.8   76.09  4643.8   75.79
  4793.8   75.92  4953.8   74.45  4980.7   75.03  4982.2   74.36  4983.7   71.36
  5016.4   71.36  5017.9   74.36  5030.7   75.42  5150.7   74.78  5170.7   76.18
  5210.7   82.62  5240.7   82.71  5260.7   83.89  5290.7   83.81  5300.7   84.74
  5320.7    85.1  5360.7   84.44  5470.7   85.79  5570.7   89.23  5642.3   95.31
#Mann= 3 , 1 , 0
 3753.40   0.135       0  4982.2    0.05       0  5017.9   0.135       0
Bank Sta=4982.20,5017.90
Exp/Cntr=0.3,0.1

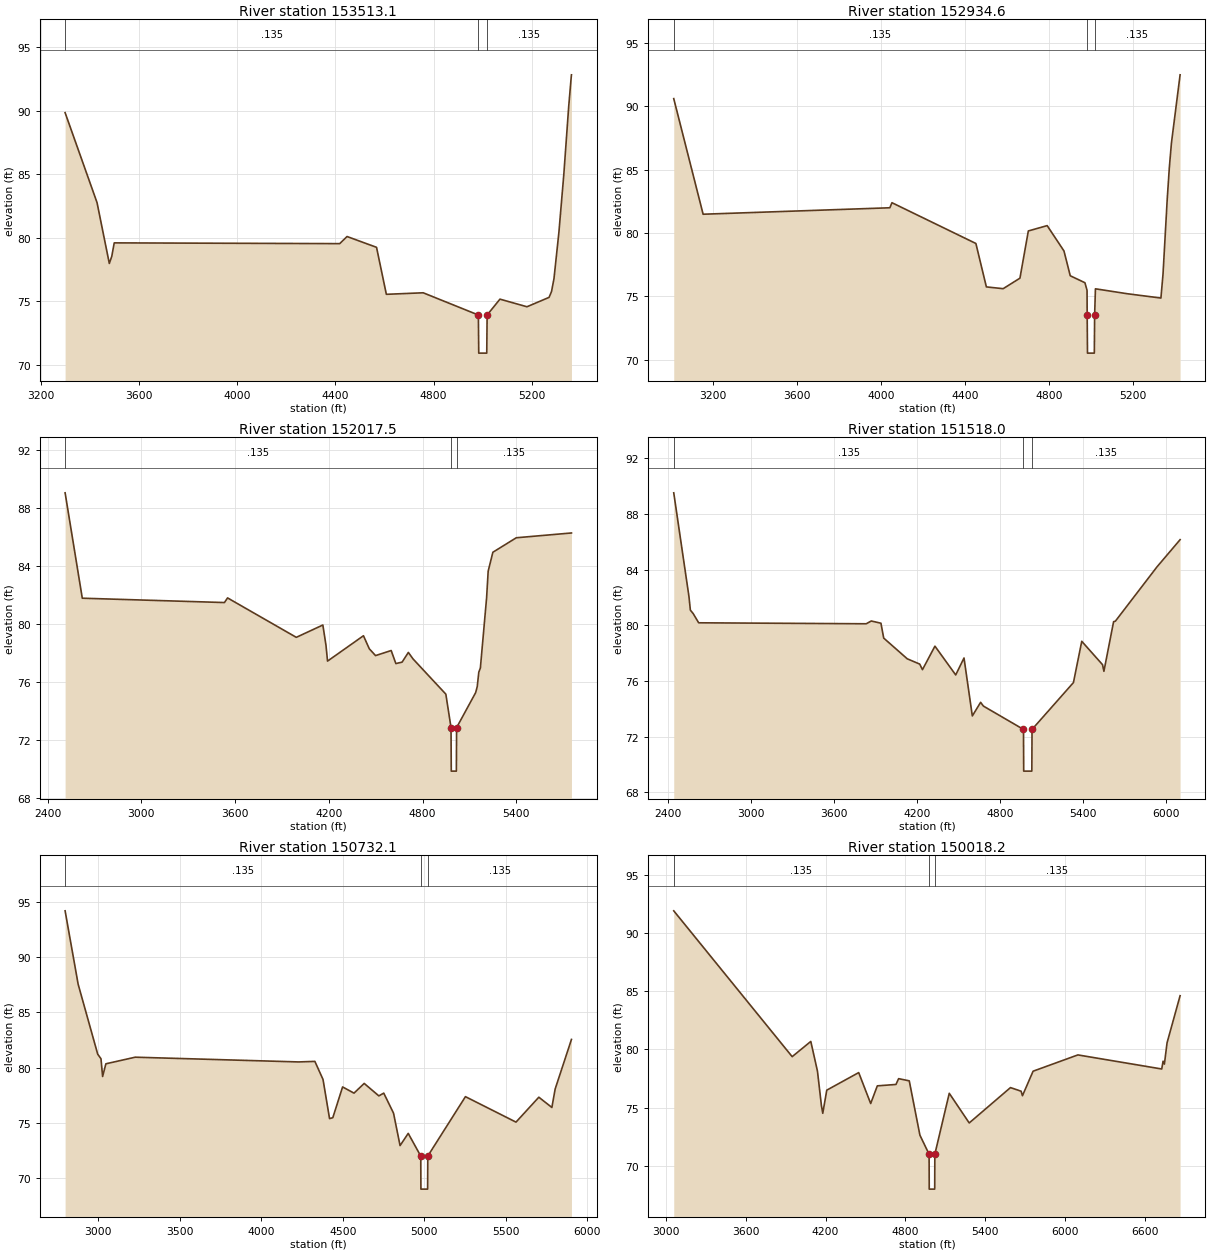
Type RM Length L Ch R = 1 ,153513.1,578.5,578.5,578.5
BEGIN DESCRIPTION:
Town Creek 305.0
END DESCRIPTION:
#Sta/Elev= 24
  3299.8   89.85  3429.8   82.77  3479.8   77.98  3489.8   78.54  3499.8    79.6
  4417.6   79.54  4447.6    80.1  4567.6   79.25  4607.6   75.55  4757.6   75.67
  4982.2   73.92  4983.7   70.92  5016.3   70.92  5017.8   73.92    5070   75.17
    5180   74.57    5270   75.31    5280   75.77    5290   76.79    5310   80.43
    5330   84.99    5350   90.36    5360   92.62  5361.1   92.83
#Mann= 3 , 1 , 0
 3299.80   0.135       0  4982.2    0.05       0  5017.8   0.135       0
Bank Sta=4982.20,5017.80
Exp/Cntr=0.3,0.1

Type RM Length L Ch R = 1 ,152934.6,917.1,917.1,917.1
BEGIN DESCRIPTION:
Town Creek 304.0
END DESCRIPTION:
#Sta/Elev= 26
  3011.8   90.61  3151.8   81.48  4041.8   81.99  4051.8   82.39  4451.8   79.17
  4501.8   75.74  4581.8    75.6  4661.8   76.43  4701.8   80.16  4791.6   80.58
  4871.6   78.58  4901.6   76.62  4971.6   76.07  4981.6   75.47  4982.2   73.51
  4983.7   70.51  5016.3   70.51  5017.8   73.51  5021.6   75.59  5173.7    75.2
  5333.7   74.86  5343.7   76.75  5363.7   82.65  5373.7   85.13  5383.7   87.09
  5425.1   92.49
#Mann= 3 , 1 , 0
 3011.80   0.135       0  4982.2    0.05       0  5017.8   0.135       0
Bank Sta=4982.20,5017.80
Exp/Cntr=0.3,0.1

Type RM Length L Ch R = 1 ,152017.5,499.5,499.5,499.5
BEGIN DESCRIPTION:
Town Creek 302.0
END DESCRIPTION:
#Sta/Elev= 30
  2511.6   89.06  2621.6   81.79  3531.6   81.49  3551.6   81.81  3991.6   79.09
  4161.6   79.94  4181.6   78.55  4191.6   77.45  4421.6    79.2    4459    78.3
    4499   77.83    4599   78.18    4629   77.28    4669   77.38    4709   78.05
    4739    77.6    4949   75.17  4982.2   72.86  4983.7   69.86  5016.3   69.86
  5017.8   72.86    5140   75.28    5150   75.69    5160   76.69    5170   76.97
    5210   81.83    5220   83.66    5250   84.96    5400   85.96  5753.1   86.29
#Mann= 3 , 1 , 0
 2511.60   0.135       0  4982.2    0.05       0  5017.8   0.135       0
Bank Sta=4982.20,5017.80
Exp/Cntr=0.3,0.1

Type RM Length L Ch R = 1 ,151518.0,785.9,785.9,785.9
BEGIN DESCRIPTION:
Town Creek 301.0
END DESCRIPTION:
#Sta/Elev= 30
  2443.1   89.53  2553.1   82.06  2563.1   81.09  2583.1   80.85  2623.1   80.18
  3833.1   80.11  3869.6   80.31  3939.6   80.15  3959.6   79.08  4129.6   77.59
  4219.6   77.21  4239.6   76.81  4329.6    78.5  4479.6   76.43  4539.6   77.65
  4599.6   73.48  4659.6   74.46  4679.6   74.19  4969.2   72.51  4970.7   69.51
  5029.4   69.51  5030.9   72.51    5330   75.88    5390   78.85    5540   77.17
    5550   76.69    5620   80.26  5633.1    80.3  5933.1    84.2  6100.3   86.16
#Mann= 3 , 1 , 0
 2443.10   0.135       0  4969.2    0.05       0  5030.9   0.135       0
Bank Sta=4969.20,5030.90
Exp/Cntr=0.3,0.1

Type RM Length L Ch R = 1 ,150732.1,713.9,713.9,713.9
BEGIN DESCRIPTION:
Town Creek 299.0
END DESCRIPTION:
#Sta/Elev= 30
  2797.7   94.22  2877.7   87.56  2997.7   81.21  3017.7    80.8  3027.7   79.19
  3047.7   80.34  3227.7   80.94  4229.2   80.51  4329.2   80.56  4379.2   78.92
  4419.2   75.37  4439.2   75.45  4499.2   78.24  4569.2   77.68  4631.6   78.56
  4721.6   77.43  4751.6   77.68  4811.6   75.86  4851.6   72.92  4901.6   74.03
 4978.37   71.97 4979.42   68.97 5020.51   68.97 5021.56   71.97  5252.5   77.36
  5562.5   75.05  5702.5   77.31  5782.5   76.38  5802.5   78.05  5902.5   82.55
#Mann= 3 , 1 , 0
 2797.70   0.135       0 4978.37    0.05       0 5021.56   0.135       0
Bank Sta=4978.37,5021.56
Exp/Cntr=0.3,0.1

Type RM Length L Ch R = 1 ,150018.2,387,387,387
BEGIN DESCRIPTION:
Town Creek 298.0
END DESCRIPTION:
#Sta/Elev= 30
  3059.4   91.92  3949.4   79.38  4089.4   80.69  4139.4   78.14  4169.4   75.16
  4179.4   74.51  4209.4    76.5  4449.4   78.01  4539.4   75.35  4589.4   76.87
  4729.4   76.99  4749.4   77.49  4829.4    77.3  4909.4   72.63 4978.44   70.99
 4979.49   67.99 5020.58   67.99 5021.63   70.99    5130   76.23    5280   73.68
    5590   76.72    5670   76.41    5680   76.02    5760   78.13  6096.8   79.53
  6726.8   78.32  6736.8   78.99  6746.8   78.74  6766.8   80.57  6864.8   84.62
#Mann= 3 , 1 , 0
 3059.40   0.135       0 4978.44    0.05       0 5021.63   0.135       0
Bank Sta=4978.44,5021.63
Exp/Cntr=0.3,0.1

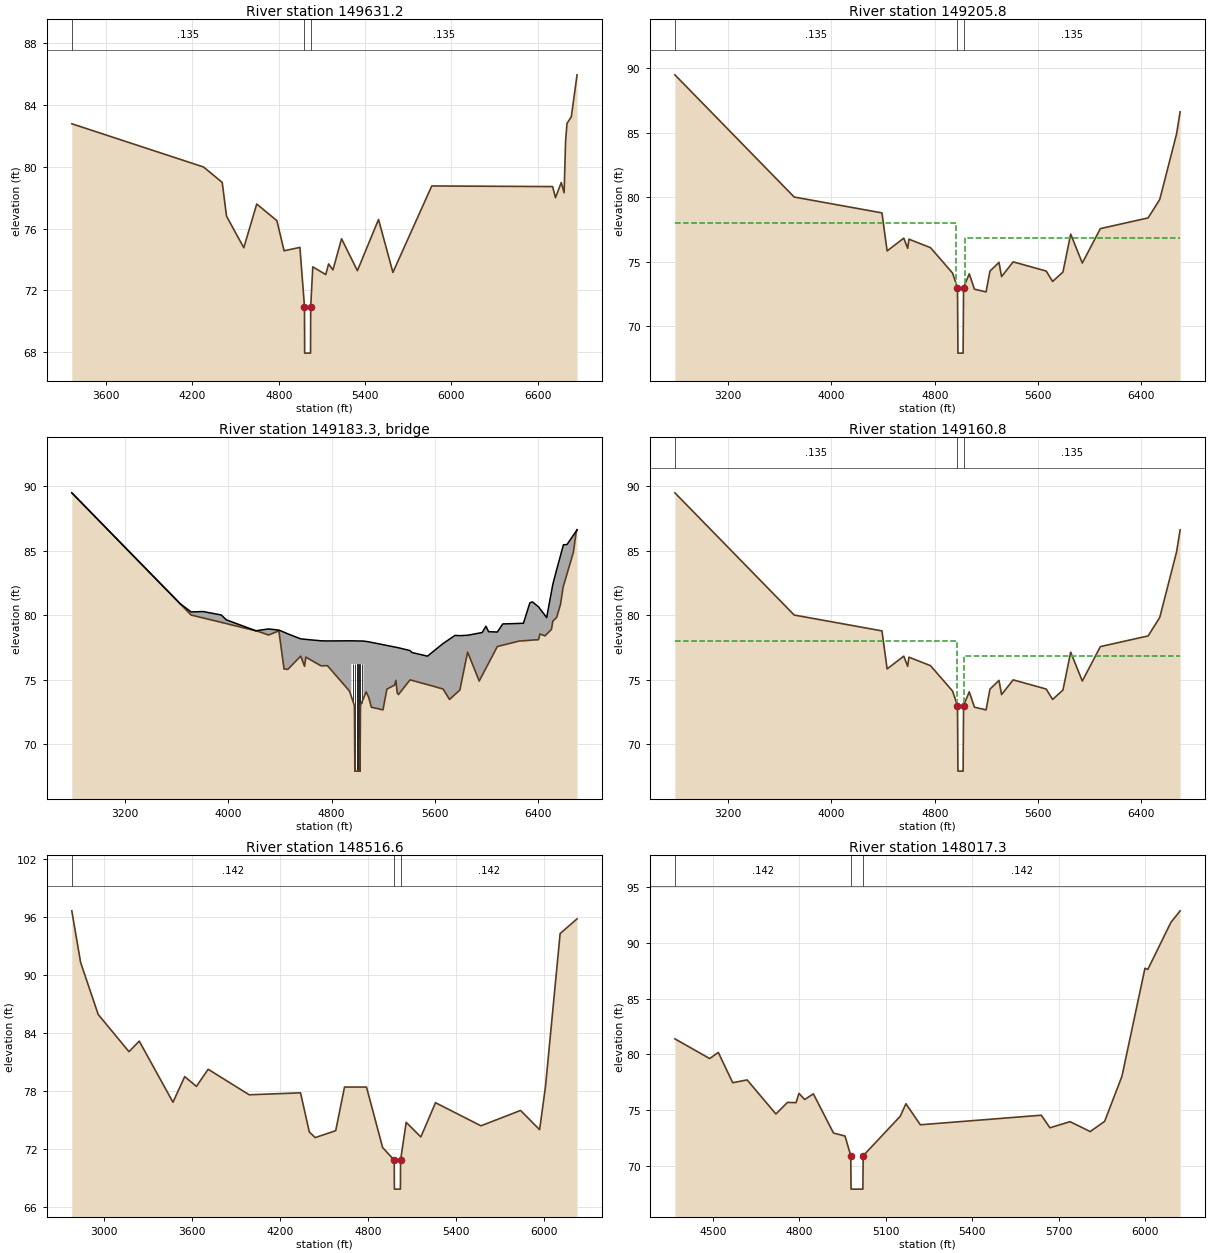
Type RM Length L Ch R = 1 ,149631.2,425.4,425.4,425.4
BEGIN DESCRIPTION:
Town Creek 297.0
END DESCRIPTION:
#Sta/Elev= 30
  3361.2    82.8  4276.6      80  4406.6      79  4436.6   76.81  4556.6   74.77
  4646.6    77.6  4786.6   76.52  4836.6   74.57  4946.6   74.79 4978.44   70.94
 4979.49   67.94 5020.51   67.94 5021.56   70.94  5036.1   73.53  5126.1   73.03
  5146.1   73.72  5176.1   73.33  5236.1   75.35  5346.1   73.28    5493    76.6
    5593   73.17  5862.9   78.77  6702.9   78.73  6722.9   78.01  6762.9   78.99
  6782.9   78.33  6792.9   81.65  6802.9   82.82  6832.9   83.25  6872.8   85.97
#Mann= 3 , 1 , 0
 3361.20   0.135       0 4978.44    0.05       0 5021.56   0.135       0
Bank Sta=4978.44,5021.56
Exp/Cntr=0.5,0.3

Type RM Length L Ch R = 1 ,149205.8,45,45,45
BEGIN DESCRIPTION:
Upstream Section of Bridge/Culvert/Weir
END DESCRIPTION:
#Sta/Elev= 30
  2786.8    89.5  3711.1   80.02  4391.2   78.79  4431.2   75.84  4560.4   76.83
  4590.4   76.04  4600.4   76.75  4767.6   76.09  4937.6   74.13  4976.5      73
    4980   67.91    5020   67.91  5023.5      73  5067.6   74.06    5108   72.87
    5198   72.66    5228   74.27    5298   74.95    5318   73.85    5408   74.99
  5663.6   74.28  5713.6   73.47  5793.6    74.2  5853.6   77.14  5943.6    74.9
  6083.6   77.57  6453.6    78.4  6543.6   79.83  6673.6    84.9  6701.7   86.63
#Mann= 3 , 1 , 0
 2786.80   0.135       0  4976.5    0.05       0  5023.5   0.135       0
#XS Ineff= 2 , 0
       0  4966.5   78.01  5033.5       0   76.83
Bank Sta=4976.50,5023.50
Exp/Cntr=0.5,0.3

Type RM Length L Ch R = 3 ,149183.3,,,
BEGIN DESCRIPTION:
Town Creek Road - TOR
Structure ID: Town Creek Road
Approximate Survey Structure
END DESCRIPTION:
Bridge Culvert--1,0,-1,-1, 0
Deck Dist Width WeirC Skew NumUp NumDn MinLoCord MaxHiCord MaxSubmerge Is_Ogee
10,25,2.6,, 60, 60,,,0.95,0,1,1,,
  2786.8  3625.3  3711.1  3805.3  3945.3  3983.2  4213.2  4311.2  4391.2  4431.2
  4460.4  4560.4  4590.4  4600.4  4717.6  4767.6  4937.6 4952.91    4953 5046.89
    5047  5067.6  5087.6    5108    5198    5228    5288    5298    5308    5318
    5408  5422.4  5542.4  5663.6  5713.6  5756.1  5793.6  5853.6  5943.6  5966.1
  5996.1  6016.1  6083.6  6126.1  6286.1  6336.1  6356.1  6403.6  6413.6  6453.6
  6466.1  6503.6  6513.6  6543.6  6573.6  6596.1  6623.9  6673.6  6693.6  6701.7
    89.5   80.91   80.26   80.29   80.02   79.65    78.8   78.94   78.85   78.69
   78.56   78.17   78.14   78.13   78.02   78.01   78.02   78.02   78.02      78
      78   77.97   77.94    77.9   77.72   77.66   77.54   77.52    77.5   77.48
   77.26   77.11   76.83   77.81   78.15   78.44   78.42   78.45   78.62   78.66
   79.15   78.73    78.7   79.33   79.38   80.97   81.04   80.65   80.51   79.99
   79.82   81.85   82.39   83.54   84.64   85.47   85.49   86.22   86.51   86.63
    89.5    80.9   80.02   79.79   79.45   79.36   78.79   78.47   78.79   75.84
    75.8   76.83   76.04   76.75   76.08   76.09   74.13   73.69   76.22    76.2
   73.56   74.06   73.63   72.87   72.66   74.27   74.58   74.95   73.98   73.85
   74.99   74.95   74.62   74.28   73.47   73.86    74.2   77.14    74.9   75.33
    75.9   76.28   77.57   77.68   78.02   78.06   78.08   78.11   78.55    78.4
   78.53   78.91   79.54   79.83   80.85   82.27   83.21    84.9   86.37   86.63
  2786.8  3625.3  3711.1  3805.3  3945.3  3983.2  4213.2  4311.2  4391.2  4431.2
  4460.4  4560.4  4590.4  4600.4  4717.6  4767.6  4937.6 4952.91    4953 5046.89
    5047  5067.6  5087.6    5108    5198    5228    5288    5298    5308    5318
    5408  5422.4  5542.4  5663.6  5713.6  5756.1  5793.6  5853.6  5943.6  5966.1
  5996.1  6016.1  6083.6  6126.1  6286.1  6336.1  6356.1  6403.6  6413.6  6453.6
  6466.1  6503.6  6513.6  6543.6  6573.6  6596.1  6623.9  6673.6  6693.6  6701.7
    89.5   80.91   80.26   80.29   80.02   79.65    78.8   78.94   78.85   78.69
   78.56   78.17   78.14   78.13   78.02   78.01   78.02   78.02   78.02      78
      78   77.97   77.94    77.9   77.72   77.66   77.54   77.52    77.5   77.48
   77.26   77.11   76.83   77.81   78.15   78.44   78.42   78.45   78.62   78.66
   79.15   78.73    78.7   79.33   79.38   80.97   81.04   80.65   80.51   79.99
   79.82   81.85   82.39   83.54   84.64   85.47   85.49   86.22   86.51   86.63
    89.5    80.9   80.02   79.79   79.45   79.36   78.79   78.47   78.79   75.84
    75.8   76.83   76.04   76.75   76.08   76.09   74.13   73.69   76.22    76.2
   73.56   74.06   73.63   72.87   72.66   74.27   74.58   74.95   73.98   73.85
   74.99   74.95   74.62   74.28   73.47   73.86    74.2   77.14    74.9   75.33
    75.9   76.28   77.57   77.68   78.02   78.06   78.08   78.11   78.55    78.4
   78.53   78.91   79.54   79.83   80.85   82.27   83.21    84.9   86.37   86.63
Pier Skew, UpSta & Num, DnSta & Num=,4968.0, 2 ,4968.0, 2 , 0 , 0 , 0 ,,
       1       1
   72.23   77.22
       1       1
   72.23   77.22
Pier Skew, UpSta & Num, DnSta & Num=,4984.0, 2 ,4984.0, 2 , 0 , 0 , 0 ,,
       1       1
   66.91   77.22
       1       1
   66.91   77.22
Pier Skew, UpSta & Num, DnSta & Num=,5000.0, 2 ,5000.0, 2 , 0 , 0 , 0 ,,
       1       1
   66.91   77.22
       1       1
   66.91   77.22
Pier Skew, UpSta & Num, DnSta & Num=,5016.0, 2 ,5016.0, 2 , 0 , 0 , 0 ,,
       1       1
   66.91   77.22
       1       1
   66.91   77.22
Pier Skew, UpSta & Num, DnSta & Num=,5032.0, 2 ,5032.0, 2 , 0 , 0 , 0 ,,
       1       1
    72.2   77.22
       1       1
    72.2   77.22
Abutment Skew #Up #Dn=, 2 , 2
 4952.80 4960.00
   76.22   73.48
 4952.80 4960.00
   76.22   73.48
Abutment Skew #Up #Dn=, 2 , 2
 5040.00 5047.09
   73.40   76.20
 5040.00 5047.09
   73.40   76.20
BR Coef= 1 , 1 , 0 ,1.25, 0 ,,,0.8,0,2,0,
Wspro=,,,, 1 ,,,, 0 ,,,, 0 ,,,,-1 ,-1 ,-1 , 0 , 0 , 0 , 0 , 0
BC Design=,, 0 ,, 0 ,,,,,,
BR U #Sta/Elev= 93
  2786.8    89.5  3335.3   83.87  3495.3   82.23  3515.3   82.03  3565.3   81.52
  3625.3    80.9  3711.1   80.02  3805.3   79.79  3945.3   79.45  3983.2   79.36
  4013.2   79.28  4073.2   79.14  4103.2   79.06  4183.2   78.87  4213.2   78.79
  4231.2   78.75  4311.2   78.47  4334.9   78.56  4391.2   78.79  4404.9   77.78
  4431.2   75.84  4460.4    75.8  4544.9   76.67  4560.4   76.83  4590.4   76.04
  4600.4   76.75  4717.6   76.08  4723.7   76.08  4767.6   76.09  4937.6   74.13
 4952.91   73.69    4953   73.68    4960   73.48  4976.5      73    4980   67.91
    5020   67.91  5023.5      73  5030.4   73.17    5040    73.4 5046.89   73.56
    5047   73.56  5067.6   74.06  5087.6   73.63  5100.4   73.15    5108   72.87
    5198   72.66    5228   74.27    5288   74.58    5298   74.95    5308   73.98
    5318   73.85  5336.4   74.08  5402.4   74.92    5408   74.99  5422.4   74.95
  5542.4   74.62  5582.4   74.51  5663.6   74.28  5713.6   73.47  5756.1   73.86
  5793.6    74.2  5826.1   75.79  5853.6   77.14  5943.6    74.9  5966.1   75.33
  5996.1    75.9  6016.1   76.28  6026.1   76.47  6083.6   77.57  6086.1   77.58
  6126.1   77.68  6166.1   77.78  6253.6      78  6286.1   78.02  6336.1   78.06
  6356.1   78.08  6396.1    78.1  6403.6   78.11  6413.6   78.55  6416.1   78.54
  6453.6    78.4  6466.1   78.53  6503.6   78.91  6513.6   79.54  6516.1   79.56
  6543.6   79.83  6573.6   80.85  6593.6   82.18  6596.1   82.27  6623.9   83.21
  6673.6    84.9  6693.6   86.37  6701.7   86.63
BR U #Mann= 3
 2786.80   0.135  4976.5    0.05  5023.5   0.135
BR U Banks=4976.50,5023.50
BR D #Sta/Elev= 93
  2786.8    89.5  3335.3   83.87  3495.3   82.23  3515.3   82.03  3565.3   81.52
  3625.3    80.9  3711.1   80.02  3805.3   79.79  3945.3   79.45  3983.2   79.36
  4013.2   79.28  4073.2   79.14  4103.2   79.06  4183.2   78.87  4213.2   78.79
  4231.2   78.75  4311.2   78.47  4334.9   78.56  4391.2   78.79  4404.9   77.78
  4431.2   75.84  4460.4    75.8  4544.9   76.67  4560.4   76.83  4590.4   76.04
  4600.4   76.75  4717.6   76.08  4723.7   76.08  4767.6   76.09  4937.6   74.13
 4952.91   73.69    4953   73.68    4960   73.48  4976.5      73    4980   67.91
    5020   67.91  5023.5      73  5030.4   73.17    5040    73.4 5046.89   73.56
    5047   73.56  5067.6   74.06  5087.6   73.63  5100.4   73.15    5108   72.87
    5198   72.66    5228   74.27    5288   74.58    5298   74.95    5308   73.98
    5318   73.85  5336.4   74.08  5402.4   74.92    5408   74.99  5422.4   74.95
  5542.4   74.62  5582.4   74.51  5663.6   74.28  5713.6   73.47  5756.1   73.86
  5793.6    74.2  5826.1   75.79  5853.6   77.14  5943.6    74.9  5966.1   75.33
  5996.1    75.9  6016.1   76.28  6026.1   76.47  6083.6   77.57  6086.1   77.58
  6126.1   77.68  6166.1   77.78  6253.6      78  6286.1   78.02  6336.1   78.06
  6356.1   78.08  6396.1    78.1  6403.6   78.11  6413.6   78.55  6416.1   78.54
  6453.6    78.4  6466.1   78.53  6503.6   78.91  6513.6   79.54  6516.1   79.56
  6543.6   79.83  6573.6   80.85  6593.6   82.18  6596.1   82.27  6623.9   83.21
  6673.6    84.9  6693.6   86.37  6701.7   86.63
BR D #Mann= 3
 2786.80   0.135  4976.5    0.05  5023.5   0.135
BR D Banks=4976.50,5023.50

Type RM Length L Ch R = 1 ,149160.8,644.2,644.2,644.2
BEGIN DESCRIPTION:
Downstream Section of Bridge/Culvert/Weir
END DESCRIPTION:
#Sta/Elev= 30
  2786.8    89.5  3711.1   80.02  4391.2   78.79  4431.2   75.84  4560.4   76.83
  4590.4   76.04  4600.4   76.75  4767.6   76.09  4937.6   74.13  4976.5      73
    4980   67.91    5020   67.91  5023.5      73  5067.6   74.06    5108   72.87
    5198   72.66    5228   74.27    5298   74.95    5318   73.85    5408   74.99
  5663.6   74.28  5713.6   73.47  5793.6    74.2  5853.6   77.14  5943.6    74.9
  6083.6   77.57  6453.6    78.4  6543.6   79.83  6673.6    84.9  6701.7   86.63
#Mann= 3 , 1 , 0
 2786.80   0.135       0  4976.5    0.05       0  5023.5   0.135       0
#XS Ineff= 2 , 0
       0 4969.83   78.01 5030.17       0   76.83
Bank Sta=4976.50,5023.50
Exp/Cntr=0.5,0.3

Type RM Length L Ch R = 1 ,148516.6,499.3,499.3,499.3
BEGIN DESCRIPTION:
Town Creek 295.0
END DESCRIPTION:
#Sta/Elev= 30
  2779.4   96.68  2839.4   91.35  2959.4   85.96  3169.4   82.11  3239.4    83.2
  3469.4   76.88  3549.4   79.53  3629.4   78.52  3709.4   80.29  3989.4   77.65
  4339.4   77.85  4399.4    73.8  4439.4   73.22  4579.4   73.94  4639.4   78.45
  4789.4   78.45  4899.4   72.19 4978.44   70.89 4979.49   67.89 5020.58   67.89
 5021.63   70.89    5060    74.8    5160   73.29    5260   76.83    5570   74.44
    5840   76.03    5970   74.04    6010   78.49    6110   94.33  6225.4   95.85
#Mann= 3 , 1 , 0
 2779.40   0.142       0 4978.44    0.05       0 5021.63   0.142       0
Bank Sta=4978.44,5021.63
Exp/Cntr=0.3,0.1

Type RM Length L Ch R = 1 ,148017.3,499.8,499.8,499.8
BEGIN DESCRIPTION:
Town Creek 294.0
END DESCRIPTION:
#Sta/Elev= 30
  4367.7   81.38  4488.5   79.61  4518.5   80.16  4568.5   77.44  4618.5   77.69
  4718.5   74.63  4758.5   75.67  4788.5   75.65  4798.5   76.48  4818.5   75.93
  4848.5   76.44  4918.5   72.92  4958.5   72.65 4978.37   70.88 4979.42   67.88
 5020.51   67.88 5021.56   70.88    5150   74.42    5170   75.55    5220   73.66
    5640   74.52    5670   73.39    5740   73.94    5810   73.05    5860   73.97
    5920   78.01    6000   87.72    6010   87.62    6090   91.84  6122.2   92.88
#Mann= 3 , 1 , 0
 4367.70   0.142       0 4978.37    0.05       0 5021.56   0.142       0
Bank Sta=4978.37,5021.56
Exp/Cntr=0.3,0.1

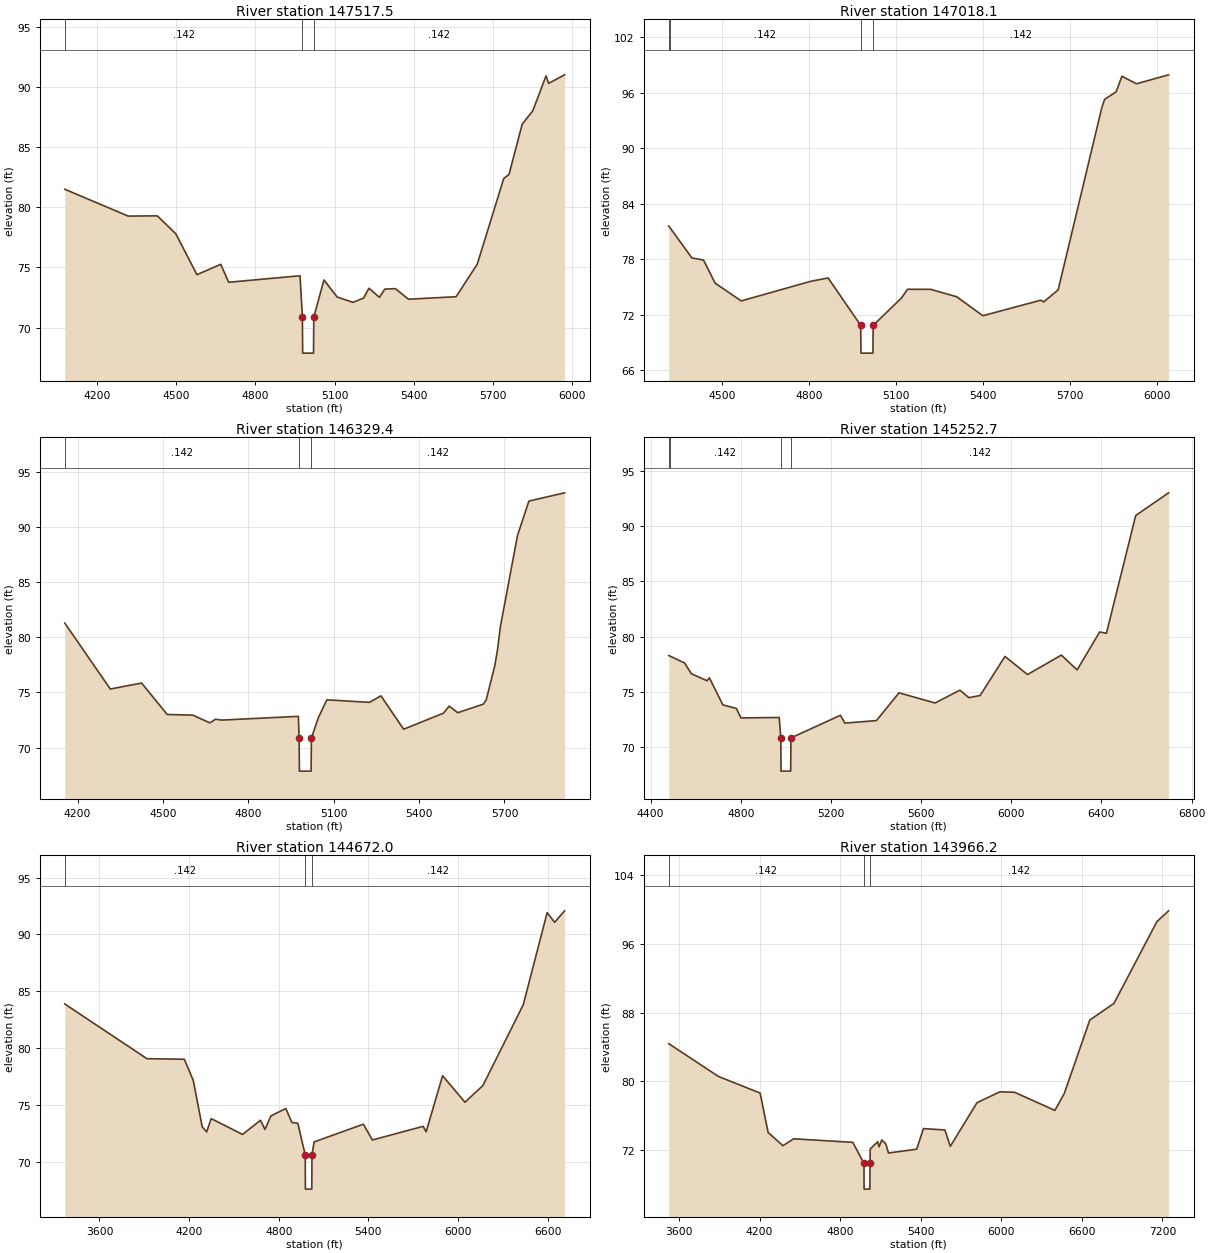
Type RM Length L Ch R = 1 ,147517.5,499.4,499.4,499.4
BEGIN DESCRIPTION:
Town Creek 293.0
END DESCRIPTION:
#Sta/Elev= 30
  4079.5    81.5  4319.5   79.27  4429.5   79.29  4499.5    77.8  4579.5    74.4
  4669.5   75.26  4699.5   73.77  4969.5   74.31 4978.37   70.88 4979.42   67.88
 5020.51   67.88 5021.56   70.88    5060   73.96    5110   72.54    5170    72.1
    5210   72.46    5230   73.27    5270   72.52    5290    73.2    5330   73.24
    5380   72.36    5560   72.57    5640   75.28    5740   82.39    5760   82.73
    5810   86.91    5850   88.02    5900   90.92    5910    90.3  5970.3   91.01
#Mann= 3 , 1 , 0
 4079.50   0.142       0 4978.37    0.05       0 5021.56   0.142       0
Bank Sta=4978.37,5021.56
Exp/Cntr=0.3,0.1

Type RM Length L Ch R = 1 ,147018.1,688.7,688.7,688.7
BEGIN DESCRIPTION:
Town Creek 292.0
END DESCRIPTION:
#Sta/Elev= 26
  4316.2    81.6    4320   81.44  4396.2   78.15  4436.2   77.93  4476.2   75.43
  4566.2   73.51  4806.2   75.63  4866.2   75.99 4978.44   70.87 4979.49   67.87
 5020.58   67.87 5021.63   70.87    5120   73.85    5140   74.77    5220   74.76
    5310   73.96    5400   71.91    5600   73.59    5610    73.4    5660   74.71
    5810   94.33    5820   95.29    5860    96.1    5880   97.79    5930   96.97
  6040.9   97.94
#Mann= 4 , 1 , 0
 4316.20    0.19       0    4320   0.142       0 4978.44    0.05       0
 5021.63   0.142       0
Bank Sta=4978.44,5021.63
Exp/Cntr=0.3,0.1

Type RM Length L Ch R = 1 ,146329.4,1076.7,1076.7,1076.7
BEGIN DESCRIPTION:
Town Creek 290.0
END DESCRIPTION:
#Sta/Elev= 29
  4154.9   81.29  4314.9   75.31  4424.9   75.85  4514.9      73  4604.9   72.94
  4664.9   72.24  4684.9   72.57  4705.8   72.49  4975.8   72.83 4978.37   70.86
 4979.42   67.86 5020.51   67.86 5021.56   70.86  5045.8    72.7  5075.8   74.33
  5225.8    74.1  5265.8   74.69  5345.8   71.66  5485.8   73.12  5505.8   73.76
  5535.8   73.16  5625.8   73.94  5635.8   74.32  5665.8   77.39  5675.8   78.91
  5685.8   80.99  5745.8   89.24  5785.8   92.36  5911.3   93.11
#Mann= 3 , 1 , 0
 4154.90   0.142       0 4978.37    0.05       0 5021.56   0.142       0
Bank Sta=4978.37,5021.56
Exp/Cntr=0.3,0.1

Type RM Length L Ch R = 1 ,145252.7,580.7,580.7,580.7
BEGIN DESCRIPTION:
Town Creek 289.0
END DESCRIPTION:
#Sta/Elev= 30
  4480.6   78.28    4485   78.24  4550.6   77.61  4580.6   76.64  4650.6      76
  4660.6   76.27  4720.6   73.82  4780.6    73.5  4800.6   72.64  4970.6   72.68
 4977.53   70.83 4978.58   67.83 5021.49   67.83 5022.54   70.83  5241.9   72.88
  5261.9   72.17  5401.9    72.4  5501.9   74.91  5661.9   73.99  5771.9   75.15
  5811.9   74.47  5861.9   74.67  5971.9    78.2  6071.9   76.56  6221.9   78.32
  6291.9   76.98  6391.9   80.41  6421.9   80.29  6551.9   90.94  6697.6   92.99
#Mann= 4 , 1 , 0
 4480.60    0.19       0    4485   0.142       0 4977.53    0.05       0
 5022.54   0.142       0
Bank Sta=4977.53,5022.54
Exp/Cntr=0.3,0.1

Type RM Length L Ch R = 1 ,144672.0,705.8,705.8,705.8
BEGIN DESCRIPTION:
Town Creek 288.0
END DESCRIPTION:
#Sta/Elev= 30
  3367.9   83.88  3917.9   79.07  4167.9   79.02  4227.9   77.17  4287.9   73.08
  4317.9   72.63  4347.9    73.8  4557.9   72.41  4677.9   73.65  4707.9   72.85
  4747.9   74.04  4847.9   74.69  4887.9   73.46  4927.9   73.39 4977.53    70.6
 4978.58    67.6 5021.49    67.6 5022.54    70.6    5037   71.75    5367   73.31
    5427   71.92    5767   73.12    5787   72.64    5897   77.57    6047   75.24
    6167   76.71    6437   83.81    6597   91.91    6647   91.06  6713.8   92.07
#Mann= 3 , 1 , 0
 3367.90   0.142       0 4977.53    0.05       0 5022.54   0.142       0
Bank Sta=4977.53,5022.54
Exp/Cntr=0.3,0.1

Type RM Length L Ch R = 1 ,143966.2,452.6,452.6,452.6
BEGIN DESCRIPTION:
Town Creek 287.0
END DESCRIPTION:
#Sta/Elev= 30
  3524.3   84.38  3894.3   80.56  4204.3   78.63  4264.3   74.03  4374.3    72.5
  4454.3    73.3  4894.3   72.89 4977.53   70.44 4978.58   67.44 5021.49   67.44
 5022.54   70.44  5024.3   72.12  5080.2   72.96  5090.2   72.36  5110.2   73.17
  5140.2   72.71  5160.2   71.65  5370.2   72.09  5420.2   74.49  5580.2   74.33
  5620.2   72.42  5818.8    77.5  5988.8   78.77  6098.8   78.72  6398.8   76.61
  6468.8   78.57  6658.8   87.13  6838.8   89.07  7158.8    98.6  7245.4   99.85
#Mann= 3 , 1 , 0
 3524.30   0.142       0 4977.53    0.05       0 5022.54   0.142       0
Bank Sta=4977.53,5022.54
Exp/Cntr=0.3,0.1

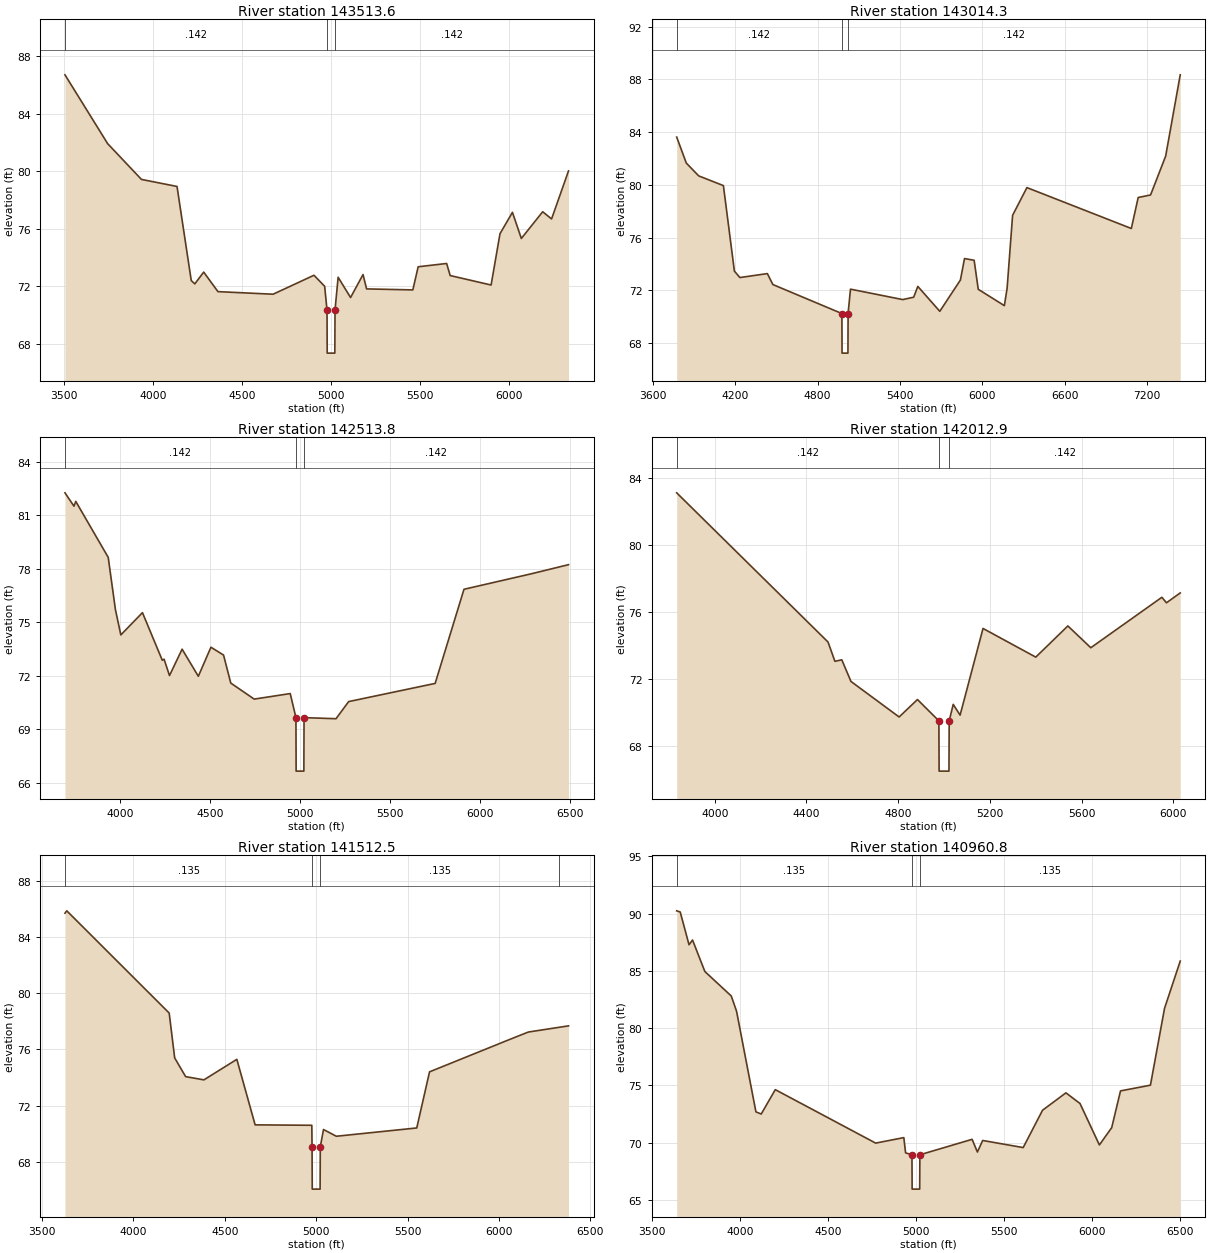
Type RM Length L Ch R = 1 ,143513.6,499.3,499.3,499.3
BEGIN DESCRIPTION:
Town Creek 286.0
END DESCRIPTION:
#Sta/Elev= 30
  3504.3   86.72  3744.3   81.93  3934.3   79.44  4134.3   78.95  4214.3    72.4
  4234.3   72.17  4284.3   72.99  4364.3   71.63  4674.3   71.45  4904.3   72.77
  4964.3      72 4977.53   70.35 4978.58   67.35 5021.49   67.35 5022.54   70.35
    5040   72.63    5110   71.22    5180   72.82    5200   71.82    5460   71.75
    5490   73.36    5650   73.59    5670   72.75    5900   72.09    5950   75.66
    6020   77.15    6070   75.33    6190   77.19    6240   76.69  6335.2   80.03
#Mann= 3 , 1 , 0
 3504.30   0.142       0 4977.53    0.05       0 5022.54   0.142       0
Bank Sta=4977.53,5022.54
Exp/Cntr=0.3,0.1

Type RM Length L Ch R = 1 ,143014.3,500.5,500.5,500.5
BEGIN DESCRIPTION:
Town Creek 285.0
END DESCRIPTION:
#Sta/Elev= 30
  3774.9   83.62  3844.9   81.65  3934.9   80.68  4114.9   79.94  4194.9   73.46
  4234.9   72.97  4434.9   73.27  4474.9   72.44 4977.46   70.24 4978.51   67.24
 5021.42   67.24 5022.47   70.24    5040   72.09    5420    71.3    5500   71.48
    5530    72.3    5690   70.41    5840   72.78    5870   74.41    5940   74.28
    5970   72.08    6160   70.84    6180   72.15    6220   77.69  6324.2   79.79
  7084.2   76.69  7134.2   79.04  7224.2   79.23  7334.2   82.18  7440.2   88.34
#Mann= 3 , 1 , 0
 3774.90   0.142       0 4977.46    0.05       0 5022.47   0.142       0
Bank Sta=4977.46,5022.47
Exp/Cntr=0.3,0.1

Type RM Length L Ch R = 1 ,142513.8,500.9,500.9,500.9
BEGIN DESCRIPTION:
Town Creek 284.0
END DESCRIPTION:
#Sta/Elev= 27
  3695.9   82.27  3745.9   81.52  3755.9   81.79  3935.9   78.65  3975.9   75.72
  4005.9    74.3  4125.9   75.55  4235.9   72.88  4245.9   72.94  4275.9   72.02
  4345.9    73.5  4435.9   71.98  4505.9   73.61  4575.9   73.17  4615.9    71.6
  4745.9    70.7  4945.9   71.01 4977.53   69.66 4978.58   66.66 5021.49   66.66
 5022.54   69.66    5200    69.6    5270   70.56    5750   71.58    5910   76.86
    6280   77.72    6490   78.24
#Mann= 3 , 1 , 0
 3695.90   0.142       0 4977.53    0.05       0 5022.54   0.142       0
Bank Sta=4977.53,5022.54
Exp/Cntr=0.3,0.1

Type RM Length L Ch R = 1 ,142012.9,500.4,500.4,500.4
BEGIN DESCRIPTION:
Town Creek 283.0
END DESCRIPTION:
#Sta/Elev= 20
  3834.1   83.09  4494.1   74.19  4524.1   73.04  4554.1   73.13  4594.1   71.84
  4804.1   69.72  4884.1   70.76 4977.46   69.49 4978.51   66.49 5021.42   66.49
 5022.47   69.49    5040   70.47    5070   69.83    5170      75    5400   73.29
    5540   75.15    5640   73.85    5950   76.86    5970   76.53    6030   77.12
#Mann= 3 , 1 , 0
 3834.10   0.142       0 4977.46    0.05       0 5022.47   0.142       0
Bank Sta=4977.46,5022.47
Exp/Cntr=0.3,0.1

Type RM Length L Ch R = 1 ,141512.5,551.7,551.7,551.7
BEGIN DESCRIPTION:
Town Creek 282.0
END DESCRIPTION:
#Sta/Elev= 21
  3626.1   85.68  3636.1   85.85  4196.1   78.58  4226.1   75.39  4286.1   74.06
  4386.1   73.83  4566.1   75.29  4666.1   70.63  4976.1    70.6 4977.46   69.06
 4978.51   66.06 5021.42   66.06 5022.47   69.06    5040    70.3    5110   69.82
    5550   70.41    5620    74.4    6050   76.66    6160   77.23    6330   77.57
    6380   77.67
#Mann= 4 , 1 , 0
 3626.10   0.135       0 4977.46    0.05       0 5022.47   0.135       0
    6330    0.18       0
Bank Sta=4977.46,5022.47
Exp/Cntr=0.3,0.1

Type RM Length L Ch R = 1 ,140960.8,446.9,446.9,446.9
BEGIN DESCRIPTION:
Town Creek 281.0
END DESCRIPTION:
#Sta/Elev= 30
  3641.4   90.25  3661.4   90.15  3711.4   87.29  3731.4    87.7  3801.4   84.95
  3951.4   82.81  3981.4   81.48  4091.4   72.69  4121.4    72.5  4201.4   74.63
  4771.4   69.96  4931.4   70.44  4941.4   69.11 4977.53   68.94 4978.58   65.94
 5021.49   65.94 5022.54   68.94  5319.2   70.29  5349.2   69.18  5379.2   70.19
  5609.2   69.57  5719.2   72.83    5852   74.35    5932   73.42    6042    69.8
    6112   71.31    6162   74.52    6332   75.02    6412   81.73  6501.2   85.86
#Mann= 3 , 1 , 0
 3641.40   0.135       0 4977.53    0.05       0 5022.54   0.135       0
Bank Sta=4977.53,5022.54
Exp/Cntr=0.3,0.1