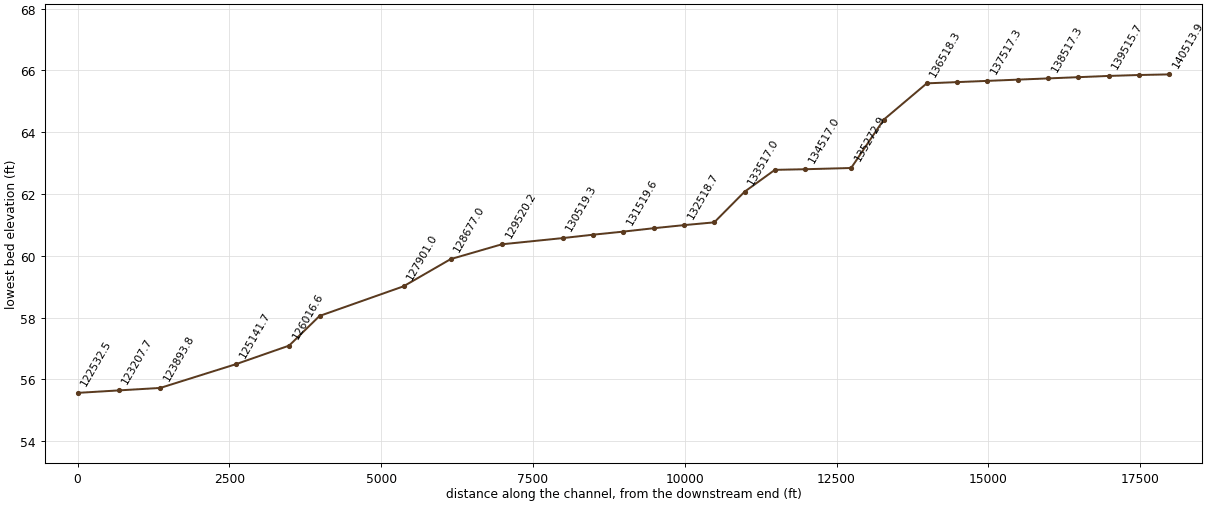
HEC-RAS study Town_Creek_FINAL.prj: Town Creek

--- Town_Creek_FINAL.g01 (geometry) --- (continued)

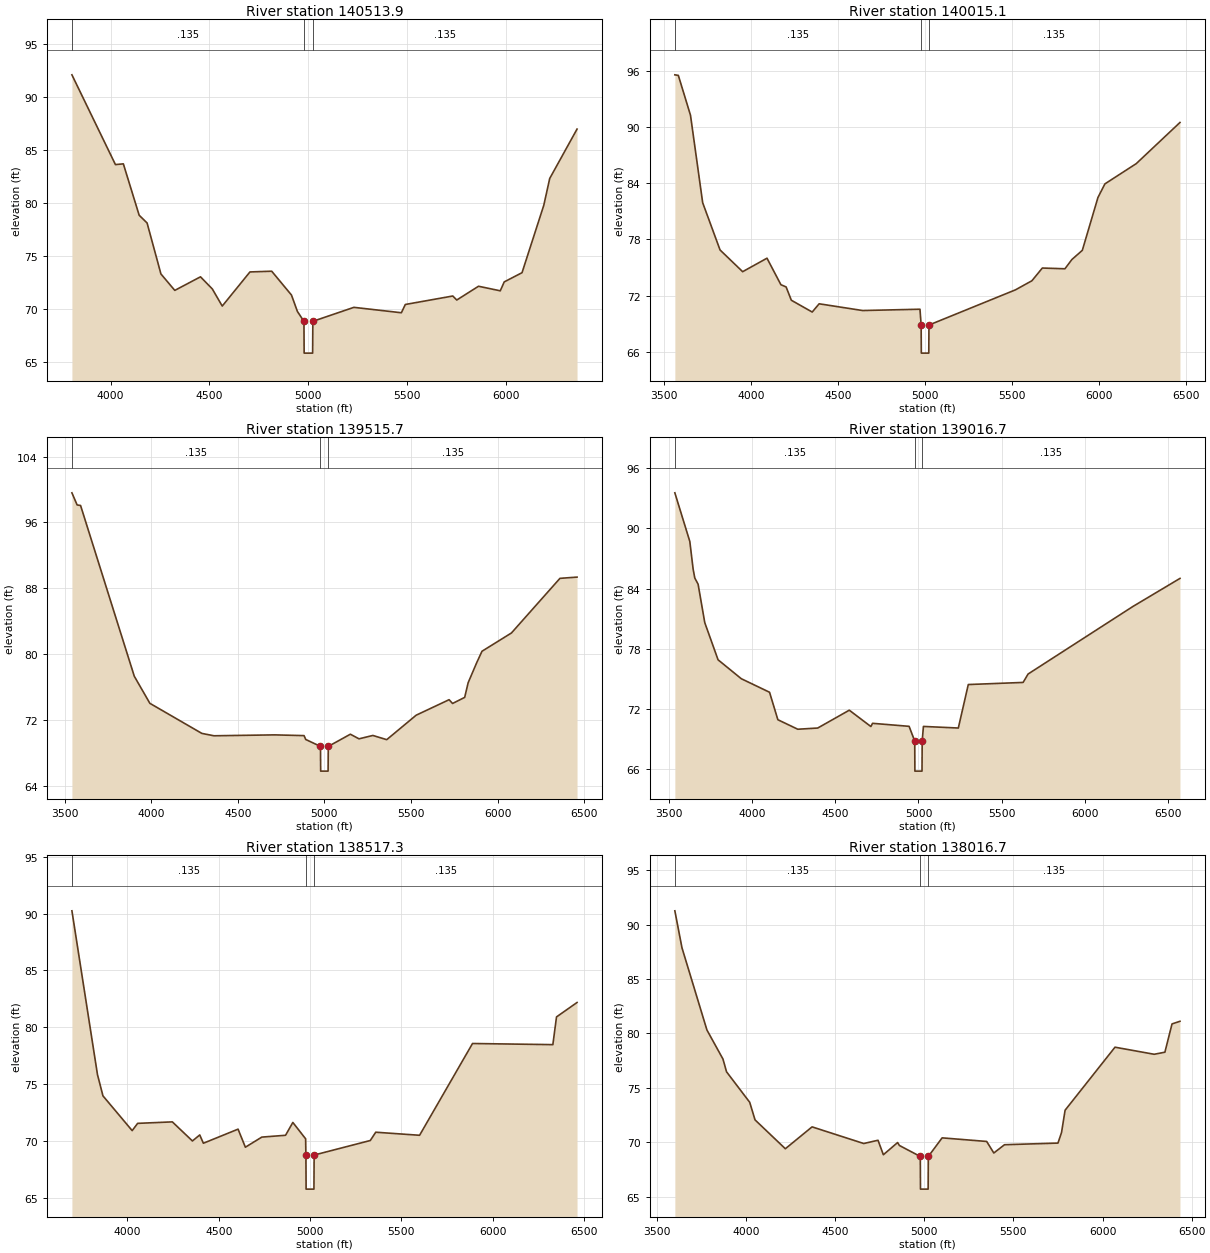
Type RM Length L Ch R = 1 ,140513.9,498.8,498.8,498.8
BEGIN DESCRIPTION:
Town Creek 280.0
END DESCRIPTION:
#Sta/Elev= 30
  3804.5   92.13  4024.5   83.66  4064.5   83.73  4144.5   78.88  4184.5   78.15
  4254.5   73.34  4324.5   71.79  4454.5   73.07  4514.5   71.92  4564.5   70.31
  4704.5   73.53  4814.5    73.6  4914.5   71.35  4944.5    69.8 4977.46   68.87
 4978.51   65.87 5021.42   65.87 5022.47   68.87    5230   70.19    5470   69.68
    5490   70.46    5730   71.26    5750   70.88    5860   72.18    5970   71.75
    5990   72.59    6080   73.46    6190   79.82    6220   82.35  6358.1   87.01
#Mann= 3 , 1 , 0
 3804.50   0.135       0 4977.46    0.05       0 5022.47   0.135       0
Bank Sta=4977.46,5022.47
Exp/Cntr=0.3,0.1

Type RM Length L Ch R = 1 ,140015.1,499.4,499.4,499.4
BEGIN DESCRIPTION:
Town Creek 279.0
END DESCRIPTION:
#Sta/Elev= 28
  3560.8   95.58  3580.8   95.52  3650.8   91.26  3720.8   81.92  3820.8   76.87
  3950.8   74.55  4090.8   75.99  4170.8   73.16  4200.8   72.92  4230.8    71.5
  4350.8   70.24  4390.8   71.12  4640.8    70.4  4970.8   70.54 4977.46   68.85
 4978.51   65.85 5021.42   65.85 5022.47   68.85    5520   72.61  5614.6   73.58
  5674.6   74.94  5804.6   74.86  5844.6   75.85  5904.6   76.83  5994.6   82.48
  6034.6   83.93  6214.6   86.09  6466.3   90.49
#Mann= 3 , 1 , 0
 3560.80   0.135       0 4977.46    0.05       0 5022.47   0.135       0
Bank Sta=4977.46,5022.47
Exp/Cntr=0.3,0.1

Type RM Length L Ch R = 1 ,139515.7,499,499,499
BEGIN DESCRIPTION:
Town Creek 278.0
END DESCRIPTION:
#Sta/Elev= 28
  3542.6    99.6  3572.6   98.13  3592.6   98.06  3902.6   77.34  3992.6   74.05
  4292.6    70.4  4362.6   70.11  4712.6   70.22  4882.6   70.13  4892.6   69.66
 4977.53   68.82 4978.58   65.82 5021.49   65.82 5022.54   68.82    5150    70.3
    5200   69.74    5280   70.15    5360   69.64    5530   72.61    5720   74.49
    5740   74.03    5810   74.77    5830   76.55    5880   79.01    5910   80.37
    6080   82.59    6360   89.22  6458.6   89.37
#Mann= 3 , 1 , 0
 3542.60   0.135       0 4977.53    0.05       0 5022.54   0.135       0
Bank Sta=4977.53,5022.54
Exp/Cntr=0.3,0.1

Type RM Length L Ch R = 1 ,139016.7,499.4,499.4,499.4
BEGIN DESCRIPTION:
Town Creek 277.0
END DESCRIPTION:
#Sta/Elev= 27
  3533.7   93.55  3623.7    88.7  3643.7   85.94  3653.7   85.05  3673.7   84.43
  3713.7    80.6  3793.7   76.89  3933.7      75  4103.7   73.65  4153.7   70.91
  4273.7   69.96  4393.7   70.08  4583.7   71.86  4713.7   70.23  4723.7   70.55
  4943.7   70.25 4977.53   68.78 4978.58   65.78 5021.42   65.78 5022.47   68.78
    5030   70.24    5240   70.08    5300   74.42    5630   74.63    5660   75.47
    6290    82.2  6574.2   85.01
#Mann= 3 , 1 , 0
 3533.70   0.135       0 4977.53    0.05       0 5022.47   0.135       0
Bank Sta=4977.53,5022.47
Exp/Cntr=0.3,0.1

Type RM Length L Ch R = 1 ,138517.3,500.6,500.6,500.6
BEGIN DESCRIPTION:
Town Creek 276.0
END DESCRIPTION:
#Sta/Elev= 26
  3695.9   90.24  3835.9   75.82  3865.9   73.95  4025.9   70.89  4055.9   71.53
  4245.9   71.66  4355.9   69.98  4395.9   70.51  4415.9   69.78  4605.9   71.02
  4645.9   69.43  4735.9   70.32  4865.9   70.48  4905.9   71.61  4975.9   70.17
 4977.46   68.74 4978.51   65.74 5021.42   65.74 5022.47   68.74    5330   70.02
    5360   70.75    5600   70.48    5890   78.56    6330   78.46    6350    80.9
  6462.4   82.17
#Mann= 3 , 1 , 0
 3695.90   0.135       0 4977.46    0.05       0 5022.47   0.135       0
Bank Sta=4977.46,5022.47
Exp/Cntr=0.3,0.1

Type RM Length L Ch R = 1 ,138016.7,499.4,499.4,499.4
BEGIN DESCRIPTION:
Town Creek 275.0
END DESCRIPTION:
#Sta/Elev= 30
  3600.2   91.27  3640.2   87.87  3780.2   80.32  3870.2   77.65  3890.2   76.48
  4020.2   73.68  4050.2   72.06  4220.2   69.41  4370.2   71.42  4660.2   69.89
  4740.2   70.19  4770.2   68.86  4850.2   69.98  4860.2   69.71 4977.46    68.7
 4978.51    65.7 5021.42    65.7 5022.47    68.7    5100   70.41    5350   70.08
    5390   69.02    5450   69.78    5750   69.93    5770    70.9    5790   72.95
    6070   78.74    6290   78.09    6350   78.28    6390   80.88  6434.6   81.12
#Mann= 3 , 1 , 0
 3600.20   0.135       0 4977.46    0.05       0 5022.47   0.135       0
Bank Sta=4977.46,5022.47
Exp/Cntr=0.3,0.1

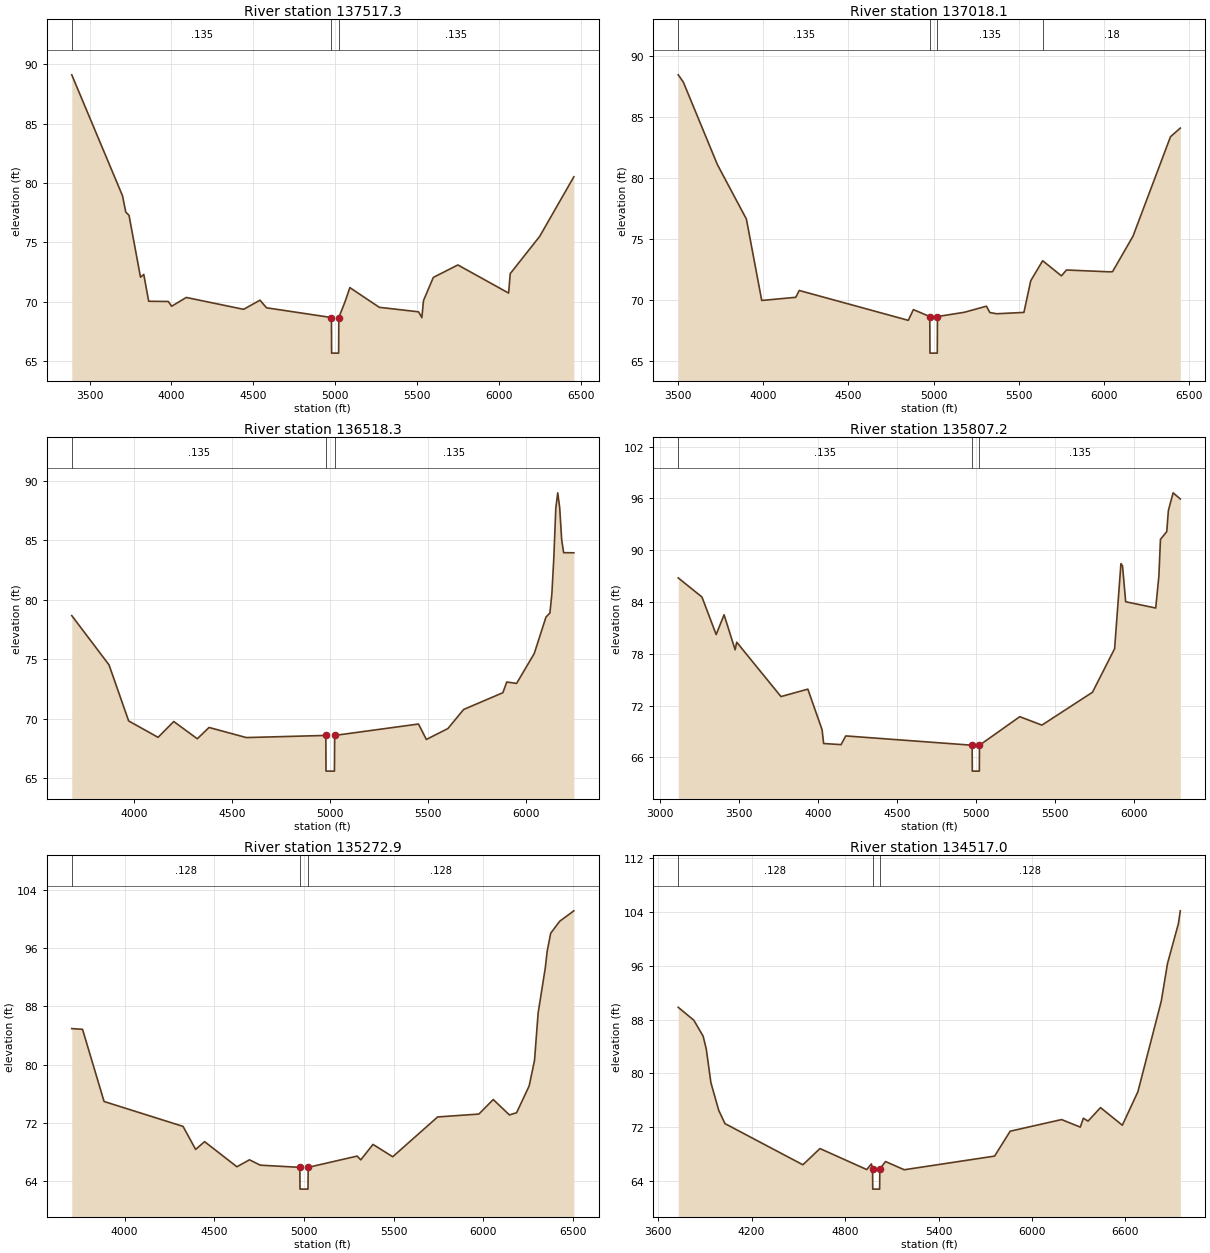
Type RM Length L Ch R = 1 ,137517.3,499.2,499.2,499.2
BEGIN DESCRIPTION:
Town Creek 274.0
END DESCRIPTION:
#Sta/Elev= 29
  3390.8   89.11  3700.8   78.92  3720.8   77.55  3740.8   77.26  3810.8   72.06
  3830.8   72.29  3860.8   70.03  3980.8   70.01  4000.8   69.61  4090.8   70.35
  4440.8   69.35  4540.8   70.12  4580.8   69.48 4977.46   68.66 4978.51   65.66
 5021.42   65.66 5022.47   68.66    5060   69.97    5090   71.18    5270   69.52
    5510   69.14    5530   68.65    5540   70.09    5600   72.04    5750   73.09
    6060   70.72    6070   72.36    6250    75.5  6458.6   80.52
#Mann= 3 , 1 , 0
 3390.80   0.135       0 4977.46    0.05       0 5022.47   0.135       0
Bank Sta=4977.46,5022.47
Exp/Cntr=0.3,0.1

Type RM Length L Ch R = 1 ,137018.1,499.8,499.8,499.8
BEGIN DESCRIPTION:
Town Creek 273.0
END DESCRIPTION:
#Sta/Elev= 27
  3501.3   88.45  3531.3   87.85  3731.3   81.08  3901.3   76.62  3991.3   69.94
  4191.3    70.2  4211.3   70.76  4851.3   68.31  4881.3   69.19 4977.53   68.62
 4978.58   65.62 5021.49   65.62 5022.54   68.62    5180   68.97    5310   69.47
    5330   68.95    5370   68.85    5530   68.96    5570   71.56    5640    73.2
    5750   71.96    5780   72.44    6030   72.29    6050    72.3    6170   75.21
    6390   83.37  6447.7   84.08
#Mann= 4 , 1 , 0
 3501.30   0.135       0 4977.53    0.05       0 5022.54   0.135       0
    5640    0.18       0
Bank Sta=4977.53,5022.54
Exp/Cntr=0.3,0.1

Type RM Length L Ch R = 1 ,136518.3,711.1,711.1,711.1
BEGIN DESCRIPTION:
Town Creek 272.0
END DESCRIPTION:
#Sta/Elev= 30
  3682.2   78.65  3872.2   74.51  3972.2    69.8  4122.2   68.42  4202.2   69.75
  4322.2    68.3  4382.2   69.25  4572.2    68.4 4977.46   68.58 4978.51   65.58
 5021.42   65.58 5022.47   68.58    5450   69.54    5490   68.24    5600   69.16
    5680   70.76    5880   72.17    5900   73.07    5950   72.95    6040   75.46
    6100   78.53    6120   78.87    6130   80.49    6140   83.53    6150   87.68
    6160   88.97    6170   87.69    6180   85.02    6190   83.94    6242   83.93
#Mann= 3 , 1 , 0
 3682.20   0.135       0 4977.46    0.05       0 5022.47   0.135       0
Bank Sta=4977.46,5022.47
Exp/Cntr=0.3,0.1

Type RM Length L Ch R = 1 ,135807.2,534.3,534.3,534.3
BEGIN DESCRIPTION:
Town Creek 271.0
END DESCRIPTION:
#Sta/Elev= 30
  3117.3   86.79  3267.3   84.58  3357.3   80.23  3407.3   82.52  3477.3   78.46
  3487.3   79.34  3767.3   73.04  3937.3    73.9  4027.3    69.2  4037.3    67.6
  4147.3   67.47  4177.3   68.48 4976.76    67.4 4977.81    64.4 5022.12    64.4
 5023.17    67.4  5278.1   70.71  5418.1   69.73  5738.1   73.54  5878.1   78.59
  5918.1   88.45  5928.1   88.18  5948.1   84.03  6138.1    83.3  6158.1      87
  6168.1   91.26  6208.1   92.16  6218.1   94.59  6248.1   96.65  6293.7   95.94
#Mann= 3 , 1 , 0
 3117.30   0.135       0 4976.76    0.05       0 5023.17   0.135       0
Bank Sta=4976.76,5023.17
Exp/Cntr=0.3,0.1

Type RM Length L Ch R = 1 ,135272.9,755.9,755.9,755.9
BEGIN DESCRIPTION:
Town Creek 269.0
END DESCRIPTION:
#Sta/Elev= 30
  3706.2   84.95  3766.2   84.85  3886.2   74.91  4326.2   71.48  4396.2   68.31
  4446.2   69.38  4626.2   65.92  4696.2   66.88  4756.2   66.14 4976.83   65.84
 4977.88   62.84 5022.19   62.84 5023.24   65.84  5296.2   67.39  5316.2   66.87
  5384.4      69  5494.4    67.3  5744.4   72.78  5974.4   73.18  6054.4   75.18
  6144.4   73.06  6184.4   73.36  6254.4   77.05  6284.4   80.58  6304.4   87.08
  6344.4   93.33  6354.4   95.53  6374.4   98.08  6424.4   99.73  6503.4  101.17
#Mann= 3 , 1 , 0
 3706.20   0.128       0 4976.83    0.05       0 5023.24   0.128       0
Bank Sta=4976.83,5023.24
Exp/Cntr=0.3,0.1

Type RM Length L Ch R = 1 ,134517.0,500,500,500
BEGIN DESCRIPTION:
Town Creek 268.0
END DESCRIPTION:
#Sta/Elev= 30
  3729.2   89.83  3829.2   87.91  3889.2   85.53  3909.2   83.62  3939.2    78.6
  3989.2   74.51  4029.2   72.54  4529.2   66.42  4639.2   68.83  4939.2   65.71
  4969.2   66.55 4976.76    65.8 4977.81    62.8 5022.12    62.8 5023.17    65.8
    5060    66.9    5180   65.68    5760   67.71    5860   71.41    6190   73.14
    6310   72.02    6330   73.34    6360   72.91    6440   74.92    6580    72.3
    6680   77.28    6830   90.74    6870   96.34    6940  102.27  6952.2  104.17
#Mann= 3 , 1 , 0
 3729.20   0.128       0 4976.76    0.05       0 5023.17   0.128       0
Bank Sta=4976.76,5023.17
Exp/Cntr=0.3,0.1

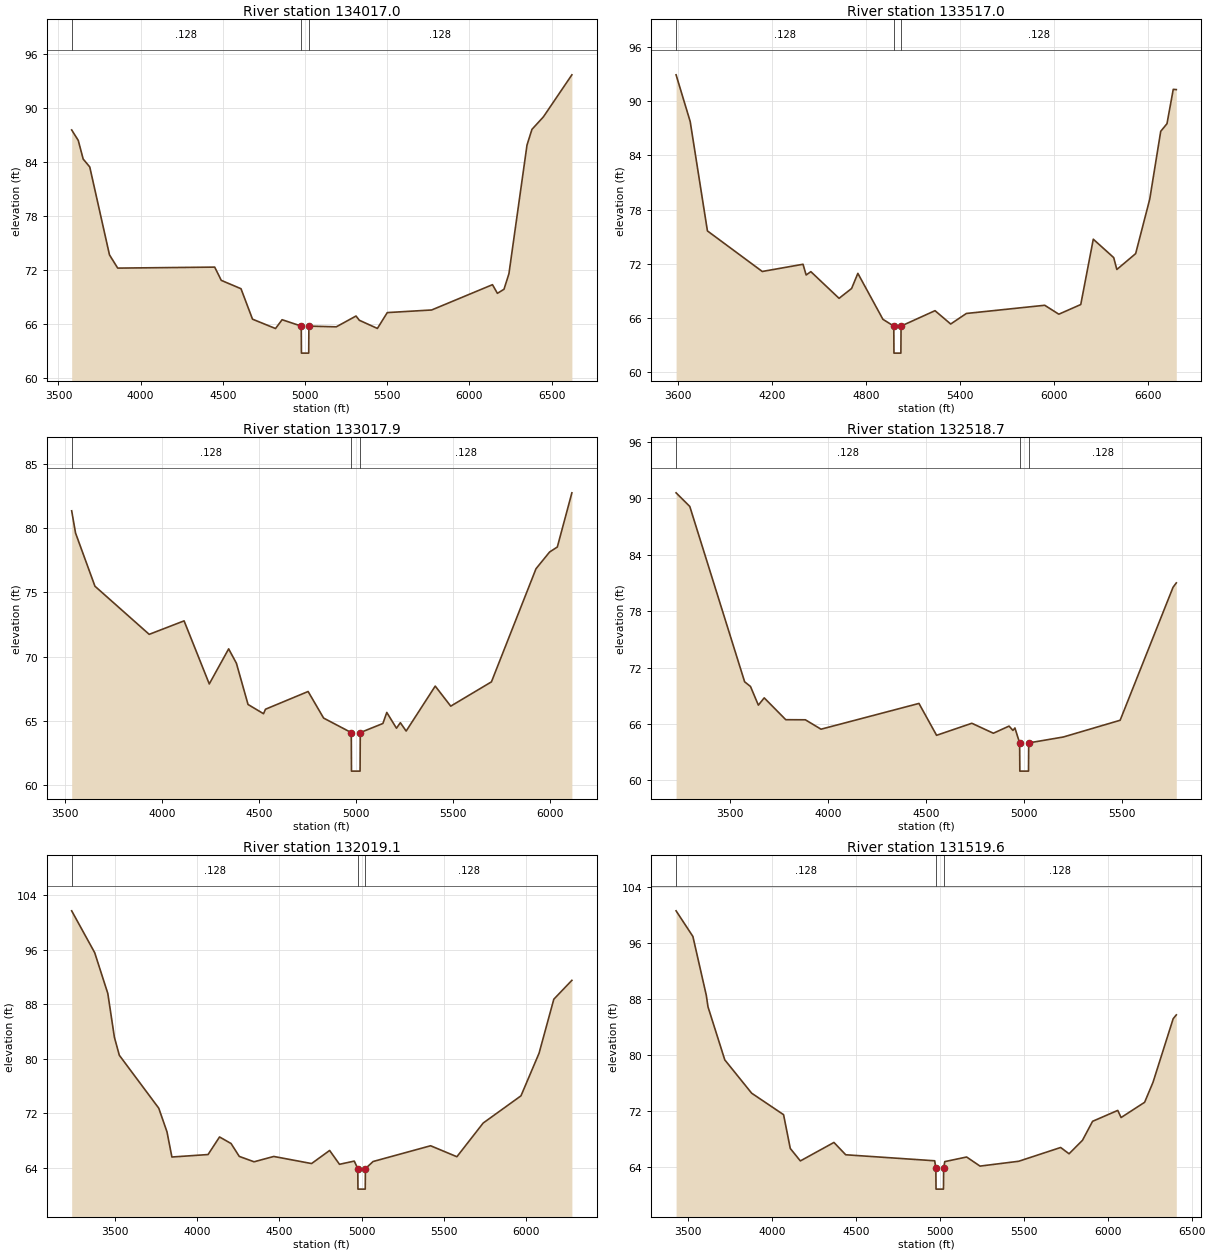
Type RM Length L Ch R = 1 ,134017.0,500,500,500
BEGIN DESCRIPTION:
Town Creek 267.0
END DESCRIPTION:
#Sta/Elev= 30
  3580.3   87.56  3620.3    86.4  3650.3   84.33  3690.3   83.45  3810.3   73.69
  3860.3   72.22  4450.3   72.33  4490.3   70.86  4610.3   69.93  4680.3   66.55
  4820.3   65.51  4860.3   66.49 4976.83   65.78 4977.88   62.78 5022.19   62.78
 5023.24   65.78    5190    65.7    5310    66.9    5330   66.43    5440   65.52
    5500   67.28    5770   67.57    6140   70.38    6170   69.42    6210   69.87
    6240   71.59    6350   85.88    6380   87.62    6450   89.02    6623   93.68
#Mann= 3 , 1 , 0
 3580.30   0.128       0 4976.83    0.05       0 5023.24   0.128       0
Bank Sta=4976.83,5023.24
Exp/Cntr=0.3,0.1

Type RM Length L Ch R = 1 ,133517.0,499.1,499.1,499.1
BEGIN DESCRIPTION:
Town Creek 266.0
END DESCRIPTION:
#Sta/Elev= 30
  3587.6   92.95  3677.6   87.77  3787.6   75.63  4137.6   71.13  4397.6   71.93
  4417.6   70.74  4447.6   71.11  4627.6   68.15  4707.6   69.24  4747.6   70.92
  4907.6   65.82 4976.83   65.07 4977.88   62.07 5022.19   62.07 5023.24   65.07
    5240   66.78    5340    65.3    5440   66.47    5940   67.38    6030   66.39
    6170   67.46    6250   74.71  6380.3   72.67  6400.3   71.35  6520.3   73.11
  6610.3   79.16  6680.3   86.68  6720.3   87.53  6760.3   91.34  6779.7   91.31
#Mann= 3 , 1 , 0
 3587.60   0.128       0 4976.83    0.05       0 5023.24   0.128       0
Bank Sta=4976.83,5023.24
Exp/Cntr=0.3,0.1

Type RM Length L Ch R = 1 ,133017.9,499.2,499.2,499.2
BEGIN DESCRIPTION:
Town Creek 265.0
END DESCRIPTION:
#Sta/Elev= 29
  3534.1   81.35  3554.1   79.62  3654.1   75.48  3934.1   71.73  4114.1   72.78
  4244.1   67.87  4344.1    70.6  4384.1   69.48  4444.1   66.27  4524.1   65.55
  4534.1    65.9  4754.1   67.28  4834.1   65.21 4976.83   64.08 4977.88   61.08
 5022.19   61.08 5023.24   64.08    5140   64.79    5160   65.65    5210   64.42
    5230   64.85    5260    64.2    5410    67.7    5490   66.14    5700   68.03
    5930   76.84    6000   78.14    6040   78.53  6115.1   82.75
#Mann= 3 , 1 , 0
 3534.10   0.128       0 4976.83    0.05       0 5023.24   0.128       0
Bank Sta=4976.83,5023.24
Exp/Cntr=0.3,0.1

Type RM Length L Ch R = 1 ,132518.7,499.6,499.6,499.6
BEGIN DESCRIPTION:
Town Creek 264.0
END DESCRIPTION:
#Sta/Elev= 24
  3222.8   90.59  3292.8   89.14  3572.8   70.49  3602.8   69.99  3642.8   68.01
  3672.8   68.78  3782.8   66.46  3882.8   66.45  3962.8   65.45  4462.8   68.19
  4552.8    64.8  4732.8   66.08  4842.8   65.02  4922.8   65.78  4942.8   65.32
  4952.8   65.58 4976.83   63.99 4977.88   60.99 5022.12   60.99 5023.17   63.99
    5200   64.62    5490    66.4    5760   80.54  5776.7   81.01
#Mann= 3 , 1 , 0
 3222.80   0.128       0 4976.83    0.05       0 5023.17   0.128       0
Bank Sta=4976.83,5023.17
Exp/Cntr=0.3,0.1

Type RM Length L Ch R = 1 ,132019.1,499.5,499.5,499.5
BEGIN DESCRIPTION:
Town Creek 263.0
END DESCRIPTION:
#Sta/Elev= 30
  3235.5   101.7  3375.5   95.57  3455.5   89.58  3495.5   83.16  3525.5   80.52
  3765.5   72.76  3815.5    69.3  3845.5    65.6  4065.5   65.96  4135.5   68.54
  4205.5   67.58  4255.5   65.69  4345.5    64.9  4465.5   65.68  4695.5   64.64
  4805.5   66.56  4865.5   64.53  4955.5      65 4976.83   63.89 4977.88   60.89
 5022.19   60.89 5023.24   63.89    5070   64.94    5420   67.25    5580   65.64
    5740   70.58    5970   74.57    6080   80.81    6170   88.74  6279.9   91.51
#Mann= 3 , 1 , 0
 3235.50   0.128       0 4976.83    0.05       0 5023.24   0.128       0
Bank Sta=4976.83,5023.24
Exp/Cntr=0.3,0.1

Type RM Length L Ch R = 1 ,131519.6,500.8,500.8,500.8
BEGIN DESCRIPTION:
Town Creek 262.0
END DESCRIPTION:
#Sta/Elev= 30
    3430  100.55    3530   96.89    3610   88.47    3620   86.83    3720   79.25
    3880   74.49    4070   71.42    4110   66.59    4170   64.81    4370   67.45
    4440   65.69    4970   64.83 4976.83   63.78 4977.88   60.78 5022.19   60.78
 5023.24   63.78    5030   64.71    5160   65.37    5240   64.07    5470   64.76
    5720   66.73    5770   65.83    5850   67.76    5910   70.47    6060   72.03
    6080   71.01    6220   73.19    6270   76.05    6390   85.13  6408.6   85.68
#Mann= 3 , 1 , 0
 3430.00   0.128       0 4976.83    0.05       0 5023.24   0.128       0
Bank Sta=4976.83,5023.24
Exp/Cntr=0.3,0.1

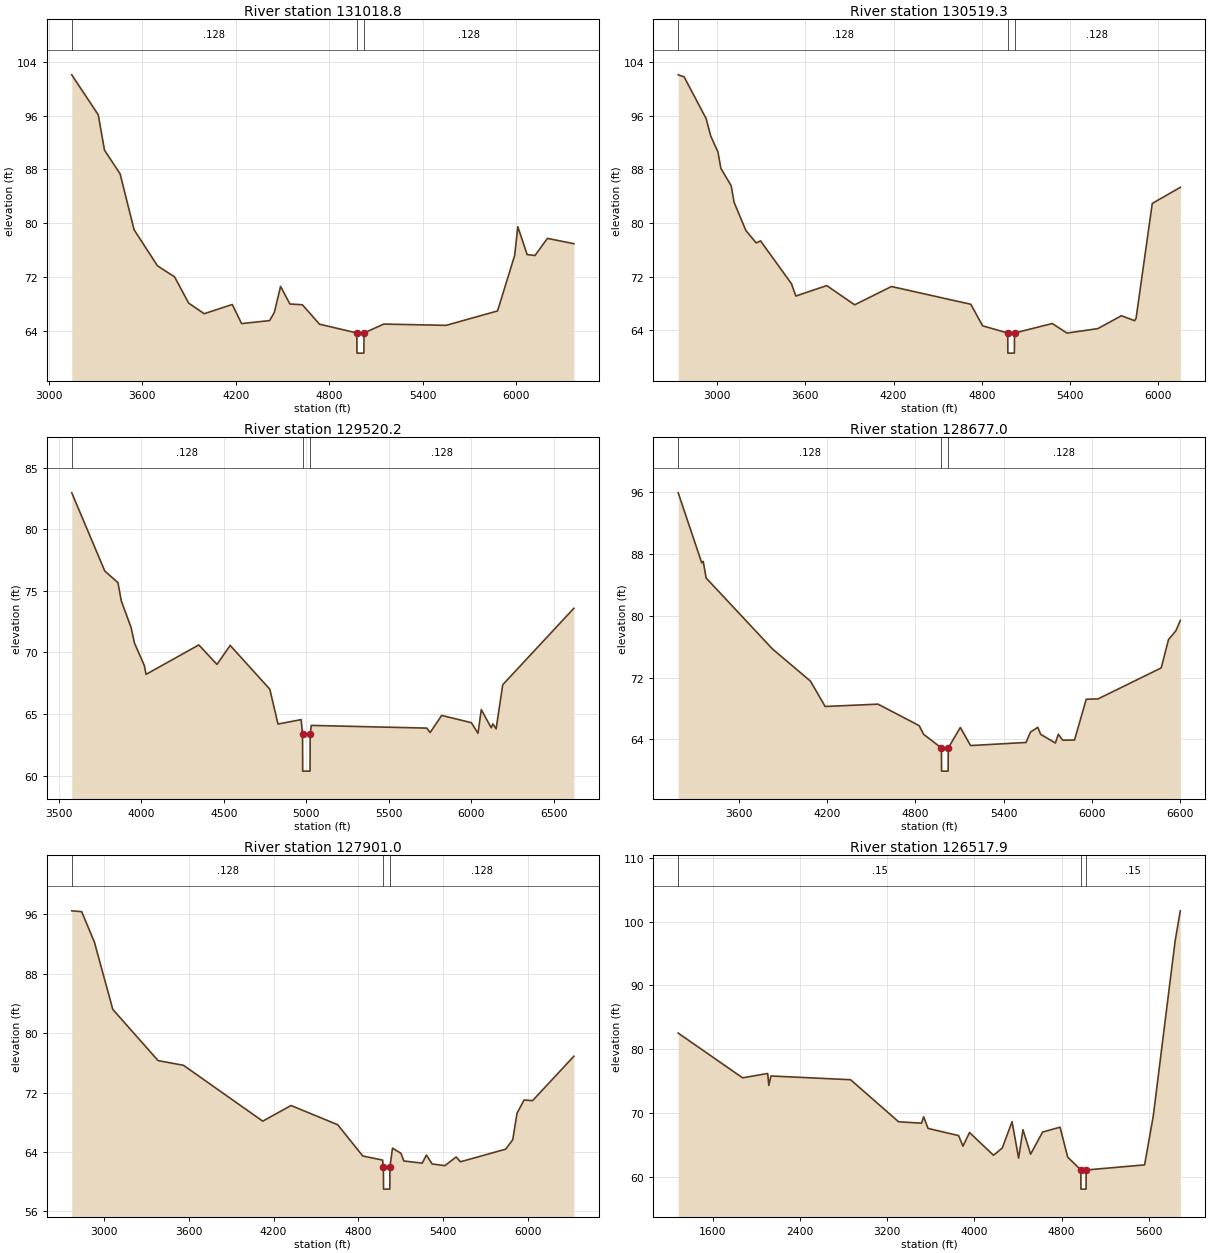
Type RM Length L Ch R = 1 ,131018.8,499.5,499.5,499.5
BEGIN DESCRIPTION:
Town Creek 261.0
END DESCRIPTION:
#Sta/Elev= 30
  3147.5  102.05  3317.5   96.11  3357.5   90.85  3457.5   87.34  3547.5   79.02
  3697.5   73.66  3807.5   72.01  3897.5   68.12  3997.5   66.54  4177.5   67.91
  4237.5   65.07  4417.5   65.52  4447.5   66.74  4487.5    70.6  4547.5   67.98
  4627.5   67.87  4737.5   64.98 4976.76   63.68 4977.81   60.68 5022.12   60.68
 5023.17   63.68    5150      65    5550   64.81    5880   66.95    5990   75.22
    6010   79.47    6070   75.33    6120   75.19    6200   77.74  6369.6   76.95
#Mann= 3 , 1 , 0
 3147.50   0.128       0 4976.76    0.05       0 5023.17   0.128       0
Bank Sta=4976.76,5023.17
Exp/Cntr=0.3,0.1

Type RM Length L Ch R = 1 ,130519.3,999.1,999.1,999.1
BEGIN DESCRIPTION:
Town Creek 260.0
END DESCRIPTION:
#Sta/Elev= 30
  2735.9   102.1  2775.9   101.8  2925.9   95.56  2955.9   93.03  3005.9   90.59
  3025.9   88.15  3095.9   85.55  3115.9   83.08  3195.9   78.87  3265.9   77.02
  3295.9   77.32  3505.9   70.93  3535.9   69.09  3745.9   70.65  3935.9   67.78
  4185.9   70.51  4725.9   67.86  4805.9   64.65 4976.76   63.57 4977.81   60.57
 5022.12   60.57 5023.17   63.57    5280   64.99    5380   63.56    5590   64.23
    5750   66.15    5840   65.41    5850   65.78    5960   82.91  6150.7   85.31
#Mann= 3 , 1 , 0
 2735.90   0.128       0 4976.76    0.05       0 5023.17   0.128       0
Bank Sta=4976.76,5023.17
Exp/Cntr=0.3,0.1

Type RM Length L Ch R = 1 ,129520.2,843.2,843.2,843.2
BEGIN DESCRIPTION:
Town Creek 259.0
END DESCRIPTION:
#Sta/Elev= 30
  3578.3   82.95  3778.3   76.61  3858.3   75.66  3878.3   74.19  3938.3      72
  3958.3   70.76  4018.3   68.93  4028.3   68.22  4348.3   70.61  4458.3   69.03
  4538.3   70.57  4778.3   67.02  4828.3   64.19  4968.3   64.55 4976.76   63.37
 4977.81   60.37 5022.12   60.37 5023.17   63.37    5030   64.08    5730   63.86
    5750    63.5    5820   64.89    6000    64.3    6040   63.44    6060   65.36
    6120   63.89    6130    64.2    6150    63.8    6190   67.38  6620.9   73.58
#Mann= 3 , 1 , 0
 3578.30   0.128       0 4976.76    0.05       0 5023.17   0.128       0
Bank Sta=4976.76,5023.17
Exp/Cntr=0.3,0.1

Type RM Length L Ch R = 1 ,128677.0,776,776,776
BEGIN DESCRIPTION:
Town Creek 257.0
END DESCRIPTION:
#Sta/Elev= 30
  3185.6   95.92  3345.6   86.85  3355.6   87.04  3375.6   84.89  3825.6   75.73
  4085.6   71.54  4185.6   68.26  4545.4   68.56  4825.4   65.78  4855.4   64.66
 4976.76   62.89 4977.81   59.89 5022.12   59.89 5023.17   62.89  5105.4   65.54
  5175.4    63.2  5552.4    63.6  5582.4   64.94  5632.4   65.56  5652.4   64.65
  5752.4   63.53  5772.4   64.67  5802.4   63.89  5882.4   63.92  5962.4    69.2
  6042.4   69.24  6472.4   73.25  6522.4   76.93  6572.4   78.06  6602.5   79.39
#Mann= 3 , 1 , 0
 3185.60   0.128       0 4976.76    0.05       0 5023.17   0.128       0
Bank Sta=4976.76,5023.17
Exp/Cntr=0.3,0.1

Type RM Length L Ch R = 1 ,127901.0,1383.1,1383.1,1383.1
BEGIN DESCRIPTION:
Town Creek 255.0
END DESCRIPTION:
#Sta/Elev= 30
  2773.9   96.48  2843.9   96.37  2933.9   92.27  3063.9   83.21  3383.9   76.32
  3563.9   75.68  4123.9   68.16  4323.9   70.27  4653.9   67.68  4831.2   63.47
  4971.2   62.92 4976.76   62.01 4977.81   59.01 5022.12   59.01 5023.17   62.01
  5041.2   64.53  5101.2   63.83  5121.2    62.8  5251.2   62.51  5281.2    63.6
  5321.2    62.4  5411.2   62.17  5491.2   63.34  5521.2   62.69  5841.2   64.39
  5891.2   65.66  5921.2   69.21  5971.2   71.01  6031.2   70.92  6323.1    76.9
#Mann= 3 , 1 , 0
 2773.90   0.128       0 4976.76    0.05       0 5023.17   0.128       0
Bank Sta=4976.76,5023.17
Exp/Cntr=0.3,0.1

Type RM Length L Ch R = 1 ,126517.9,501.3,501.3,501.3
BEGIN DESCRIPTION:
Town Creek 253.0
END DESCRIPTION:
#Sta/Elev= 30
  1285.3   82.51  1875.3    75.5  2105.3   76.18  2115.3   74.31  2135.3   75.79
  2865.3    75.2  3305.3   68.61  3515.3   68.39  3535.3   69.39  3575.3   67.57
  3855.3   66.44  3895.3   64.79  3955.3   66.92  4175.3   63.36  4255.3   64.49
  4345.3   68.62  4405.3   62.92  4445.3   67.37  4515.3   63.53  4625.3      67
  4785.3   67.76  4855.3   63.07 4975.57   61.05 4976.62   58.05 5023.45   58.05
  5024.5   61.05    5560   61.85    5640   69.54    5840   96.96  5887.5  101.68
#Mann= 3 , 1 , 0
 1285.30    0.15       0 4975.57    0.05       0  5024.5    0.15       0
Bank Sta=4975.57,5024.50
Exp/Cntr=0.3,0.1

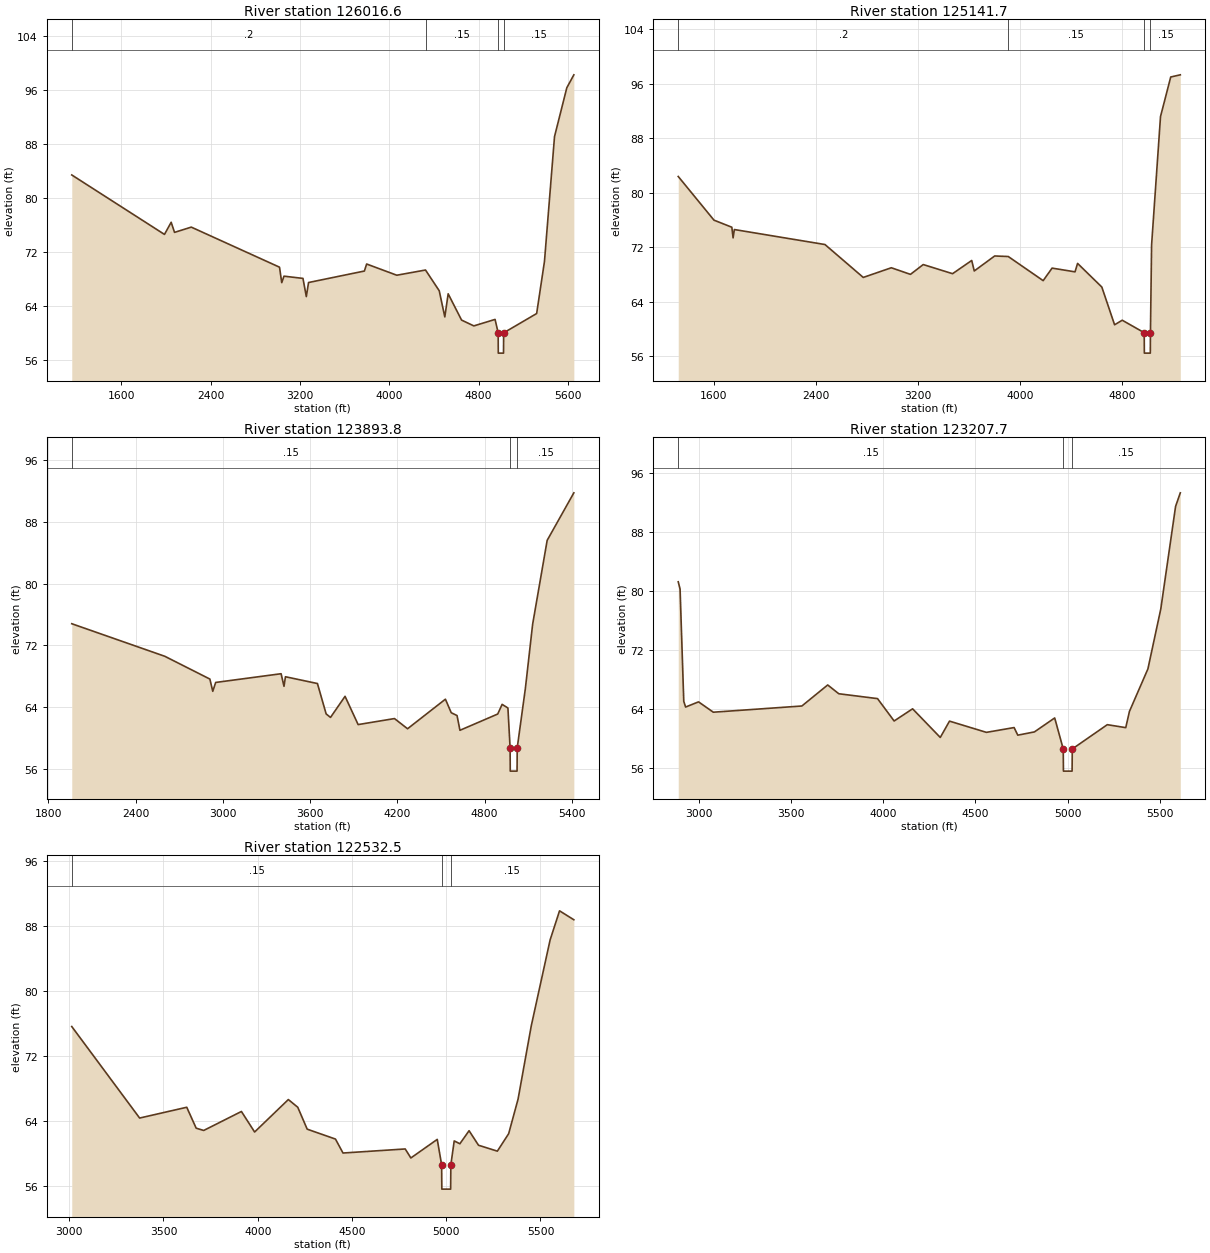
Type RM Length L Ch R = 1 ,126016.6,874.9,874.9,874.9
BEGIN DESCRIPTION:
Town Creek 252.0
END DESCRIPTION:
#Sta/Elev= 30
  1157.8   83.46  1987.8   74.66  2047.8   76.46  2077.8   74.96  2227.8   75.74
  3017.8   69.81  3037.8   67.52  3057.8   68.48  3227.8   68.15  3257.8   65.46
  3277.8   67.54  3777.8   69.24  3797.8   70.28  4067.8   68.62    4325   69.39
  4447.8   66.32  4497.8   62.45  4527.8   65.87  4647.8   61.98  4757.8   61.12
  4947.8   62.08  4975.5   60.09 4976.55   57.09 5023.45   57.09  5024.5   60.09
    5320   62.95    5390   70.66    5480   89.14    5590   96.36    5653   98.28
#Mann= 4 , 1 , 0
 1157.80     0.2       0    4325    0.15       0  4975.5    0.05       0
  5024.5    0.15       0
Bank Sta=4975.50,5024.50
Exp/Cntr=0.3,0.1

Type RM Length L Ch R = 1 ,125141.7,1247.9,1247.9,1247.9
BEGIN DESCRIPTION:
Town Creek 250.0
END DESCRIPTION:
#Sta/Elev= 30
  1323.6   82.42  1603.6   76.01  1743.6   74.97  1753.6   73.41  1763.6   74.63
  2473.6   72.43  2773.6    67.6  2993.6   69.02  3143.6   68.05  3243.6   69.49
  3473.6   68.15  3623.6   70.09  3643.6   68.55  3803.6   70.75    3910   70.67
  4183.6   67.13  4253.6   68.97  4433.3   68.42  4453.3   69.66  4643.3   66.19
  4743.3   60.65  4803.3   61.32  4975.5   59.49 4976.55   56.49 5023.38   56.49
 5024.43   59.49  5033.3   72.36  5103.3   91.22  5183.3   97.02  5258.4   97.34
#Mann= 4 , 1 , 0
 1323.60     0.2       0    3910    0.15       0  4975.5    0.05       0
 5024.43    0.15       0
Bank Sta=4975.50,5024.43
Exp/Cntr=0.3,0.1

Type RM Length L Ch R = 1 ,123893.8,686.1,686.1,686.1
BEGIN DESCRIPTION:
Town Creek 248.0
END DESCRIPTION:
#Sta/Elev= 30
  1960.1   74.82  2600.1    70.6  2910.1   67.65  2930.1   66.06  2950.1   67.21
  3400.1   68.34  3420.1   66.71  3430.1   67.95  3650.1   67.07  3710.1   63.13
  3740.1   62.68  3840.1   65.41  3930.1   61.75  4180.1   62.53  4270.1   61.21
  4530.5   65.04  4570.5   63.29  4610.5   62.92  4630.5   61.01  4890.5   63.12
  4920.5   64.37  4960.5    63.9  4975.5   58.72 4976.55   55.72 5023.38   55.72
 5024.43   58.72  5080.5   66.42  5130.5   74.75  5230.5   85.62    5414   91.78
#Mann= 3 , 1 , 0
 1960.10    0.15       0  4975.5    0.05       0 5024.43    0.15       0
Bank Sta=4975.50,5024.43
Exp/Cntr=0.3,0.1

Type RM Length L Ch R = 1 ,123207.7,675.2,675.2,675.2
BEGIN DESCRIPTION:
Town Creek 246.0
END DESCRIPTION:
#Sta/Elev= 30
  2889.2   81.28  2899.2   80.29  2919.2   65.09  2929.2   64.32  2999.2   65.02
  3079.2   63.62  3559.2   64.46  3699.2   67.31  3759.2   66.12  3969.2   65.46
  4059.2   62.43  4159.2   64.08  4309.2    60.2  4359.2   62.41  4559.2   60.89
  4709.2   61.54  4729.2   60.51  4819.2   60.95  4929.2   62.84  4975.5   58.64
 4976.55   55.64 5023.45   55.64  5024.5   58.64  5214.3   61.93  5314.3   61.53
  5334.3   63.73  5434.3   69.48  5504.3   77.62  5584.3   91.49  5609.9   93.33
#Mann= 3 , 1 , 0
 2889.20    0.15       0  4975.5    0.05       0  5024.5    0.15       0
Bank Sta=4975.50,5024.50
Exp/Cntr=0.3,0.1

Type RM Length L Ch R = 1 ,122532.5,640.6,640.6,640.6
BEGIN DESCRIPTION:
Town Creek 245.0
END DESCRIPTION:
#Sta/Elev= 30
  3013.5    75.6  3373.5   64.32  3623.5   65.65  3673.5   63.07  3713.5   62.79
  3913.5   65.13  3983.5    62.6  4162.4    66.6  4212.4   65.65  4262.4   62.95
  4412.4   61.73  4452.4   60.01  4782.4   60.51  4812.4    59.4  4952.4   61.69
 4975.57   58.56 4976.62   55.56 5023.45   55.56  5024.5   58.56  5042.4    61.5
  5072.4   61.15  5121.2   62.76  5171.2   60.97  5271.2   60.24  5331.2   62.39
  5381.2   66.66  5451.2   75.69  5551.2   86.28  5601.2   89.86    5677   88.76
#Mann= 3 , 1 , 0
 3013.50    0.15       0 4975.57    0.05       0  5024.5    0.15       0
Bank Sta=4975.57,5024.50
Exp/Cntr=0.5,0.3