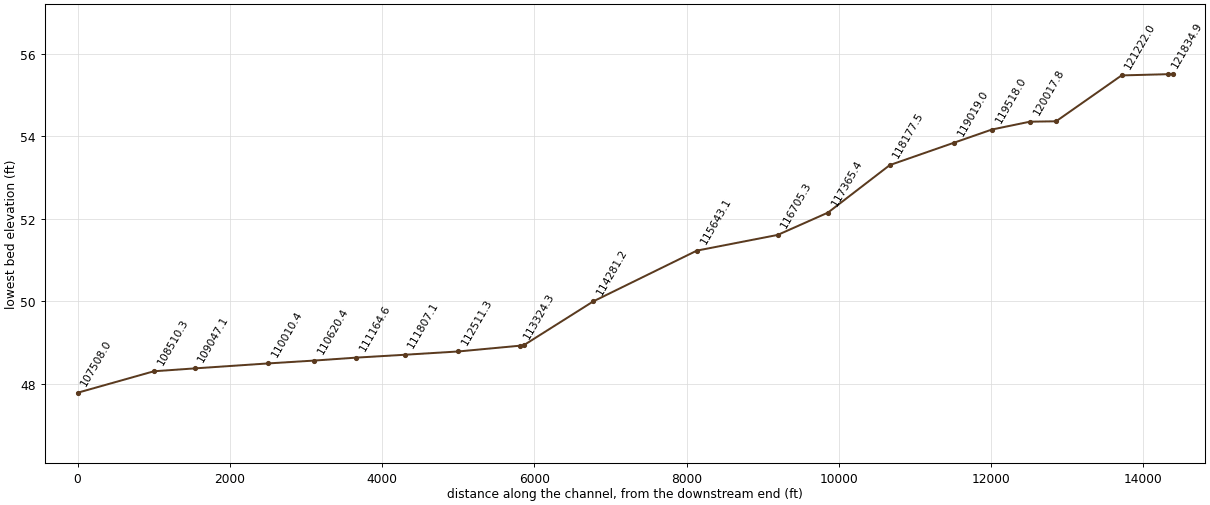
HEC-RAS study Town_Creek_FINAL.prj: Town Creek

--- Town_Creek_FINAL.g01 (geometry) --- (continued)

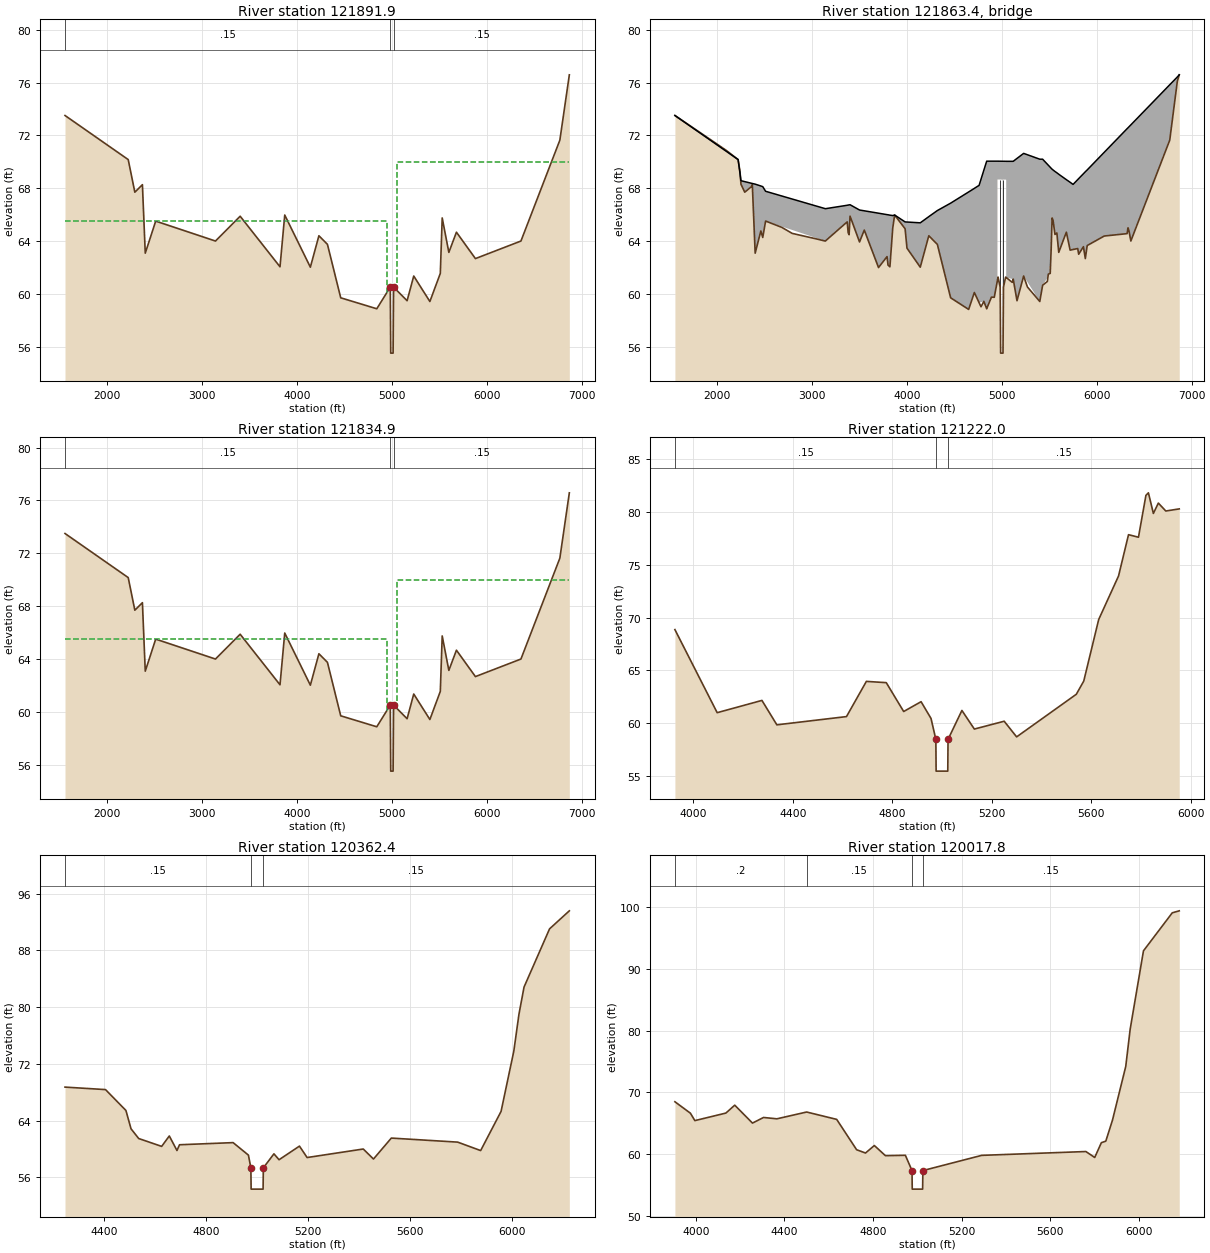
Type RM Length L Ch R = 1 ,121891.9,57,57,57
BEGIN DESCRIPTION:
Upstream Section of Bridge/Culvert/Weir
END DESCRIPTION:
#Sta/Elev= 30
  1554.7   73.51  2220.8   70.17  2290.8    67.7  2370.5   68.27  2400.5   63.08
  2510.5   65.51  3140.5      64  3400.5   65.88  3820.5   62.05  3870.5   65.97
  4140.5   62.02  4230.5    64.4  4320.5   63.75  4460.5    59.7  4840.5   58.87
  4982.5   60.51  4987.5   55.51  5012.5   55.51  5017.5   60.51    5160   59.48
    5230   61.35    5400   59.42    5510   61.55    5530   65.75    5600   63.14
    5680   64.67    5880   62.67  6359.8      64  6769.8   71.64  6869.8   76.59
#Mann= 3 , 1 , 0
 1554.70    0.15       0  4982.5    0.05       0  5017.5    0.15       0
#XS Ineff= 2 , 0
       0    4945    65.5    5055       0      70
Bank Sta=4982.50,5017.50
Exp/Cntr=0.5,0.3

Type RM Length L Ch R = 3 ,121863.4,,,
BEGIN DESCRIPTION:
Temperence Hall Rd - TOR
Structure ID: Temperence Hall Rd
Approximate Survey Structure
END DESCRIPTION:
Bridge Culvert--1,0,-1,-1, 0
Deck Dist Width WeirC Skew NumUp NumDn MinLoCord MaxHiCord MaxSubmerge Is_Ogee
10,37,2.6,, 60, 60,,,0.95,0,1,1,,
  1554.7  2220.8  2250.8  2290.8  2370.5  2400.5  2460.5  2480.5  2510.5  3140.5
  3370.5  3390.5  3400.5  3500.5  3550.5  3700.5  3790.5  3800.5  3820.5  3850.5
  3870.5  3980.5  4000.5  4140.5  4230.5  4320.5  4460.5  4650.5  4710.5  4760.5
  4810.5  4840.5  4920.5 4953.91    4954 5045.89    5046    5120    5160    5230
    5400    5430    5510    5530    5560    5580    5600    5680    5720  5750.9
    5810    5860    5880    5900    6320    6330  6359.8  6769.8  6849.8  6869.8
   73.51   70.17   68.57    68.5   68.36   68.31   68.17   68.12   67.77   66.45
   66.71   66.74   66.75   66.35   66.29   66.11      66   65.99   65.96   65.93
   65.97   65.45   65.44   65.38   65.85   66.31   66.87   67.72   67.99   68.22
   69.37   70.05   70.05   70.05   70.05   70.04   70.04   70.04   70.26   70.64
    70.2    70.2   69.59   69.44   69.27   69.17   69.06   68.65   68.45   68.29
   68.73    69.1   69.25   69.39   72.51   72.58    72.8   75.84   76.43   76.59
   73.51   70.17    68.3    67.7   68.27   63.08   64.76   64.27   65.51      64
   65.45   64.48   65.88   63.93   64.83   61.99   62.82   62.18   62.05   64.98
   65.97   64.93   63.46   62.02    64.4   63.75    59.7   58.82    60.1   59.33
   59.43   58.87   59.74   61.02   68.66   68.65   61.24   61.11   59.48   61.35
   59.42   60.65   61.55   65.75    64.5   64.61   63.14   64.67   63.31   63.36
      63   63.57   62.67   63.66   64.56      65      64   71.64   76.11   76.59
  1554.7  2220.8  2250.8  2290.8  2370.5  2400.5  2460.5  2480.5  2510.5  3140.5
  3370.5  3390.5  3400.5  3500.5  3550.5  3700.5  3790.5  3800.5  3820.5  3850.5
  3870.5  3980.5  4000.5  4140.5  4230.5  4320.5  4460.5  4650.5  4710.5  4760.5
  4810.5  4840.5  4920.5 4953.91    4954 5045.89    5046    5120    5160    5230
    5400    5430    5510    5530    5560    5580    5600    5680    5720  5750.9
    5810    5860    5880    5900    6320    6330  6359.8  6769.8  6849.8  6869.8
    73.5   70.17   68.57    68.5   68.36   68.31   68.17   68.12   67.77   66.45
   66.71   66.74   66.75   66.35   66.29   66.11      66   65.99   65.96   65.93
   65.97   65.45   65.44   65.38   65.85   66.31   66.87   67.72   67.99   68.22
   69.37   70.05   70.05   70.05   70.05   70.04   70.04   70.04   70.26   70.64
    70.2    70.2   69.59   69.44   69.27   69.17   69.06   68.65   68.45   68.29
   68.73    69.1   69.25   69.39   72.51   72.58    72.8   75.84   76.43   76.58
    73.5   70.16   68.29   67.69   68.26   63.07   64.75   64.26    65.5   63.99
   65.44   64.47   65.87   63.92   64.82   61.98   62.81   62.17   62.04   64.97
   65.96   64.92   63.45   62.01   64.39   63.74   59.69   58.81   60.09   59.32
   59.42   58.86   59.73   61.01   68.65   68.64   61.23    61.1   59.47   61.34
   59.41   60.64   61.54   65.74   64.49    64.6   63.13   64.66    63.3   63.35
   62.99   63.56   62.66   63.65   64.55   64.99   63.99   71.63    76.1   76.58
Pier Skew, UpSta & Num, DnSta & Num=,4985.0, 2 ,4985.0, 2 , 0 , 0 , 0 ,,
       1       1
   56.51   69.65
       1       1
    56.5   69.64
Pier Skew, UpSta & Num, DnSta & Num=,5015.0, 2 ,5015.0, 2 , 0 , 0 , 0 ,,
       1       1
   56.51   69.65
       1       1
    56.5   69.64
Abutment Skew #Up #Dn=, 2 , 2
 4953.80 4970.00
   68.66   60.94
 4953.80 4970.00
   68.65   60.93
Abutment Skew #Up #Dn=, 2 , 2
 5030.00 5046.09
   60.93   68.65
 5030.00 5046.09
   60.92   68.64
BR Coef= 1 , 1 , 0 ,1.25, 0 ,,,0.8,0,2,0,
Wspro=,,,, 1 ,,,, 0 ,,,, 0 ,,,,-1 ,-1 ,-1 , 0 , 0 , 0 , 0 , 0
BC Design=,, 0 ,, 0 ,,,,,,
BR U #Sta/Elev= 115
  1554.7   73.51  1794.7   72.34  1874.7   71.95  1904.7    71.8  1964.7   71.51
  2090.8   70.89  2127.7   70.69  2220.8   70.17  2240.8   69.26  2250.8    68.3
  2290.8    67.7  2317.7   67.86  2360.5   68.12  2370.5   68.27  2400.5   63.08
  2417.7   63.56  2460.5   64.76  2480.5   64.27  2497.7   64.98  2510.5   65.51
  2512.2   65.51  2572.2   65.34  2662.2   65.09  2680.5   65.04  2790.5   64.58
  3022.2    64.2  3052.2   64.15  3132.2   64.01  3140.5      64  3162.2   64.14
  3171.9    64.2  3271.9   64.83  3370.5   65.45  3380.5   64.63  3390.5   64.48
  3400.5   65.88  3431.9   65.27  3441.9   65.07  3500.5   63.93  3550.5   64.83
  3700.5   61.99  3790.5   62.82  3800.5   62.18  3820.5   62.05  3850.5   64.98
  3857.4   65.32  3867.4   65.82  3870.5   65.97  3980.5   64.93  4000.5   63.46
  4140.5   62.02  4147.4    62.2  4230.5    64.4  4300.5   63.89  4320.5   63.75
  4370.5    62.3  4460.5    59.7  4650.5   58.82  4710.5    60.1  4760.5   59.33
  4780.5   59.02  4810.5   59.43  4840.4   58.87  4840.5   58.87  4890.5   59.75
  4920.5   59.74 4953.91   61.02    4954   61.02  4960.5   61.27    4970   60.94
  4982.5   60.51  4987.5   55.51  5012.5   55.51  5017.5   60.51    5030   60.93
    5040   61.27 5045.89   61.24    5046   61.24    5110   60.87    5120   61.11
  5120.5   61.09    5160   59.48    5230   61.35  5240.5   61.13    5270   60.52
  5330.5   60.01    5400   59.42  5426.7   60.51    5430   60.65    5480   60.94
    5490   61.49    5510   61.55    5520   63.36    5530   65.75  5536.7   65.63
    5540   65.57    5560    64.5    5580   64.61    5600   63.14    5680   64.67
    5720   63.31  5750.9   63.36    5800   63.43    5810      63    5860   63.57
    5880   62.67    5900   63.66    6080   64.38    6320   64.56    6330      65
  6339.8   64.77  6359.8      64  6769.8   71.64  6849.8   76.11  6869.8   76.59
BR U #Mann= 3
 1554.70    0.15  4982.5    0.05  5017.5    0.15
BR U Banks=4982.50,5017.50
BR D #Sta/Elev= 115
  1554.7    73.5  1794.7   72.33  1874.7   71.94  1904.7   71.79  1964.7    71.5
  2090.8   70.88  2127.7   70.68  2220.8   70.16  2240.8   69.25  2250.8   68.29
  2290.8   67.69  2317.7   67.85  2360.5   68.11  2370.5   68.26  2400.5   63.07
  2417.7   63.55  2460.5   64.75  2480.5   64.26  2497.7   64.97  2510.5    65.5
  2512.2    65.5  2572.2   65.33  2662.2   65.08  2680.5   65.03  2790.5   64.57
  3022.2   64.19  3052.2   64.14  3132.2      64  3140.5   63.99  3162.2   64.13
  3171.9   64.19  3271.9   64.82  3370.5   65.44  3380.5   64.62  3390.5   64.47
  3400.5   65.87  3431.9   65.26  3441.9   65.06  3500.5   63.92  3550.5   64.82
  3700.5   61.98  3790.5   62.81  3800.5   62.17  3820.5   62.04  3850.5   64.97
  3857.4   65.31  3867.4   65.81  3870.5   65.96  3980.5   64.92  4000.5   63.45
  4140.5   62.01  4147.4   62.19  4230.5   64.39  4300.5   63.88  4320.5   63.74
  4370.5   62.29  4460.5   59.69  4650.5   58.81  4710.5   60.09  4760.5   59.32
  4780.5   59.01  4810.5   59.42  4840.4   58.86  4840.5   58.86  4890.5   59.74
  4920.5   59.73 4953.91   61.01    4954   61.01  4960.5   61.26    4970   60.93
  4982.5    60.5  4987.5    55.5  5012.5    55.5  5017.5    60.5    5030   60.92
    5040   61.26 5045.89   61.23    5046   61.23    5110   60.86    5120    61.1
  5120.5   61.08    5160   59.47    5230   61.34  5240.5   61.12    5270   60.51
  5330.5      60    5400   59.41  5426.7    60.5    5430   60.64    5480   60.93
    5490   61.48    5510   61.54    5520   63.35    5530   65.74  5536.7   65.62
    5540   65.56    5560   64.49    5580    64.6    5600   63.13    5680   64.66
    5720    63.3  5750.9   63.35    5800   63.42    5810   62.99    5860   63.56
    5880   62.66    5900   63.65    6080   64.37    6320   64.55    6330   64.99
  6339.8   64.76  6359.8   63.99  6769.8   71.63  6849.8    76.1  6869.8   76.58
BR D #Mann= 3
 1554.70    0.15  4982.5    0.05  5017.5    0.15
BR D Banks=4982.50,5017.50

Type RM Length L Ch R = 1 ,121834.9,612.9,612.9,612.9
BEGIN DESCRIPTION:
Downstream Section of Bridge/Culvert/Weir
END DESCRIPTION:
#Sta/Elev= 30
  1554.7    73.5  2220.8   70.16  2290.8   67.69  2370.5   68.26  2400.5   63.07
  2510.5    65.5  3140.5   63.99  3400.5   65.87  3820.5   62.04  3870.5   65.96
  4140.5   62.01  4230.5   64.39  4320.5   63.74  4460.5   59.69  4840.5   58.86
  4982.5    60.5  4987.5    55.5  5012.5    55.5  5017.5    60.5    5160   59.47
    5230   61.34    5400   59.41    5510   61.54    5530   65.74    5600   63.13
    5680   64.66    5880   62.66  6359.8   63.99  6769.8   71.63  6869.8   76.58
#Mann= 3 , 1 , 0
 1554.70    0.15       0  4982.5    0.05       0  5017.5    0.15       0
#XS Ineff= 2 , 0
       0    4945    65.5    5055       0      70
Bank Sta=4982.50,5017.50
Exp/Cntr=0.5,0.3

Type RM Length L Ch R = 1 ,121222.0,859.6,859.6,859.6
BEGIN DESCRIPTION:
Town Creek 242.0
END DESCRIPTION:
#Sta/Elev= 30
  3926.1   68.86  4096.1      61  4276.1   62.16  4336.1   59.85  4616.1   60.63
  4696.1   63.96  4776.1   63.84  4846.1   61.11  4916.1   62.04  4956.1   60.45
  4975.5   58.47 4976.55   55.47 5023.45   55.47  5024.5   58.47  5080.3   61.21
  5130.3   59.45  5250.3   60.19  5300.3   58.71  5540.3   62.74  5570.3   63.99
  5630.3   69.81  5710.3   73.94  5750.3   77.84  5790.3    77.6  5820.3   81.56
  5830.3    81.8  5850.3   79.85  5870.3   80.83  5900.3   80.08  5954.3   80.28
#Mann= 3 , 1 , 0
 3926.10    0.15       0  4975.5    0.05       0  5024.5    0.15       0
Bank Sta=4975.50,5024.50
Exp/Cntr=0.3,0.1

Type RM Length L Ch R = 1 ,120362.4,344.6,344.6,344.6
BEGIN DESCRIPTION:
Town Creek 241.0
END DESCRIPTION:
#Sta/Elev= 30
  4247.3   68.73    4406   68.38    4486   65.44    4506   62.86    4536   61.49
    4626   60.38    4656   61.85    4686    59.8    4696   60.61    4906   60.91
    4966   59.15 4975.57   57.36 4976.62   54.36 5023.45   54.36  5024.5   57.36
    5066   59.33    5086    58.5    5166   60.42    5196   58.81    5416   60.01
    5456    58.6    5526   61.55    5786   60.98    5876   59.79    5956   65.31
    6006   73.81    6026   78.98    6046   82.82    6146   91.02  6223.5   93.56
#Mann= 3 , 1 , 0
 4247.30    0.15       0 4975.57    0.05       0  5024.5    0.15       0
Bank Sta=4975.57,5024.50
Exp/Cntr=0.3,0.1

Type RM Length L Ch R = 1 ,120017.8,499.8,499.8,499.8
BEGIN DESCRIPTION:
Town Creek 240.0
END DESCRIPTION:
#Sta/Elev= 30
  3905.6   68.48  3975.6   66.63  3995.6   65.43  4135.6   66.65  4175.6   67.93
  4255.6   65.03  4305.6   65.94  4365.6   65.72    4500   66.82  4635.6   65.63
  4725.6   60.72  4765.6   60.19  4805.6    61.4  4855.6   59.76  4945.6   59.82
  4975.5   57.35 4976.55   54.35 5023.45   54.35  5024.5   57.35    5290   59.81
    5760   60.43    5800   59.47    5830   61.86    5850   62.11    5880   65.49
    5940   74.19    5960   80.22    6020   92.89    6150   99.04  6181.4   99.36
#Mann= 4 , 1 , 0
 3905.60     0.2       0    4500    0.15       0  4975.5    0.05       0
  5024.5    0.15       0
Bank Sta=4975.50,5024.50
Exp/Cntr=0.3,0.1

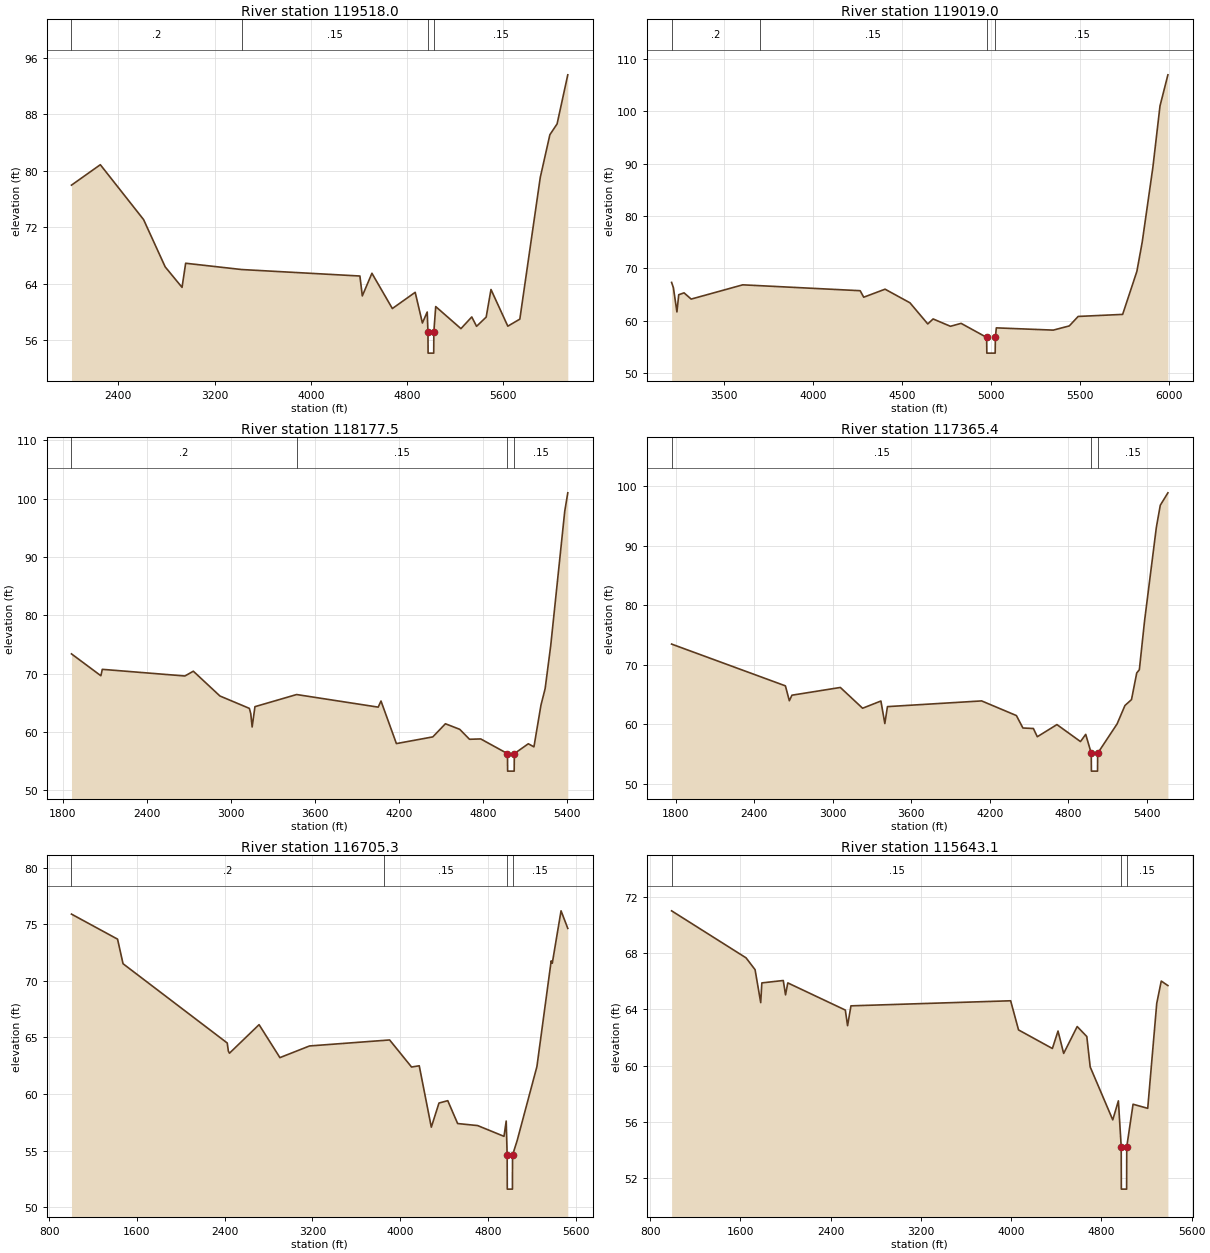
Type RM Length L Ch R = 1 ,119518.0,499,499,499
BEGIN DESCRIPTION:
Town Creek 239.0
END DESCRIPTION:
#Sta/Elev= 30
  2009.3   77.97  2249.3   80.87  2609.3   73.09  2789.3   66.38  2929.3   63.48
  2959.3    66.9    3425   66.01  4409.3   65.09  4429.3   62.27  4509.3   65.48
  4679.3   60.48  4869.3   62.78  4929.3   58.43  4969.3   59.99 4975.57   57.16
 4976.62   54.16 5023.45   54.16  5024.5   57.16    5040   60.76    5250   57.63
    5340   59.29    5380   57.96    5460   59.27    5500   63.18    5640   57.98
    5740   58.98    5910   79.06    5990   85.12    6050   86.65    6139   93.61
#Mann= 4 , 1 , 0
 2009.30     0.2       0    3425    0.15       0 4975.57    0.05       0
  5024.5    0.15       0
Bank Sta=4975.57,5024.50
Exp/Cntr=0.3,0.1

Type RM Length L Ch R = 1 ,119019.0,841.5,841.5,841.5
BEGIN DESCRIPTION:
Town Creek 238.0
END DESCRIPTION:
#Sta/Elev= 30
  3204.5   67.33  3214.5   66.34  3234.5    61.7  3244.5   64.98  3274.5   65.34
  3314.5   64.15  3604.5   66.87    3700   66.71  4264.5   65.75  4284.5   64.51
  4404.5   66.04  4544.5   63.44  4644.5   59.41  4674.5   60.36  4771.9   58.96
  4831.9   59.52  4975.5   56.84 4976.55   53.84 5023.45   53.84  5024.5   56.84
    5030   58.66    5350   58.23    5440   59.03    5490   60.84    5740   61.23
    5820   69.44    5850   75.03    5910   89.31    5950  101.01  5994.4  106.94
#Mann= 4 , 1 , 0
 3204.50     0.2       0    3700    0.15       0  4975.5    0.05       0
  5024.5    0.15       0
Bank Sta=4975.50,5024.50
Exp/Cntr=0.3,0.1

Type RM Length L Ch R = 1 ,118177.5,812.1,812.1,812.1
BEGIN DESCRIPTION:
Town Creek 236.0
END DESCRIPTION:
#Sta/Elev= 30
  1862.4    73.4  2072.4   69.65  2082.4   70.75  2672.4   69.61  2732.4   70.43
  2922.4   66.18  3132.4   64.06  3142.4   63.18  3152.4   60.87  3172.4   64.35
    3470   66.43  4052.4   64.27  4072.4   65.32  4182.4   58.02  4442.4   59.17
  4532.4   61.42  4634.4   60.47  4704.4   58.76  4784.4   58.82  4975.5    56.3
 4976.55    53.3 5023.38    53.3 5024.43    56.3  5124.4   57.99  5164.4   57.46
  5214.4   64.59  5244.4   67.45  5284.4   74.84  5384.4   97.86  5406.1  101.01
#Mann= 4 , 1 , 0
 1862.40     0.2       0    3470    0.15       0  4975.5    0.05       0
 5024.43    0.15       0
Bank Sta=4975.50,5024.43
Exp/Cntr=0.3,0.1

Type RM Length L Ch R = 1 ,117365.4,660.1,660.1,660.1
BEGIN DESCRIPTION:
Town Creek 234.0
END DESCRIPTION:
#Sta/Elev= 30
  1767.5    73.5  2637.5   66.48  2667.5   63.98  2687.5   64.91  3057.5   66.21
  3227.5   62.72  3367.5   63.93  3397.5   60.15  3417.5   62.99  4137.5   63.95
  4403.1   61.49  4453.1    59.4  4533.1   59.31  4563.1   57.93  4713.1   59.97
  4893.1   57.12  4933.1   58.33  4975.5   55.15 4976.55   52.15 5023.45   52.15
  5024.5   55.15  5173.1   60.09  5233.1   63.18  5283.1   64.17  5323.1   68.65
  5343.1   69.19  5383.1   77.43  5473.1   93.12  5503.1   96.83  5561.4   98.92
#Mann= 3 , 1 , 0
 1767.50    0.15       0  4975.5    0.05       0  5024.5    0.15       0
Bank Sta=4975.50,5024.50
Exp/Cntr=0.3,0.1

Type RM Length L Ch R = 1 ,116705.3,1062.2,1062.2,1062.2
BEGIN DESCRIPTION:
Town Creek 233.0
END DESCRIPTION:
#Sta/Elev= 30
    1004   75.89    1424   73.68    1474   71.51    2424   64.51    2434   63.79
    2444   63.61    2714   66.13    2904   63.22    3174   64.25    3850   64.74
    3904   64.78    4104   62.39    4174    62.5    4284   57.08    4354   59.21
    4434   59.42    4524    57.4  4706.7   57.22  4946.7   56.27  4966.7   57.62
  4975.5   54.61 4976.55   51.61 5023.45   51.61  5024.5   54.61  5066.7    55.9
  5246.7   62.43  5376.7   71.76  5386.7   71.55  5466.7   76.18  5528.1   74.63
#Mann= 4 , 1 , 0
 1004.00     0.2       0    3850    0.15       0  4975.5    0.05       0
  5024.5    0.15       0
Bank Sta=4975.50,5024.50
Exp/Cntr=0.3,0.1

Type RM Length L Ch R = 1 ,115643.1,1361.9,1361.9,1361.9
BEGIN DESCRIPTION:
Town Creek 231.0
END DESCRIPTION:
#Sta/Elev= 30
   989.7      71  1649.7   67.66  1729.7   66.82  1779.7   64.48  1789.7   65.88
  1979.7   66.05  1999.7   65.03  2019.7   65.88  2529.7   63.95  2549.7   62.84
  2579.7   64.25  3995.3   64.61  4065.3   62.54  4365.3   61.22  4415.3   62.46
  4465.3   60.87  4585.3   62.78  4670.5   62.07  4700.5   59.91  4900.5   56.15
  4950.5    57.5  4975.5   54.23 4976.55   51.23 5023.45   51.23  5024.5   54.23
  5080.5   57.26  5210.5   56.97  5290.5   64.43  5330.5   66.01  5389.4   65.69
#Mann= 3 , 1 , 0
  989.70    0.15       0  4975.5    0.05       0  5024.5    0.15       0
Bank Sta=4975.50,5024.50
Exp/Cntr=0.3,0.1

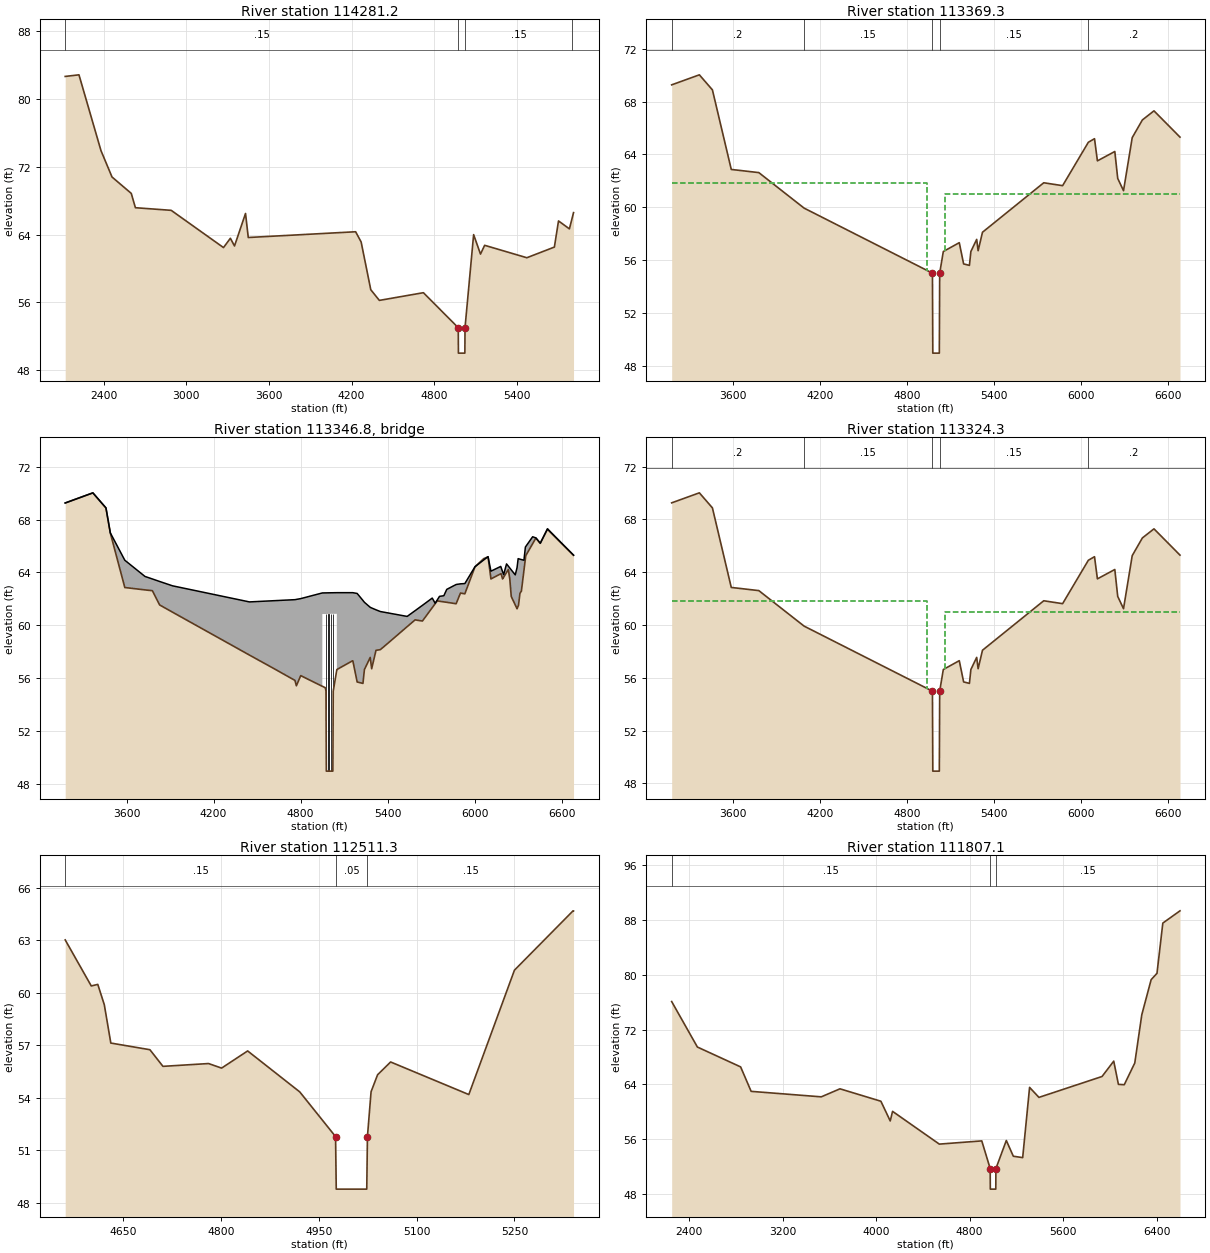
Type RM Length L Ch R = 1 ,114281.2,911.9,911.9,911.9
BEGIN DESCRIPTION:
Town Creek 229.0
END DESCRIPTION:
#Sta/Elev= 30
  2119.9   82.69  2219.9   82.88  2379.9   73.92  2459.9   70.81  2599.9   68.87
  2629.9   67.18  2889.9   66.87  3269.9   62.47  3319.9   63.57  3349.9   62.66
  3429.9    66.5  3449.9   63.66  4229.9   64.34  4269.9   63.13  4339.9   57.49
  4402.3   56.23  4722.3   57.14  4975.5      53 4976.55      50 5023.45      50
  5024.5      53  5087.1      64  5137.1    61.7  5167.1   62.74  5473.8   61.27
  5673.8   62.53  5703.8   65.62  5782.9   64.68    5800   65.77  5812.9    66.6
#Mann= 4 , 1 , 0
 2119.90    0.15       0  4975.5    0.05       0  5024.5    0.15       0
    5800     0.2       0
Bank Sta=4975.50,5024.50
Exp/Cntr=0.5,0.3

Type RM Length L Ch R = 1 ,113369.3,45,45,45
BEGIN DESCRIPTION:
Upstream Section of Bridge/Culvert/Weir
END DESCRIPTION:
#Sta/Elev= 30
  3177.1   69.27    3368   70.03    3458   68.89    3588   62.86    3778   62.62
    4090   59.93    4975      55  4977.5   48.94  5022.5   48.94    5025      55
  5049.9   56.64    5160   57.31    5190    55.7    5230   55.59    5240   56.64
    5280   57.56    5290    56.7    5320    58.1  5742.4   61.85  5872.4   61.63
    6050   64.92  6092.4   65.19  6112.4   63.51  6232.4   64.22  6252.4   62.18
  6292.4   61.25  6352.4   65.27  6422.4   66.61  6502.4    67.3  6681.8   65.31
#Mann= 5 , 1 , 0
 3177.10     0.2       0    4090    0.15       0    4975    0.05       0
    5025    0.15       0    6050     0.2       0
#XS Ineff= 2 , 0
       0    4940    61.8    5060       0      61
Bank Sta=4975.00,5025.00
Exp/Cntr=0.5,0.3

Type RM Length L Ch R = 3 ,113346.8,,,
BEGIN DESCRIPTION:
Faith Baptist Church Rd - TOR
Structure ID: Faith Baptist Church Rd
Approximate Survey Structure
END DESCRIPTION:
Bridge Culvert--1,0,-1,-1, 0
Deck Dist Width WeirC Skew NumUp NumDn MinLoCord MaxHiCord MaxSubmerge Is_Ogee
10,25,2.6,, 60, 60,,,0.95,0,1,1,,
  3177.1    3368    3458    3488    3588  3727.1    3778    3828  3917.1  4447.1
    4761    4771    4801 4949.91    4950 5049.79  5049.9    5160    5190    5230
    5240    5280    5290    5320    5350  5534.6    5590    5640  5707.7  5727.7
  5742.4  5757.7  5787.7  5807.7  5872.4  5902.4  5932.4  6002.4  6092.4  6112.4
  6179.9  6192.4  6199.9  6219.9  6232.4  6242.4  6252.4  6279.9  6292.4  6299.9
  6312.4  6322.4  6339.9  6349.9  6352.4  6399.9  6422.4  6452.4  6502.4  6681.8
   69.27   70.04    68.9   67.01   64.93    63.7   63.51   63.32   62.99   61.77
   61.94   61.96   62.02   62.45   62.45   62.47   62.47   62.47   62.41   61.88
   61.74   61.36   61.31   61.17   61.04   60.67   61.11   61.51   62.06   61.67
   61.92   62.19   62.24   62.72   63.09   63.14   63.16   64.44    65.2    64.1
   64.46   64.07   63.84   64.65   64.48   64.34    64.2   63.82   64.37   65.05
   65.01   64.98   64.93   65.93   65.97   66.71   66.62   66.22   67.31   65.31
   69.27   70.03   68.89      67   62.86   62.68   62.62   61.54   60.99   57.74
   55.82   55.41   56.18   55.37   60.85   60.87   56.64   57.31    55.7   55.59
   56.64   57.56    56.7    58.1   58.15   59.89   60.41   60.32   61.33   61.63
   61.85   61.82   61.77   61.74   61.63   62.44   62.38   64.43   65.19   63.51
    63.9   63.51   63.64      64   64.22    63.5   62.18   61.54   61.25   61.45
   62.42   62.59   64.15   65.05   65.27   66.18   66.61   66.21    67.3   65.31
  3177.1    3368    3458    3488    3588  3727.1    3778    3828  3917.1  4447.1
    4761    4771    4801 4949.91    4950 5049.79  5049.9    5160    5190    5230
    5240    5280    5290    5320    5350  5534.6    5590    5640  5707.7  5727.7
  5742.4  5757.7  5787.7  5807.7  5872.4  5902.4  5932.4  6002.4  6092.4  6112.4
  6179.9  6192.4  6199.9  6219.9  6232.4  6242.4  6252.4  6279.9  6292.4  6299.9
  6312.4  6322.4  6339.9  6349.9  6352.4  6399.9  6422.4  6452.4  6502.4  6681.8
   69.27   70.04    68.9   67.01   64.93    63.7   63.51   63.32   62.99   61.77
   61.94   61.96   62.02   62.45   62.45   62.47   62.47   62.47   62.41   61.88
   61.74   61.36   61.31   61.17   61.04   60.67   61.11   61.51   62.06   61.67
   61.92   62.19   62.24   62.72   63.09   63.14   63.16   64.44    65.2    64.1
   64.46   64.07   63.84   64.65   64.48   64.34    64.2   63.82   64.37   65.05
   65.01   64.98   64.93   65.93   65.97   66.71   66.62   66.22   67.31   65.31
   69.27   70.03   68.89      67   62.86   62.68   62.62   61.54   60.99   57.74
   55.82   55.41   56.18   55.37   60.85   60.87   56.64   57.31    55.7   55.59
   56.64   57.56    56.7    58.1   58.15   59.89   60.41   60.32   61.33   61.63
   61.85   61.82   61.77   61.74   61.63   62.44   62.38   64.43   65.19   63.51
    63.9   63.51   63.64      64   64.22    63.5   62.18   61.54   61.25   61.45
   62.42   62.59   64.15   65.05   65.27   66.18   66.61   66.21    67.3   65.31
Pier Skew, UpSta & Num, DnSta & Num=,4975.6, 2 ,4975.6, 2 , 0 , 0 , 0 ,,
       1       1
   51.33   61.86
       1       1
   51.33   61.86
Pier Skew, UpSta & Num, DnSta & Num=,4991.9, 2 ,4991.9, 2 , 0 , 0 , 0 ,,
       1       1
   47.94   61.86
       1       1
   47.94   61.86
Pier Skew, UpSta & Num, DnSta & Num=,5008.1, 2 ,5008.1, 2 , 0 , 0 , 0 ,,
       1       1
   47.94   61.87
       1       1
   47.94   61.87
Pier Skew, UpSta & Num, DnSta & Num=,5024.4, 2 ,5024.4, 2 , 0 , 0 , 0 ,,
       1       1
   51.33   61.87
       1       1
   51.33   61.87
Abutment Skew #Up #Dn=, 2 , 2
 4949.80 4967.50
   60.85   55.28
 4949.80 4967.50
   60.85   55.28
Abutment Skew #Up #Dn=, 2 , 2
 5032.50 5049.99
   55.49   60.87
 5032.50 5049.99
   55.49   60.87
BR Coef= 1 , 1 , 0 ,1.25, 0 ,,,0.8,0,2,0,
Wspro=,,,, 1 ,,,, 0 ,,,, 0 ,,,,-1 ,-1 ,-1 , 0 , 0 , 0 , 0 , 0
BC Design=,, 0 ,, 0 ,,,,,,
BR U #Sta/Elev= 94
  3177.1   69.27  3227.1   69.47  3357.1   69.99    3368   70.03  3397.1   69.66
    3458   68.89    3488      67    3588   62.86  3727.1   62.68    3778   62.62
    3828   61.54  3917.1   60.99    4090   59.93  4447.1   57.74  4608.4   56.76
  4668.4   56.39    4761   55.82    4771   55.41    4801   56.18  4822.7   56.06
 4949.91   55.37    4950   55.37  4952.7   55.36  4967.5   55.28    4971   55.26
    4975      55  4977.5   48.94  5022.5   48.94    5025      55  5032.5   55.49
 5049.79   56.63  5049.9   56.64    5050   56.64  5152.7   57.27    5160   57.31
    5190    55.7  5192.7   55.69    5230   55.59    5240   56.64  5261.5   57.13
    5280   57.56    5290    56.7    5320    58.1    5350   58.15  5371.5   58.35
  5421.5   58.82  5534.6   59.89    5590   60.41  5604.6   60.38    5640   60.32
  5707.7   61.33  5727.7   61.63  5742.4   61.85  5757.7   61.82  5787.7   61.77
  5807.7   61.74  5872.4   61.63  5879.9   61.83  5902.4   62.44  5932.4   62.38
  6002.4   64.43  6049.9   64.92    6050   64.92  6062.4   65.05  6069.9   65.08
  6092.4   65.19  6112.4   63.51  6179.9    63.9  6182.4   63.91  6192.4   63.51
  6199.9   63.64  6219.9      64  6232.4   64.22  6242.4    63.5  6252.4   62.18
  6279.9   61.54  6289.9   61.31  6292.4   61.25  6299.9   61.45  6302.4   61.51
  6312.4   62.42  6322.4   62.59  6339.9   64.15  6349.9   65.05  6352.4   65.27
  6399.9   66.18  6422.4   66.61  6439.9   66.38  6452.4   66.21  6502.4    67.3
  6505.8   67.23  6509.9   67.19  6579.9   66.42  6681.8   65.31
BR U #Mann= 5
 3177.10     0.2    4090    0.15    4975    0.05    5025    0.15    6050     0.2
BR U Banks=4975.00,5025.00
BR D #Sta/Elev= 94
  3177.1   69.27  3227.1   69.47  3357.1   69.99    3368   70.03  3397.1   69.66
    3458   68.89    3488      67    3588   62.86  3727.1   62.68    3778   62.62
    3828   61.54  3917.1   60.99    4090   59.93  4447.1   57.74  4608.4   56.76
  4668.4   56.39    4761   55.82    4771   55.41    4801   56.18  4822.7   56.06
 4949.91   55.37    4950   55.37  4952.7   55.36  4967.5   55.28    4971   55.26
    4975      55  4977.5   48.94  5022.5   48.94    5025      55  5032.5   55.49
 5049.79   56.63  5049.9   56.64    5050   56.64  5152.7   57.27    5160   57.31
    5190    55.7  5192.7   55.69    5230   55.59    5240   56.64  5261.5   57.13
    5280   57.56    5290    56.7    5320    58.1    5350   58.15  5371.5   58.35
  5421.5   58.82  5534.6   59.89    5590   60.41  5604.6   60.38    5640   60.32
  5707.7   61.33  5727.7   61.63  5742.4   61.85  5757.7   61.82  5787.7   61.77
  5807.7   61.74  5872.4   61.63  5879.9   61.83  5902.4   62.44  5932.4   62.38
  6002.4   64.43  6049.9   64.92    6050   64.92  6062.4   65.05  6069.9   65.08
  6092.4   65.19  6112.4   63.51  6179.9    63.9  6182.4   63.91  6192.4   63.51
  6199.9   63.64  6219.9      64  6232.4   64.22  6242.4    63.5  6252.4   62.18
  6279.9   61.54  6289.9   61.31  6292.4   61.25  6299.9   61.45  6302.4   61.51
  6312.4   62.42  6322.4   62.59  6339.9   64.15  6349.9   65.05  6352.4   65.27
  6399.9   66.18  6422.4   66.61  6439.9   66.38  6452.4   66.21  6502.4    67.3
  6505.8   67.23  6509.9   67.19  6579.9   66.42  6681.8   65.31
BR D #Mann= 5
 3177.10     0.2    4090    0.15    4975    0.05    5025    0.15    6050     0.2
BR D Banks=4975.00,5025.00

Type RM Length L Ch R = 1 ,113324.3,813,813,813
BEGIN DESCRIPTION:
Downstream Section of Bridge/Culvert/Weir
END DESCRIPTION:
#Sta/Elev= 30
  3177.1   69.26    3368   70.02    3458   68.88    3588   62.85    3778   62.61
    4090   59.92    4975   54.99  4977.5   48.93  5022.5   48.93    5025   54.99
  5049.9   56.63    5160    57.3    5190   55.69    5230   55.58    5240   56.63
    5280   57.55    5290   56.69    5320   58.09  5742.4   61.84  5872.4   61.62
    6050   64.91  6092.4   65.18  6112.4    63.5  6232.4   64.21  6252.4   62.17
  6292.4   61.24  6352.4   65.26  6422.4    66.6  6502.4   67.29  6681.8    65.3
#Mann= 5 , 1 , 0
 3177.10     0.2       0    4090    0.15       0    4975    0.05       0
    5025    0.15       0    6050     0.2       0
#XS Ineff= 2 , 0
       0    4940    61.8    5060       0      61
Bank Sta=4975.00,5025.00
Exp/Cntr=0.5,0.3

Type RM Length L Ch R = 1 ,112511.3,704.2,704.2,704.2
BEGIN DESCRIPTION:
Town Creek 225.0
END DESCRIPTION:
#Sta/Elev= 22
  4560.6   63.02  4600.6   60.39  4610.6   60.48  4620.6   59.32  4630.6   57.13
  4690.6   56.75  4710.6    55.8  4780.6   55.96  4800.6    55.7  4840.6   56.68
  4920.6   54.34  4975.5   51.79 4976.55   48.79 5023.38   48.79 5024.43   51.79
    5030   54.35    5040   55.32    5060   56.05    5180   54.19    5250   61.29
    5340   64.68  5340.7   64.67
#Mann= 3 , 1 , 0
 4560.60    0.15       0  4975.5    0.05       0 5024.43    0.15       0
Bank Sta=4975.50,5024.43
Exp/Cntr=0.3,0.1

Type RM Length L Ch R = 1 ,111807.1,642.5,642.5,642.5
BEGIN DESCRIPTION:
Town Creek 224.0
END DESCRIPTION:
#Sta/Elev= 30
  2250.3   76.09  2470.3   69.45  2840.3   66.55  2930.3   62.98  3530.3   62.18
  3690.3   63.35  4040.3   61.54  4120.3   58.66  4140.3   60.06  4540.3   55.28
  4903.5   55.75  4975.5   51.71 4976.55   48.71 5023.45   48.71  5024.5   51.71
  5113.5   55.81  5173.5   53.51  5253.5   53.31  5312.6   63.56  5392.6    62.1
  5932.6   65.15  6032.6   67.39  6072.6      64  6122.6   63.95  6212.6   67.12
  6272.6   74.16  6352.6   79.28  6402.6   80.21  6452.6   87.54  6599.5   89.33
#Mann= 3 , 1 , 0
 2250.30    0.15       0  4975.5    0.05       0  5024.5    0.15       0
Bank Sta=4975.50,5024.50
Exp/Cntr=0.3,0.1

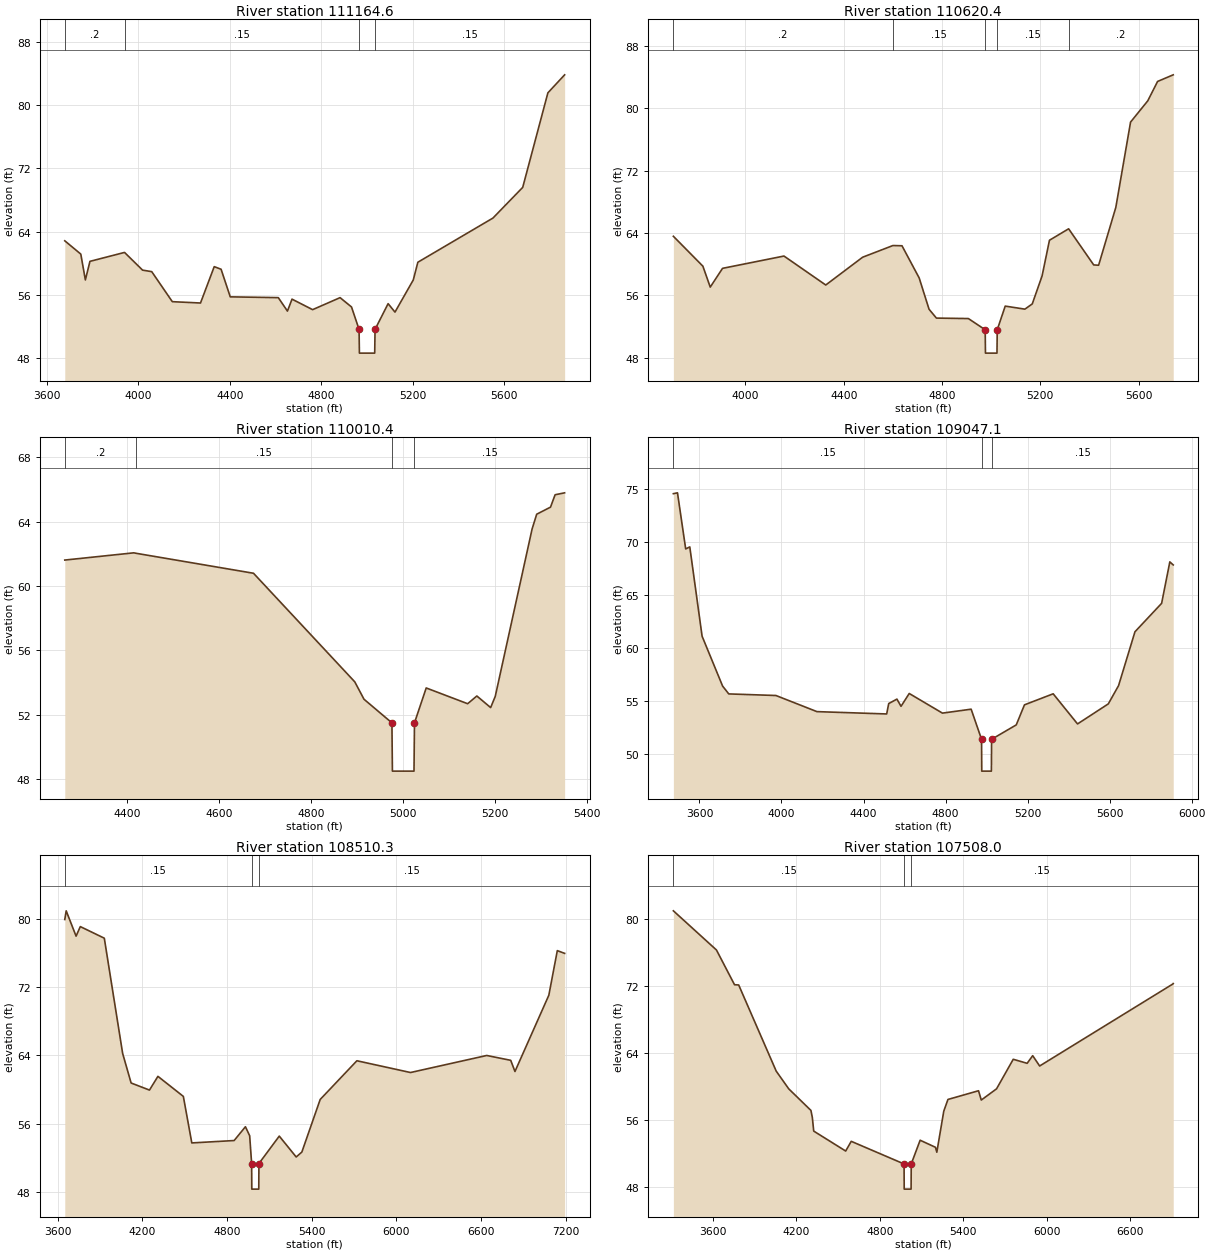
Type RM Length L Ch R = 1 ,111164.6,544.2,544.2,544.2
BEGIN DESCRIPTION:
Town Creek 223.0
END DESCRIPTION:
#Sta/Elev= 30
  3678.8   62.85  3748.8   61.17  3768.8    57.9  3788.8   60.25    3940   61.38
  4018.8   59.14  4058.8   58.95  4148.8   55.15    4272   54.98    4332   59.58
    4362   59.25    4402   55.76    4612   55.66    4652   53.96    4672   55.47
    4762   54.14    4882   55.66    4932   54.48    4965   51.64  4966.5   48.64
  5033.4   48.64  5034.9   51.64    5092    54.9    5122   53.83    5202    57.9
    5222   60.14  5550.3   65.73  5680.3   69.61  5790.3   81.57  5863.5   83.85
#Mann= 4 , 1 , 0
 3678.80     0.2       0    3940    0.15       0    4965    0.05       0
  5034.9    0.15       0
Bank Sta=4965.00,5034.90
Exp/Cntr=0.3,0.1

Type RM Length L Ch R = 1 ,110620.4,610,610,610
BEGIN DESCRIPTION:
Town Creek 221.0
END DESCRIPTION:
#Sta/Elev= 30
  3706.8   63.58  3826.8   59.74  3856.8   57.05  3906.8   59.46  4156.8   61.04
  4326.8   57.32  4476.8   60.89    4600   62.39    4637   62.36    4707   58.22
    4747   54.21    4777   53.07    4907   53.01  4975.5   51.57 4976.55   48.57
 5023.45   48.57  5024.5   51.57    5057   54.61    5137   54.22    5167   54.89
    5207   58.49    5237   63.07    5315   64.54    5417    59.9    5437   59.86
    5507   67.29    5567   78.25    5637   80.98    5677   83.47  5740.6   84.32
#Mann= 5 , 1 , 0
 3706.80     0.2       0    4600    0.15       0  4975.5    0.05       0
  5024.5    0.15       0    5315     0.2       0
Bank Sta=4975.50,5024.50
Exp/Cntr=0.3,0.1

Type RM Length L Ch R = 1 ,110010.4,963.3,963.3,963.3
BEGIN DESCRIPTION:
Town Creek 220.0
END DESCRIPTION:
#Sta/Elev= 20
  4264.8   61.62  4414.8   62.07    4420   62.04  4674.8    60.8  4894.8   54.05
  4914.8   52.97  4975.5    51.5 4976.55    48.5 5023.45    48.5  5024.5    51.5
    5050   53.67    5140   52.69    5160   53.17    5190   52.45    5200   53.15
    5280   63.55    5290   64.47    5320   64.91    5330   65.68  5350.7    65.8
#Mann= 4 , 1 , 0
 4264.80     0.2       0    4420    0.15       0  4975.5    0.05       0
  5024.5    0.15       0
Bank Sta=4975.50,5024.50
Exp/Cntr=0.3,0.1

Type RM Length L Ch R = 1 ,109047.1,536.8,536.8,536.8
BEGIN DESCRIPTION:
Town Creek 218.0
END DESCRIPTION:
#Sta/Elev= 30
  3472.9   74.54  3492.9   74.62  3532.9   69.33  3552.9   69.52  3612.9    61.1
  3712.9    56.4  3742.9   55.66  3972.9   55.51  4172.9   53.99  4512.9   53.77
  4522.9   54.75  4562.9   55.17  4582.9   54.49  4622.9    55.7  4784.8   53.85
  4924.8   54.22  4975.5   51.38 4976.55   48.38 5023.45   48.38  5024.5   51.38
  5144.8   52.74  5184.8   54.63  5324.8   55.67  5443.6   52.83  5593.6   54.72
  5643.6   56.44  5723.6   61.52  5853.6    64.2  5893.6   68.11  5910.2   67.82
#Mann= 3 , 1 , 0
 3472.90    0.15       0  4975.5    0.05       0  5024.5    0.15       0
Bank Sta=4975.50,5024.50
Exp/Cntr=0.3,0.1

Type RM Length L Ch R = 1 ,108510.3,1002.3,1002.3,1002.3
BEGIN DESCRIPTION:
Town Creek 217.0
END DESCRIPTION:
#Sta/Elev= 30
  3650.3   79.94  3660.3   80.96  3730.3   77.99  3760.3   79.11  3930.3   77.75
  4060.3   64.23  4120.3   60.76  4250.3   59.93  4310.3   61.54  4490.3   59.19
  4550.3   53.73  4850.3   54.01  4930.3   55.63  4960.3   54.57 4974.24   51.31
 4975.29   48.31 5024.78   48.31 5025.83   51.31    5170   54.53    5290   52.08
    5330   52.66    5460   58.83    5720   63.37    6100   61.99    6640   63.99
    6810   63.42    6840   62.11    7080   71.06    7140   76.29  7191.9   75.97
#Mann= 3 , 1 , 0
 3650.30    0.15       0 4974.24    0.05       0 5025.83    0.15       0
Bank Sta=4974.24,5025.83
Exp/Cntr=0.3,0.1

Type RM Length L Ch R = 1 ,107508.0,1002,1002,1002
BEGIN DESCRIPTION:
Town Creek 215.0
END DESCRIPTION:
#Sta/Elev= 29
  3314.1   80.97  3624.1    76.3  3754.1   72.16  3784.1   72.13  4054.1   61.86
  4144.1   59.75  4304.1   57.17  4314.1   56.33  4324.1   54.71  4554.1   52.33
  4594.1   53.49 4974.24   50.79 4975.29   47.79 5024.78   47.79 5025.83   50.79
    5090   53.62    5200   52.78    5210   52.19    5260   57.08    5290   58.48
    5510   59.52    5530   58.41    5640   59.75    5760   63.27    5860   62.79
    5900    63.7    5950   62.47    6910   72.26  6911.4    72.3
#Mann= 3 , 1 , 0
 3314.10    0.15       0 4974.24    0.05       0 5025.83    0.15       0
Bank Sta=4974.24,5025.83
Exp/Cntr=0.3,0.1