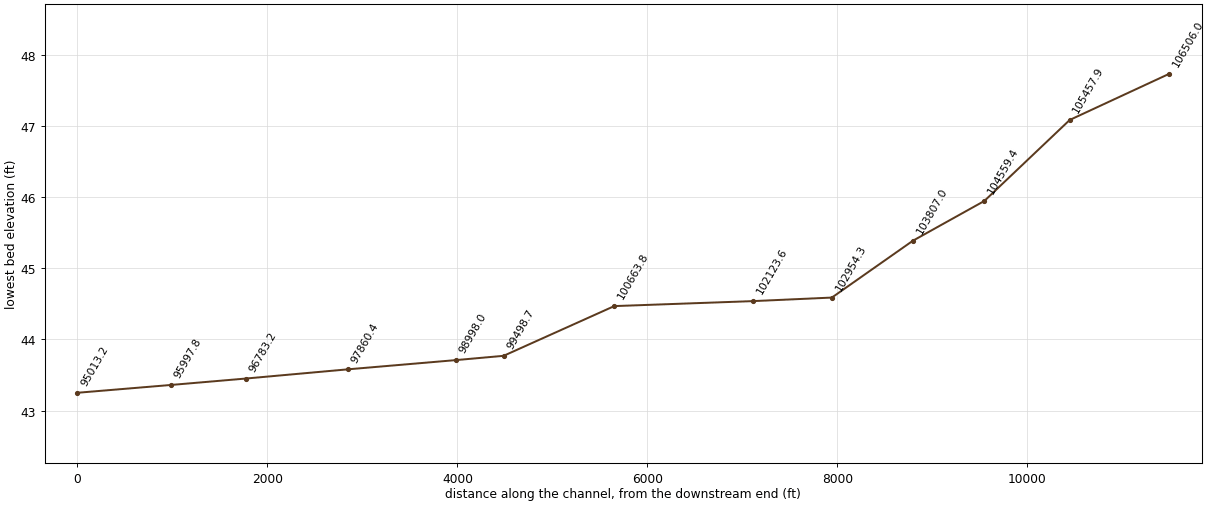
HEC-RAS study Town_Creek_FINAL.prj: Town Creek

--- Town_Creek_FINAL.g01 (geometry) --- (continued)

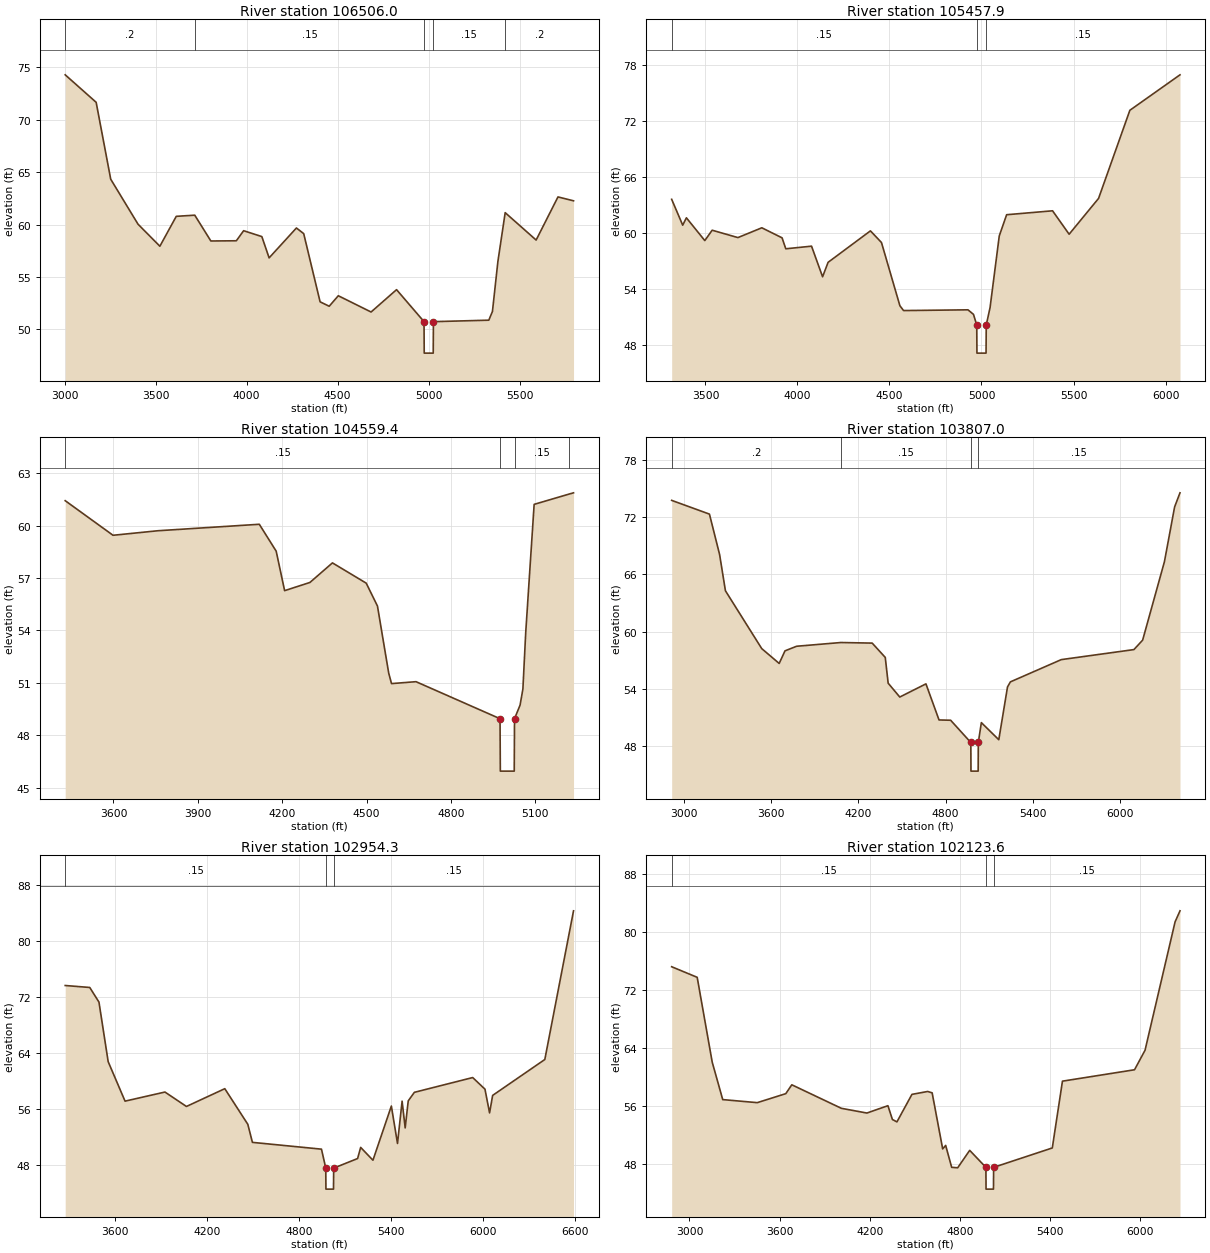
Type RM Length L Ch R = 1 ,106506.0,1048.1,1048.1,1048.1
BEGIN DESCRIPTION:
Town Creek 213.0
END DESCRIPTION:
#Sta/Elev= 30
  3003.4   74.27  3173.4   71.65  3253.4   64.32  3403.4   60.03  3523.4   57.93
  3613.4   60.78    3715   60.89  3803.4   58.43  3943.4   58.45  3983.4   59.41
  4083.4   58.85  4123.4   56.82  4273.4   59.67  4313.4   59.13  4403.4   52.63
  4453.4   52.21  4503.4   53.21  4683.4   51.66  4823.4   53.79 4974.24   50.74
 4975.29   47.74 5024.78   47.74 5025.83   50.74    5330   50.88    5350   51.71
    5380   56.48    5420   61.13    5590   58.52    5710   62.63  5795.4   62.26
#Mann= 5 , 1 , 0
 3003.40     0.2       0    3715    0.15       0 4974.24    0.05       0
 5025.83    0.15       0    5420     0.2       0
Bank Sta=4974.24,5025.83
Exp/Cntr=0.3,0.1

Type RM Length L Ch R = 1 ,105457.9,898.5,898.5,898.5
BEGIN DESCRIPTION:
Town Creek 211.0
END DESCRIPTION:
#Sta/Elev= 30
  3316.6   63.57  3376.6    60.8  3396.6   61.59  3496.6   59.15  3536.6   60.26
  3676.6   59.47  3806.6   60.52  3916.6   59.44  3936.6   58.27  4076.6   58.55
  4136.6   55.27  4166.6   56.82  4396.6   60.19  4456.6   58.94  4556.6   52.17
  4576.6   51.65  4926.6   51.73  4956.6   51.24 4974.24   50.09 4975.29   47.09
 5024.78   47.09 5025.83   50.09  5046.6   51.97  5096.6   59.65  5136.6   61.92
  5386.2   62.34  5476.2   59.83  5636.2   63.67  5806.2   73.11  6078.6   76.91
#Mann= 3 , 1 , 0
 3316.60    0.15       0 4974.24    0.05       0 5025.83    0.15       0
Bank Sta=4974.24,5025.83
Exp/Cntr=0.3,0.1

Type RM Length L Ch R = 1 ,104559.4,752.4,752.4,752.4
BEGIN DESCRIPTION:
Town Creek 209.0
END DESCRIPTION:
#Sta/Elev= 23
  3428.5   61.43  3598.5   59.45  3758.5   59.71  4118.5   60.08  4178.5   58.54
  4208.5   56.28  4298.5   56.75  4378.5   57.87  4498.5   56.71  4538.5    55.4
  4578.5   51.56  4588.5   50.96  4675.5   51.07 4974.24   48.95 4975.29   45.95
 5024.71   45.95 5025.76   48.95  5045.5   49.73  5055.5   50.65  5065.5   53.87
  5095.5   61.22    5220   61.81  5235.5   61.88
#Mann= 4 , 1 , 0
 3428.50    0.15       0 4974.24    0.05       0 5025.76    0.15       0
    5220     0.2       0
Bank Sta=4974.24,5025.76
Exp/Cntr=0.3,0.1

Type RM Length L Ch R = 1 ,103807.0,852.7,852.7,852.7
BEGIN DESCRIPTION:
Town Creek 208.0
END DESCRIPTION:
#Sta/Elev= 30
  2915.3   73.75  3175.3   72.31  3245.3   68.07  3285.3   64.28  3535.3   58.22
  3655.3   56.67  3695.3   57.99  3775.3   58.47    4080   58.86  4295.3    58.8
  4385.3    57.3  4405.3    54.6  4485.3   53.15  4665.3   54.53  4755.3   50.75
  4835.3   50.72 4974.17   48.39 4975.22   45.39 5024.71   45.39 5025.76   48.39
  5046.7   50.47  5166.7   48.68  5226.7   54.21  5246.7   54.74  5596.7   57.07
  6096.7   58.12  6156.7   59.11  6306.7   67.33  6376.7   73.06  6413.8   74.54
#Mann= 4 , 1 , 0
 2915.30     0.2       0    4080    0.15       0 4974.17    0.05       0
 5025.76    0.15       0
Bank Sta=4974.17,5025.76
Exp/Cntr=0.3,0.1

Type RM Length L Ch R = 1 ,102954.3,830.7,830.7,830.7
BEGIN DESCRIPTION:
Town Creek 206.0
END DESCRIPTION:
#Sta/Elev= 30
  3276.3   73.68  3436.3    73.4  3496.3   71.31  3556.3    62.8  3666.3   57.16
  3926.3   58.46  4066.3    56.4  4316.3   58.94  4466.3   53.85  4496.3   51.27
  4946.3    50.3 4974.24   47.59 4975.29   44.59 5024.71   44.59 5025.76   47.59
  5181.7   48.96  5201.7   50.55  5281.7   48.72  5401.7   56.46  5441.7   51.11
  5471.7   57.16  5491.7   53.34  5511.7    57.2  5551.7   58.42  5931.7   60.53
  6011.7   58.87  6041.7   55.48  6061.7   57.98  6401.7   63.11  6588.8   84.35
#Mann= 3 , 1 , 0
 3276.30    0.15       0 4974.24    0.05       0 5025.76    0.15       0
Bank Sta=4974.24,5025.76
Exp/Cntr=0.3,0.1

Type RM Length L Ch R = 1 ,102123.6,1459.8,1459.8,1459.8
BEGIN DESCRIPTION:
Town Creek 204.0
END DESCRIPTION:
#Sta/Elev= 30
  2881.8   75.17  3051.8   73.71  3151.8   62.03  3221.8   56.87  3451.8   56.45
  3641.8   57.69  3681.8   58.91  4011.8   55.67  4181.8   55.02  4321.8   56.03
  4351.8   54.13  4381.8    53.8  4481.8   57.59  4586.4   57.99  4616.4    57.8
  4686.4   50.08  4706.4   50.56  4746.4   47.54  4786.4   47.48  4866.4   49.88
 4974.24   47.54 4975.29   44.54 5024.71   44.54 5025.76   47.54  5416.4   50.21
  5484.1   59.41  5964.1   60.98  6034.1   63.67  6234.1   81.35  6266.8   82.87
#Mann= 3 , 1 , 0
 2881.80    0.15       0 4974.24    0.05       0 5025.76    0.15       0
Bank Sta=4974.24,5025.76
Exp/Cntr=0.3,0.1

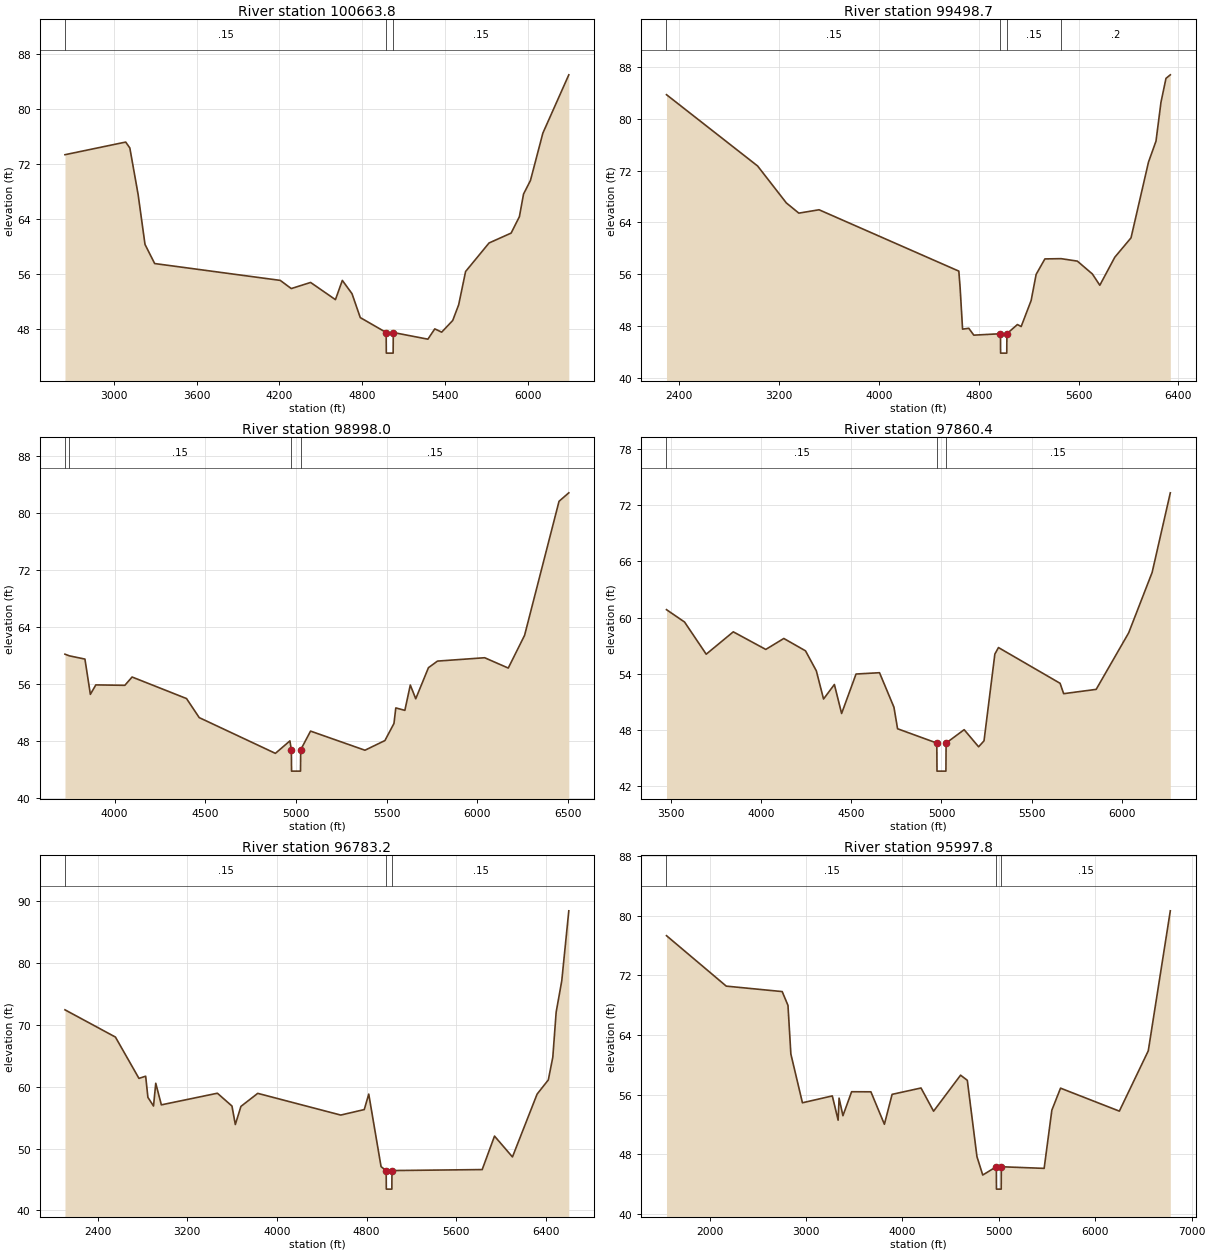
Type RM Length L Ch R = 1 ,100663.8,1165.1,1165.1,1165.1
BEGIN DESCRIPTION:
Town Creek 201.0
END DESCRIPTION:
#Sta/Elev= 30
  2646.6   73.33  3086.6   75.17  3116.6   74.31  3176.6   67.55  3226.6   60.28
  3296.6    57.5  4206.6   55.05  4286.6   53.86  4426.6   54.75  4606.6   52.25
  4656.6   55.05  4726.6   53.12  4786.6   49.64 4974.24   47.47 4975.29   44.47
 5024.78   44.47 5025.83   47.47  5276.6    46.5  5326.6      48  5376.6   47.52
  5456.6   49.22  5499.8   51.51  5549.8   56.34  5719.8   60.49  5879.8   61.93
  5939.8   64.32  5969.8   67.61  6019.8   69.58  6109.8   76.47  6297.8   84.95
#Mann= 3 , 1 , 0
 2646.60    0.15       0 4974.24    0.05       0 5025.83    0.15       0
Bank Sta=4974.24,5025.83
Exp/Cntr=0.3,0.1

Type RM Length L Ch R = 1 ,99498.7,500.7,500.7,500.7
BEGIN DESCRIPTION:
Town Creek 199.0
END DESCRIPTION:
#Sta/Elev= 30
  2299.1   83.74  3029.1   72.71  3259.1      67  3359.1   65.42  3521.2   65.94
  4640.7   56.45  4650.7   53.99  4670.7   47.48  4720.7   47.61  4760.7   46.55
 4974.24   46.77 4975.29   43.77 5024.71   43.77 5025.76   46.77    5110   48.19
    5140   47.88    5220   51.91    5260   55.95    5330   58.34    5460   58.38
    5590      58    5710   56.02    5770   54.27    5890    58.6    6020    61.6
    6160   73.32    6220   76.55    6260   82.58    6300   86.26  6334.7   86.81
#Mann= 4 , 1 , 0
 2299.10    0.15       0 4974.24    0.05       0 5025.76    0.15       0
    5460     0.2       0
Bank Sta=4974.24,5025.76
Exp/Cntr=0.3,0.1

Type RM Length L Ch R = 1 ,98998.0,1137.6,1137.6,1137.6
BEGIN DESCRIPTION:
Town Creek 198.0
END DESCRIPTION:
#Sta/Elev= 30
  3726.2   60.16    3750   59.93  3836.2   59.47  3866.2   54.51  3896.2   55.84
  4056.2   55.78  4096.2   56.95  4396.2   53.92  4466.2   51.24  4886.2   46.21
  4966.2   47.96 4974.24   46.71 4975.29   43.71 5024.71   43.71 5025.76   46.71
    5080   49.34    5380   46.65    5490   48.01    5540   50.42    5550    52.6
    5600   52.26    5630   55.82    5660   53.89    5730   58.26    5780   59.19
    6040   59.66    6170   58.21    6260   62.81    6450   81.67  6503.8   82.86
#Mann= 4 , 1 , 0
 3726.20     0.2       0    3750    0.15       0 4974.24    0.05       0
 5025.76    0.15       0
Bank Sta=4974.24,5025.76
Exp/Cntr=0.3,0.1

Type RM Length L Ch R = 1 ,97860.4,1077.2,1077.2,1077.2
BEGIN DESCRIPTION:
Town Creek 196.0
END DESCRIPTION:
#Sta/Elev= 30
  3476.9   60.84  3576.9   59.52  3696.9   56.08  3846.9   58.47  4026.9   56.59
  4126.9   57.76  4246.9   56.44  4306.9    54.3  4346.9   51.29  4406.9   52.84
  4446.9   49.74  4526.9   53.96  4656.9    54.1  4736.9   50.41  4756.9   48.11
 4974.24   46.58 4975.29   43.58 5024.71   43.58 5025.76   46.58  5125.8   48.01
  5205.8   46.18  5235.8   46.82  5295.8   56.09  5315.8   56.79    5657   52.97
    5677   51.86    5857   52.32    6037   58.36    6167   64.82  6267.7   73.33
#Mann= 3 , 1 , 0
 3476.90    0.15       0 4974.24    0.05       0 5025.76    0.15       0
Bank Sta=4974.24,5025.76
Exp/Cntr=0.3,0.1

Type RM Length L Ch R = 1 ,96783.2,785.4,785.4,785.4
BEGIN DESCRIPTION:
Town Creek 194.0
END DESCRIPTION:
#Sta/Elev= 30
  2108.1   72.43  2558.1   68.03  2768.1   61.35  2828.1    61.7  2848.1   58.28
  2898.1   56.88  2918.1   60.56  2968.1   57.07  3468.1   58.95  3598.1   56.88
  3628.1   53.89  3678.1   56.82  3828.1   58.93  4568.6   55.42  4778.6   56.31
  4818.6   58.81  4928.6   47.08 4974.24   46.45 4975.29   43.45 5024.71   43.45
 5025.76   46.45  5830.9   46.61  5940.9   52.02  6100.9   48.65  6320.9   58.81
  6420.9    61.1  6460.9   64.76  6490.9   72.06  6540.9   77.11  6603.7   88.43
#Mann= 3 , 1 , 0
 2108.10    0.15       0 4974.24    0.05       0 5025.76    0.15       0
Bank Sta=4974.24,5025.76
Exp/Cntr=0.3,0.1

Type RM Length L Ch R = 1 ,95997.8,984.6,984.6,984.6
BEGIN DESCRIPTION:
Town Creek 192.0
END DESCRIPTION:
#Sta/Elev= 30
  1553.2   77.32  2173.2   70.56  2753.2   69.83  2813.2   67.98  2843.2   61.46
  2963.2   54.93  3273.2   55.85  3333.2    52.6  3343.2   55.55  3383.2    53.2
  3473.2   56.41  3673.2    56.4  3813.2   52.05  3893.2   56.06  4193.2   56.91
  4323.2    53.8  4603.2   58.63  4673.2   57.94  4773.2   47.71  4833.2   45.25
 4974.24   46.36 4975.29   43.36 5024.78   43.36 5025.83   46.36    5470   46.14
    5550   53.94    5640   56.89    6250   53.81    6550   61.89  6778.6   80.65
#Mann= 3 , 1 , 0
 1553.20    0.15       0 4974.24    0.05       0 5025.83    0.15       0
Bank Sta=4974.24,5025.83
Exp/Cntr=0.3,0.1

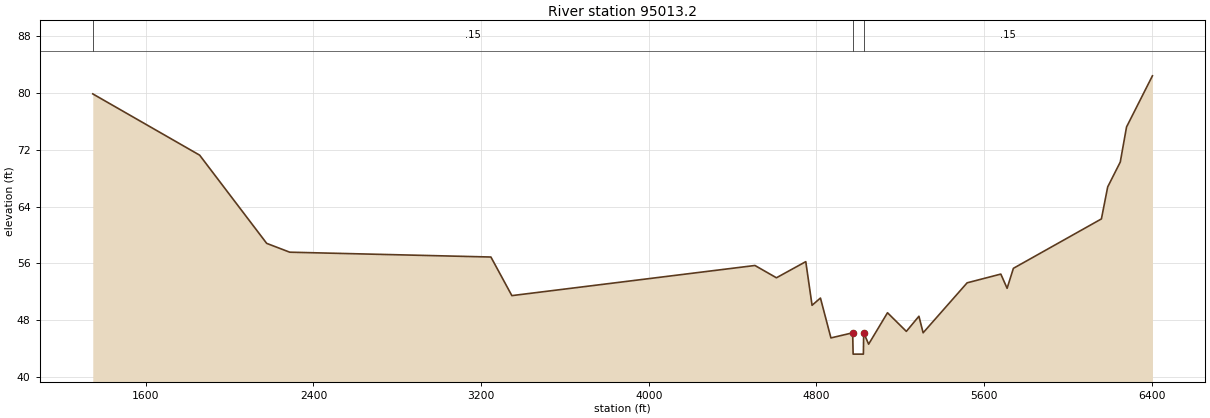
Type RM Length L Ch R = 1 ,95013.2,0,0,0
BEGIN DESCRIPTION:
Town Creek 190.0
END DESCRIPTION:
#Sta/Elev= 30
  1346.9   79.86  1856.9   71.24  2176.9   58.83  2286.9   57.59  3246.9   56.91
  3346.9   51.48  4506.9   55.72  4609.5   53.99  4749.5   56.26  4779.5   50.12
  4819.5   51.14  4869.5   45.53 4973.33   46.25 4975.43   43.25 5024.43   43.25
 5025.83   46.25  5049.5   44.65  5139.5   49.07  5229.5   46.45  5289.5   48.58
  5309.5   46.25  5519.5   53.28  5680.3   54.51  5710.3   52.51  5740.3   55.32
  6160.3   62.27  6190.3   66.77  6250.3   70.27  6280.3   75.21  6403.8    82.4
#Mann= 3 , 1 , 0
 1346.90    0.15       0 4973.33    0.05       0 5025.83    0.15       0
Bank Sta=4973.33,5025.83
Exp/Cntr=0.3,0.1

Chan Stop Cuts=-1