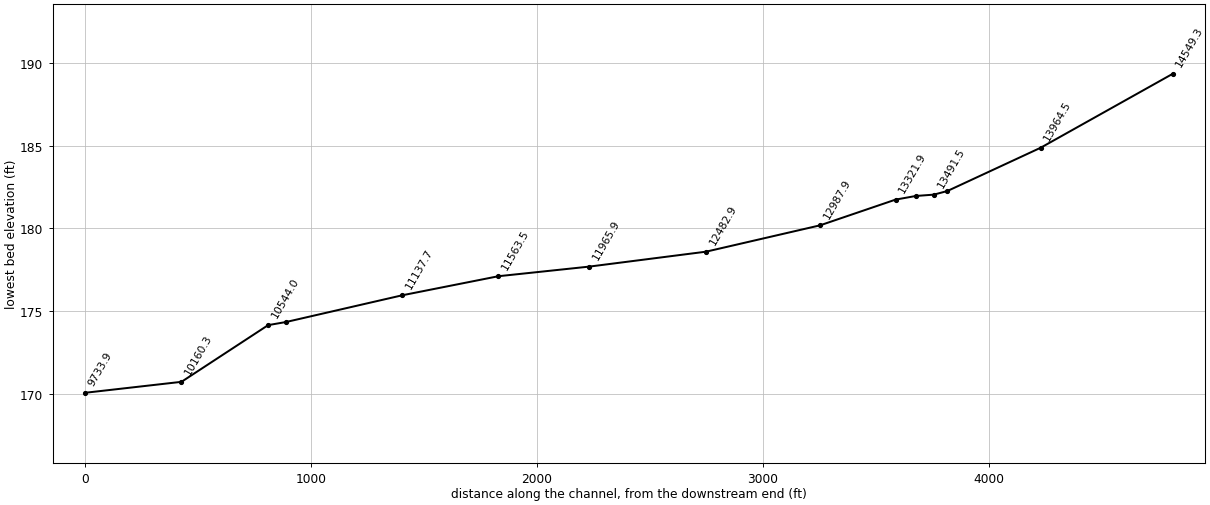
--- Millstone_Creek_021220.prj (project) ---

Proj Title=Millstone Creek
Current Plan=p02
Default Exp/Contr=0.3,0.1
English Units
Geom File=g01
Flow File=f01
Flow File=f02
Plan File=p01
Plan File=p02
Y Axis Title=Elevation
X Axis Title(PF)=Main Channel Distance
X Axis Title(XS)=Station
BEGIN DESCRIPTION:
NEUSE RIVER BASIN
Little Contentnea Creek Sub-basin
MILLSTONE CREEK
(Flood Hazard, Floodway) Model
Prepared by: Andrew J. Bonner   Date: 11/21/2002
Watershed Concepts
3333 Regency Pkwy
Cary, North Carolina 27511
END DESCRIPTION:
DSS Export Rating Curves= 0
DSS Export Rating Curve Sorted= 0
DSS Export Volume Flow Curves= 0
DXF OffsetX= 0
DXF OffsetY= 0
DXF ScaleX= 1
DXF ScaleY= 10

--- Millstone_Creek_021220.p02 (plan) ---

Plan Title=Multi_Profile
Program Version=4.00
Short Identifier=Multi_Profil
Geom File=g01
Flow File=f02
Subcritical Flow
K Sum by GR= 0
Std Step Tol= 0.01
Critical Tol= 0.01
Num of Std Step Trials= 20
Max Error Tol= 0.3
Flow Tol Ratio= 0.001
Split Flow NTrial= 30
Split Flow Tol= 0.02
Split Flow Ratio= 0.02
Log Output Level= 0
Friction Slope Method= 1
Unsteady Friction Slope Method= 2
Unsteady Bridges Friction Slope Method= 1
Parabolic Critical Depth
Global Vel Dist= 0 , 0 , 0
Global Log Level= 0
CheckData=True
Encroach Param=-1 ,0,0, 2
Computation Interval=1HOUR
Output Interval=1HOUR
Run HTab= 0
Run UNet= 0
Run PostProcess= 0
Run WQNet= 0
UNET Theta= 1
UNET Theta Warmup= 1
UNET ZTol= 0.02
UNET ZSATol= 0.1
UNET MxIter= 20
UNET MaxInSteps= 20
UNET DtIC= 0
UNET DtMin= 0
UNET MaxCRTS= 20
UNET WFStab= 2
UNET SFStab= 1
UNET WFX= 1
UNET SFX= 1
UNET DSS MLevel= 4
UNET DZMax Abort= 100
UNET Convert EG Bridges=-1
UNET Use Existing IB Tables=-1
UNET Froude Reduction=False
UNET Froude Limit= 1
UNET Froude Power= 10
UNET Time Slicing=0,0, 5
Instantaneous Interval=1HOUR
Write IC File= 0
Echo Input=False
Echo Output=False
Write Detailed= 0
Detailed Automatic Start=False, 10
WQ ULTIMATE=-1
WQ Max Comp Step=1HOUR
WQ Output Interval=15MIN
WQ Output Selected Increments= 0
WQ Output face flow=0
WQ Output face velocity=0
WQ Output face area=0
WQ Output face dispersion=0
WQ Output cell volume=0
WQ Output cell surface area=0
WQ Output cell continuity=0
WQ Output face conc=0
WQ Output face dconc_dx=0
WQ Output face courant=0
WQ Output face peclet=0
WQ Output face adv mass=0
WQ Output face disp mass=0
WQ Output cell mass=0
WQ Output cell source sink temp=0
WQ Output cell source sink nsm=0
WQ Output MaxMinRange=-1
WQ Daily Max Min Mean=-1
WQ Daily Range=0
WQ Daily Time=0
WQ Create Restart=0
WQ Fixed Restart=0
WQ System Summary=False
Sorting and Armoring Iterations= 10
XS Update Threshold= 0.02
Hydraulics Update Threshold= 0.02
Energy Slope Method= 1
Volume Change Method= 0
XS Weighting Method= 0
Number of US Weighted Cross Sections= 1
Number of DS Weighted Cross Sections= 1
Upstream XS Weight=0.25
Main XS Weight=0.5
Downstream XS Weight=0.25
Number of DS XS's Weighted with US Boundary= 1
Upstream Boundary Weight= 1
Weight of XSs Associated with US Boundary= 0
Number of US XS's Weighted with DS Boundary= 1
Downstream Boundary Weight= 0.5
Weight of XSs Associated with DS Boundary= 0.5
Sediment Output Level= 4
Mass or Volume Output= 0
Output Increment Type= 1
Profile and TS Output Increment= 10
XS Output Flag= 0
XS Output Increment= 10
Disregard all LS=0
Disregard all Conn=0
Disregard all Breaches=0
Disregard all Pumps=0

--- Millstone_Creek_021220.p01 (plan) ---

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Plan Title=100 Year Single
Short Identifier=Plan01
Geom File=g01
Flow File=f01
Encroach River=Millstone Creek
Encroach Reach=Reach - 1
Encroach Node=14549.3
       4      .8
Encroach Node=13964.5
       1    4920    5080
Encroach Node=13551.5
       1    4940    5060
Encroach Node=13491.5
       1    4940    5060
Encroach Node=13411.9
       1    4983    5200
Encroach Node=13321.9
       1    4983    5200
Encroach Node=12987.9
       1    4974    5350
Encroach Node=12482.9
       4      .7
Encroach Node=11965.9
       4      .7
Encroach Node=11563.5
       4      .7
Encroach Node=11137.7
       4      .7
Encroach Node=10624.0
       4      .7
Encroach Node=10544.0
       4      .7
Encroach Node=10160.3
       1    4760    5020
Encroach Node=9733.9
       4      .7
Encroach Node=9353.7
       4      .7
Encroach Node=8930.2
       4      .7
Encroach Node=8554.7
       1    4980    5125
Encroach Node=8200.1
       4      .7
Encroach Node=7562.3
       4      .7
Encroach Node=7025.1
       4      .7
Encroach Node=6357.7
       4      .7
Encroach Node=5734.3
       4      .7
Encroach Node=5067.4
       4      .7
Encroach Node=4625.4
       4      .7
Encroach Node=4159.3
       4      .7
Encroach Node=3384.0
       1    4980    5300
Encroach Node=3124.0
       1    4980    5300
Encroach Node=2863.4
       4      .7
Encroach Node=2475.3
       1    4850    5270
Encroach Node=1829.1
       1    4660    5470
Encroach Node=1243.7
       1    4940    5060

--- Millstone_Creek_021220.f02 (steady flow) ---

Flow Title=Multi_Profile
Program Version=4.00
Number of Profiles= 7
Profile Names=10-yr,25-yr,50-yr,500-yr,100-yr-10%,100-yr-20%,100-yr-35%
River Rch & RM=Millstone Creek,Reach - 1       ,14549.3
     413     586     739    1410    1032    1323    1617
River Rch & RM=Millstone Creek,Reach - 1       ,13551.5
     490     691     869    1646    1202    1540    1882
River Rch & RM=Millstone Creek,Reach - 1       ,11965.9
     573     805    1010    1899    1382    1772    2165
River Rch & RM=Millstone Creek,Reach - 1       ,8930.2
     714     998    1248    2323    1685    2159    2638
River Rch & RM=Millstone Creek,Reach - 1       ,6357.7
     787    1098    1370    2540    1839    2356    2879
River Rch & RM=Millstone Creek,Reach - 1       ,3384.0
     914    1270    1581    2911    2102    2694    3291
Boundary for River Rch & Prof#=Millstone Creek,Reach - 1       , 1
Up Type= 0
Dn Type= 1
Dn Known WS=157.11
Boundary for River Rch & Prof#=Millstone Creek,Reach - 1       , 2
Up Type= 0
Dn Type= 1
Dn Known WS=157.98
Boundary for River Rch & Prof#=Millstone Creek,Reach - 1       , 3
Up Type= 0
Dn Type= 1
Dn Known WS=158.73
Boundary for River Rch & Prof#=Millstone Creek,Reach - 1       , 4
Up Type= 0
Dn Type= 1
Dn Known WS=161.63
Boundary for River Rch & Prof#=Millstone Creek,Reach - 1       , 5
Up Type= 0
Dn Type= 1
Dn Known WS=160.04
Boundary for River Rch & Prof#=Millstone Creek,Reach - 1       , 6
Up Type= 0
Dn Type= 1
Dn Known WS=161.78
Boundary for River Rch & Prof#=Millstone Creek,Reach - 1       , 7
Up Type= 0
Dn Type= 1
Dn Known WS=161.54
DSS Import GetInterval= 0
DSS Import GetPeak= 0
DSS Import FillOption= 0

--- Millstone_Creek_021220.f01 (steady flow) ---

Flow Title= 100 Year Single
Program Version=4.00
Number of Profiles= 2
Profile Names=100-Year,AFW
River Rch & RM=Millstone Creek,Reach - 1       ,14549.3
     911     911
River Rch & RM=Millstone Creek,Reach - 1       ,13551.5
    1069    1069
River Rch & RM=Millstone Creek,Reach - 1       ,11965.9
    1240    1240
River Rch & RM=Millstone Creek,Reach - 1       ,8930.2
    1527    1527
River Rch & RM=Millstone Creek,Reach - 1       ,6357.7
    1674    1674
River Rch & RM=Millstone Creek,Reach - 1       ,3384.0
    1927    1927
Boundary for River Rch & Prof#=Millstone Creek,Reach - 1       , 1
Up Type= 0
Dn Type= 1
Dn Known WS=159.61
Boundary for River Rch & Prof#=Millstone Creek,Reach - 1       , 2
Up Type= 0
Dn Type= 1
Dn Known WS=160.2
DSS Import GetInterval= 0
DSS Import GetPeak= 0
DSS Import FillOption= 0

--- Millstone_Creek_021220.g01 (geometry) ---

Geom Title=Geom 01 by CodeH2 for Windows
Program Version=4.00

River Reach=Millstone Creek ,Reach - 1
Reach XY= 30
  0.053123415452  0.074966558855  0.073445874618  0.074051508447
  0.103165456624  0.083165694702  0.121261772287  0.112621163015
  0.141470997498  0.122659747197   0.16934102904  0.114866129409
  0.207250399374  0.120546083039  0.222968937185  0.139434739782
  0.238423361304  0.140887365096  0.281879873811  0.178136451196
  0.335374970499  0.187646807992  0.345777276968  0.197031899435
  0.368740076085  0.200483488103  0.374293255142  0.207987335439
  0.394704715981  0.210088925828  0.423370861655   0.22419637011
  0.491568790352  0.236143364379  0.501894126544    0.2308603359
  0.547880093623  0.237824636691  0.602030192272  0.230740352822
  0.624122170811  0.221254898175  0.649096761662  0.227498545888
  0.665905711723  0.247189353649  0.696522525676  0.254873552907
  0.714476974555  0.267569120845  0.761599385126   0.25355298444
  0.793416784469  0.264718956788  0.830637195368  0.268441450644
  0.861854679321  0.287051656094  0.885338094682  0.334723793303

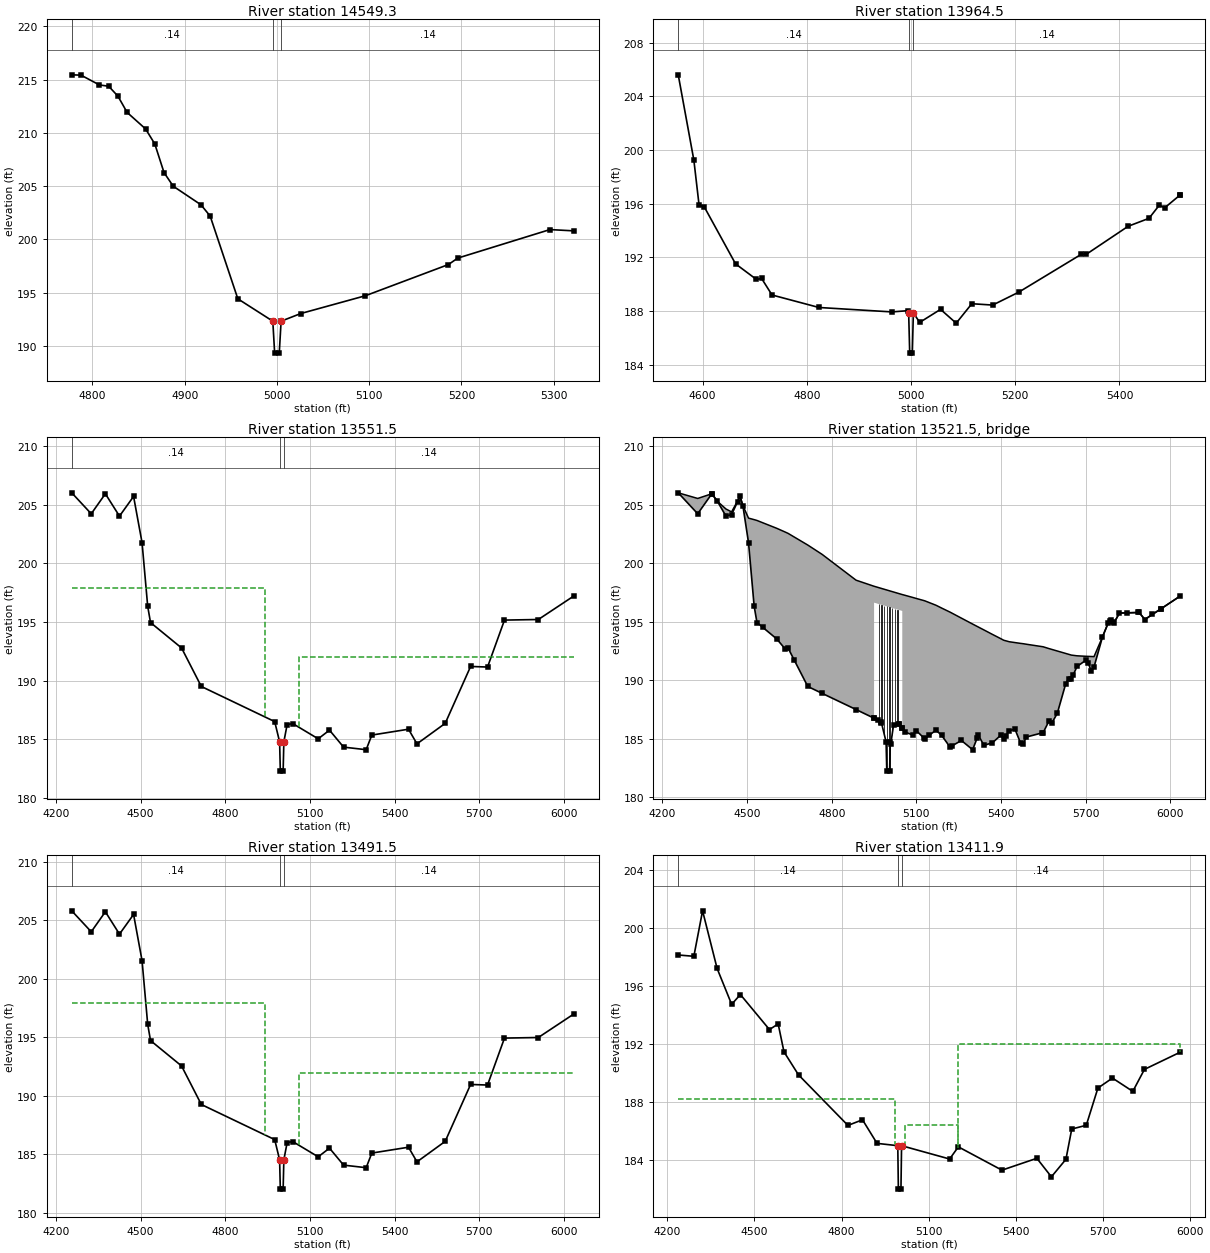
Type RM Length L Ch R = 1 ,14549.3 ,584.8,584.8,584.8
BEGIN DESCRIPTION:
Millstone Creek 22.0
END DESCRIPTION:
#Sta/Elev= 23
  4777.6  215.46  4787.6  215.43  4807.6  214.51  4817.6  214.39  4827.6  213.46
  4837.6  211.93  4857.6  210.38  4867.6  208.97  4877.6  206.28  4887.6     205
  4917.6  203.26  4927.6   202.2  4957.6  194.43  4995.5  192.33  4997.5  189.33
  5002.5  189.33  5004.5  192.33  5025.9  193.05  5095.9  194.72  5185.9  197.65
  5195.9  198.25  5295.9  200.93  5321.8  200.81
#Mann= 3 , 1 , 0
  4777.6     .14       0  4995.5    .048       0  5004.5     .14       0
Bank Sta=4995.5,5004.5
XS Rating Curve= 0 ,0
Exp/Cntr=0.3,0.1

Type RM Length L Ch R = 1 ,13964.5 ,413,413,413
BEGIN DESCRIPTION:
Millstone Creek 21.0
END DESCRIPTION:
#Sta/Elev= 29
  4553.3   205.6  4583.3  199.24  4593.3  195.89  4603.3  195.76  4663.3  191.52
  4703.3  190.36  4713.3  190.43  4733.3   189.2  4823.3  188.27  4963.3  187.94
  4993.3  188.03  4995.5  187.87  4997.5  184.87  5002.5  184.87  5004.5  187.87
  5016.7  187.16  5056.7  188.13  5086.7   187.1  5116.7  188.55  5156.7  188.45
  5206.7  189.41  5326.7  192.23  5336.7  192.24  5416.7  194.32  5456.7  194.91
  5476.7   195.9  5486.7  195.69  5516.7  196.66  5516.8  196.66
#Mann= 3 , 1 , 0
  4553.3     .14       0  4995.5    .048       0  5004.5     .14       0
Bank Sta=4995.5,5004.5
XS Rating Curve= 0 ,0
Exp/Cntr=0.5,0.3

Type RM Length L Ch R = 1 ,13551.5 ,60,60,60
BEGIN DESCRIPTION:
Upstream Section of Bridge/Culvert/Weir
END DESCRIPTION:
#Sta/Elev= 30
  4256.1  206.03  4325.1  204.24  4375.1  205.95  4425.1  204.04  4475.1  205.72
  4505.1  201.78  4525.1  196.34  4535.1  194.95  4645.1  192.78  4715.1  189.49
  4975.1  186.49  4992.5  184.76    4995  182.26    5005  182.26  5007.5  184.76
  5019.2  186.24  5039.2  186.32  5129.2  185.02  5169.2  185.76  5219.2  184.31
  5299.2  184.09  5319.2  185.34  5449.2  185.84  5479.2  184.59  5579.2  186.34
  5669.2   191.2  5729.2  191.15  5789.2  195.16  5909.2  195.21    6035  197.22
#Mann= 3 , 1 , 0
  4256.1     .14       0  4992.5    .048       0  5007.5     .14       0
#XS Ineff= 2 , 0
       0    4940   197.9    5060       0     192
Permanent Ineff=
       F       F
Bank Sta=4992.5,5007.5
XS Rating Curve= 0 ,0
Exp/Cntr=0.5,0.3

Type RM Length L Ch R = 3 ,13521.5 ,,,
BEGIN DESCRIPTION:
Railroad-TOR
Structure ID: MC - Railroad
Approximate Survey Structure
END DESCRIPTION:
Bridge Culvert--1,0,-1,-1, 0
Deck Dist Width WeirC Skew NumUp NumDn MinLoCord MaxHiCord MaxSubmerge Is_Ogee
10,40,2.6,0, 60, 60, , , 0.95, 0, 1,1,,
  4256.1  4325.1  4375.1  4395.1  4425.1  4445.1  4475.1  4485.1  4505.1  4525.1
  4535.1  4605.1  4635.1  4645.1  4715.1  4766.1  4886.1 4949.91    4950 5049.89
    5050  5059.2  5089.2  5099.2  5129.2  5169.2  5189.2  5219.2  5259.2  5299.2
  5319.2  5339.2  5369.2  5399.2  5409.2  5429.2  5449.2  5469.2  5479.2  5489.2
  5549.2  5569.2  5579.2  5599.2  5629.2  5639.2  5649.2  5669.2  5699.2  5709.2
  5719.2  5729.2  5759.2  5779.2  5789.2  5799.2  5819.2  5889.2  5909.2    6035
  206.02  205.54  205.94  205.29  204.64  204.39  205.71  204.93  203.86  203.73
  203.66  202.99  202.67  202.56  201.56  200.76  198.56  198.04  198.04  197.33
  197.33  197.27  197.07     197   196.8  196.42  196.18  195.83  195.32  194.81
  194.56  194.31  193.93  193.56  193.43   193.3  193.23  193.16  193.13  193.09
  192.87  192.72  192.65  192.51   192.3  192.23  192.16   192.1  192.06  192.05
  192.04  192.03  193.71  194.89  195.15  194.87  195.75   195.8   195.2  197.21
  206.02  204.23  205.94  205.29  204.03  204.16  205.71  204.93  201.77  196.33
  194.94  193.54  192.68  192.77  189.48  188.89  187.51  186.77  196.64  195.93
  185.92  185.59  185.32  185.72  185.01  185.75  185.31   184.3  184.87  184.08
  185.33  184.45  184.67  185.32  184.98  185.71  185.83  184.64  184.58  185.16
  185.54  186.51  186.33  187.19  189.73  190.14  190.14  191.19   191.7  191.46
   190.8  191.14  193.71  194.89  195.15  194.87  195.75   195.8   195.2  197.21
  4256.1  4325.1  4375.1  4395.1  4425.1  4445.1  4475.1  4485.1  4505.1  4525.1
  4535.1  4605.1  4635.1  4645.1  4715.1  4766.1  4886.1 4949.91    4950 5049.89
    5050  5059.2  5089.2  5099.2  5129.2  5169.2  5189.2  5219.2  5259.2  5299.2
  5319.2  5339.2  5369.2  5399.2  5409.2  5429.2  5449.2  5469.2  5479.2  5489.2
  5549.2  5569.2  5579.2  5599.2  5629.2  5639.2  5649.2  5669.2  5699.2  5709.2
  5719.2  5729.2  5759.2  5779.2  5789.2  5799.2  5819.2  5889.2  5909.2    6035
  205.92  205.54  205.85   205.2  204.64  204.39  205.62  204.84  203.86  203.73
  203.66  202.99  202.67  202.56  201.56  200.76  198.56  198.04  198.04  197.33
  197.33  197.27  197.07     197   196.8  196.42  196.18  195.83  195.32  194.81
  194.56  194.31  193.93  193.56  193.43   193.3  193.23  193.16  193.13  193.09
  192.87  192.72  192.65  192.51   192.3  192.23  192.16   192.1  192.06  192.05
  192.04  192.03  193.62   194.8  195.06  194.78  195.66  195.71  195.11  197.11
  205.82  204.03  205.74  205.09  203.83  203.96  205.51  204.73  201.57  196.13
  194.74  193.34  192.48  192.57  189.28  188.69  187.31  186.57  196.44  195.73
  185.72  185.39  185.12  185.52  184.81  185.55  185.11   184.1  184.67  183.88
  185.13  184.25  184.47  185.12  184.78  185.51  185.63  184.44  184.38  184.96
  185.34  186.31  186.13  186.99  189.53  189.94  189.94  190.99   191.5  191.26
   190.6  190.94  193.51  194.69  194.95  194.67  195.55   195.6     195  197.01
Pier Skew, UpSta & Num, DnSta & Num=  ,4967.2, 2 ,4967.2, 2 , 0 , 0 , 0 ,,
       1       1
  185.57  197.51
       1       1
  185.37  197.31
Pier Skew, UpSta & Num, DnSta & Num=  ,4976.5, 2 ,4976.5, 2 , 0 , 0 , 0 ,,
       1       1
  185.29  197.43
       1       1
  185.09  197.23
Pier Skew, UpSta & Num, DnSta & Num=  ,4985.9, 2 ,4985.9, 2 , 0 , 0 , 0 ,,
       1       1
  184.36  197.37
       1       1
  184.16  197.17
Pier Skew, UpSta & Num, DnSta & Num=  ,4995.3, 2 ,4995.3, 2 , 0 , 0 , 0 ,,
       1       1
  181.25   197.3
       1       1
  181.05   197.1
Pier Skew, UpSta & Num, DnSta & Num=  ,5004.7, 2 ,5004.7, 2 , 0 , 0 , 0 ,,
       1       1
  181.25  197.24
       1       1
  181.05  197.04
Pier Skew, UpSta & Num, DnSta & Num=  ,5014, 2 ,5014, 2 , 0 , 0 , 0 ,,
       1       1
  184.28  197.18
       1       1
  184.08  196.98
Pier Skew, UpSta & Num, DnSta & Num=  ,5023.4, 2 ,5023.4, 2 , 0 , 0 , 0 ,,
       1       1
  185.24  197.12
       1       1
  185.04  196.92
Pier Skew, UpSta & Num, DnSta & Num=  ,5032.8, 2 ,5032.8, 2 , 0 , 0 , 0 ,,
       1       1
  185.28  197.05
       1       1
  185.08  196.85
Abutment Skew #Up #Dn= , 2 , 2
  4949.8  4962.5
  196.64  186.63
  4949.8  4962.5
  196.44  186.43
Abutment Skew #Up #Dn= , 2 , 2
  5037.5 5050.09
   186.3  195.93
  5037.5 5050.09
   186.1  195.73
BR Coef= 1 , 1 , 0 ,1.25, 0 ,,,0.8,0,2,0,
WSPro=,,,, 1 ,,,, 0 ,,,, 0 ,,,,-1 ,-1 ,-1 , 0 , 0 , 0 , 0 , 0
BR U #Sta/Elev= 89
  4256.1  206.02  4325.1  204.23  4375.1  205.94  4376.1  205.91  4395.1  205.29
  4425.1  204.03  4445.1  204.16  4466.1  205.25  4475.1  205.71  4485.1  204.93
  4505.1  201.77  4525.1  196.33  4535.1  194.94  4556.1  194.52  4605.1  193.54
  4635.1  192.68  4645.1  192.77  4666.1  191.78  4715.1  189.48  4766.1  188.89
  4886.1  187.51 4949.91  186.77    4950  186.77  4962.5  186.63  4975.1  186.48
  4976.1  186.38  4992.5  184.75    4995  182.25    5005  182.25  5007.5  184.75
  5009.2  184.57  5019.2  186.23  5037.5   186.3  5039.2  186.31 5049.89  185.93
    5050  185.92  5059.2  185.59  5089.2  185.32  5099.2  185.72  5125.9  185.09
  5129.2  185.01  5145.9  185.32  5169.2  185.75  5189.2  185.31  5219.2   184.3
  5225.9   184.4  5259.2  184.87  5299.2  184.08  5315.9  185.12  5319.2  185.33
  5339.2  184.45  5369.2  184.67  5399.2  185.32  5409.2  184.98  5415.9  185.22
  5429.2  185.71  5449.2  185.83  5469.2  184.64  5479.2  184.58  5489.2  185.16
  5545.9  185.52  5549.2  185.54  5569.2  186.51  5579.2  186.33  5599.2  187.19
  5629.2  189.73  5639.2  190.14  5649.2  190.14  5655.9  190.49  5669.2  191.19
  5699.2   191.7  5709.2  191.46  5719.2   190.8  5729.2  191.14  5759.2  193.71
  5779.2  194.89  5785.9  195.06  5789.2  195.15  5795.9  194.96  5799.2  194.87
  5819.2  195.75  5845.9  195.77  5885.9   195.8  5889.2   195.8  5909.2   195.2
  5935.9  195.63  5965.9  196.11    5967  196.12    6035  197.21
BR U #Mann= 3
  4256.1     .14  4992.5    .048  5007.5     .14
BR U Banks=4992.5,5007.5
BR D #Sta/Elev= 89
  4256.1  205.82  4325.1  204.03  4375.1  205.74  4376.1  205.71  4395.1  205.09
  4425.1  203.83  4445.1  203.96  4466.1  205.05  4475.1  205.51  4485.1  204.73
  4505.1  201.57  4525.1  196.13  4535.1  194.74  4556.1  194.32  4605.1  193.34
  4635.1  192.48  4645.1  192.57  4666.1  191.58  4715.1  189.28  4766.1  188.69
  4886.1  187.31 4949.91  186.57    4950  186.57  4962.5  186.43  4975.1  186.28
  4976.1  186.18  4992.5  184.55    4995  182.05    5005  182.05  5007.5  184.55
  5009.2  184.37  5019.2  186.03  5037.5   186.1  5039.2  186.11 5049.89  185.73
    5050  185.72  5059.2  185.39  5089.2  185.12  5099.2  185.52  5125.9  184.89
  5129.2  184.81  5145.9  185.12  5169.2  185.55  5189.2  185.11  5219.2   184.1
  5225.9   184.2  5259.2  184.67  5299.2  183.88  5315.9  184.92  5319.2  185.13
  5339.2  184.25  5369.2  184.47  5399.2  185.12  5409.2  184.78  5415.9  185.02
  5429.2  185.51  5449.2  185.63  5469.2  184.44  5479.2  184.38  5489.2  184.96
  5545.9  185.32  5549.2  185.34  5569.2  186.31  5579.2  186.13  5599.2  186.99
  5629.2  189.53  5639.2  189.94  5649.2  189.94  5655.9  190.29  5669.2  190.99
  5699.2   191.5  5709.2  191.26  5719.2   190.6  5729.2  190.94  5759.2  193.51
  5779.2  194.69  5785.9  194.86  5789.2  194.95  5795.9  194.76  5799.2  194.67
  5819.2  195.55  5845.9  195.57  5885.9   195.6  5889.2   195.6  5909.2     195
  5935.9  195.43  5965.9  195.91    5967  195.92    6035  197.01
BR D #Mann= 3
  4256.1     .14  4992.5    .048  5007.5     .14
BR D Banks=4992.5,5007.5
BC Design=,, 0 ,, 0 ,,,,,,
BC HTab HWMax=206.03
BC Use User HTab Curves=0
BC User HTab FreeFlow(D)= 0

Type RM Length L Ch R = 1 ,13491.5 ,79.6,79.6,79.6
BEGIN DESCRIPTION:
Downstream Section of Bridge/Culvert/Weir
END DESCRIPTION:
#Sta/Elev= 30
  4256.1  205.81  4325.1  204.02  4375.1  205.73  4425.1  203.82  4475.1   205.5
  4505.1  201.56  4525.1  196.12  4535.1  194.73  4645.1  192.56  4715.1  189.27
  4975.1  186.27  4992.5  184.54    4995  182.04    5005  182.04  5007.5  184.54
  5019.2  186.02  5039.2   186.1  5129.2   184.8  5169.2  185.54  5219.2  184.09
  5299.2  183.87  5319.2  185.12  5449.2  185.62  5479.2  184.37  5579.2  186.12
  5669.2  190.98  5729.2  190.93  5789.2  194.94  5909.2  194.99    6035     197
#Mann= 3 , 1 , 0
  4256.1     .14       0  4992.5    .048       0  5007.5     .14       0
#XS Ineff= 2 , 0
       0    4940   197.9    5060       0     192
Permanent Ineff=
       F       F
Bank Sta=4992.5,5007.5
XS Rating Curve= 0 ,0
Exp/Cntr=0.5,0.3

Type RM Length L Ch R = 1 ,13411.9 ,90,90,90
BEGIN DESCRIPTION:
Upstream Section of Bridge/Culvert/Weir
END DESCRIPTION:
#Sta/Elev= 30
  4238.4  198.13  4292.1  198.04  4322.1  201.18  4372.1   197.2  4422.1  194.72
  4452.1   195.4  4552.1  192.98  4582.1  193.37  4602.1  191.44  4652.1  189.85
  4822.1  186.36  4872.1  186.75  4922.1  185.12  4993.5  184.96  4995.5  181.96
  5004.4  181.96  5006.5  184.96  5171.8  184.04  5201.8  184.88  5351.8  183.27
  5471.8  184.09  5521.8  182.81  5571.8  184.02  5591.8  186.11  5641.8  186.37
  5681.8  188.94  5731.8  189.63  5801.8  188.71  5841.8  190.23  5965.2  191.42
#Mann= 3 ,-1 , 0
  4238.4     .14       0  4993.5    .048       0  5006.5     .14       0
#XS Ineff= 3 ,-1
    4200    4983   188.2    5017    5200   186.4    5200    6000     192
Permanent Ineff=
       F       F       F
Bank Sta=4993.5,5006.5
XS Rating Curve= 0 ,0
Exp/Cntr=0.5,0.3

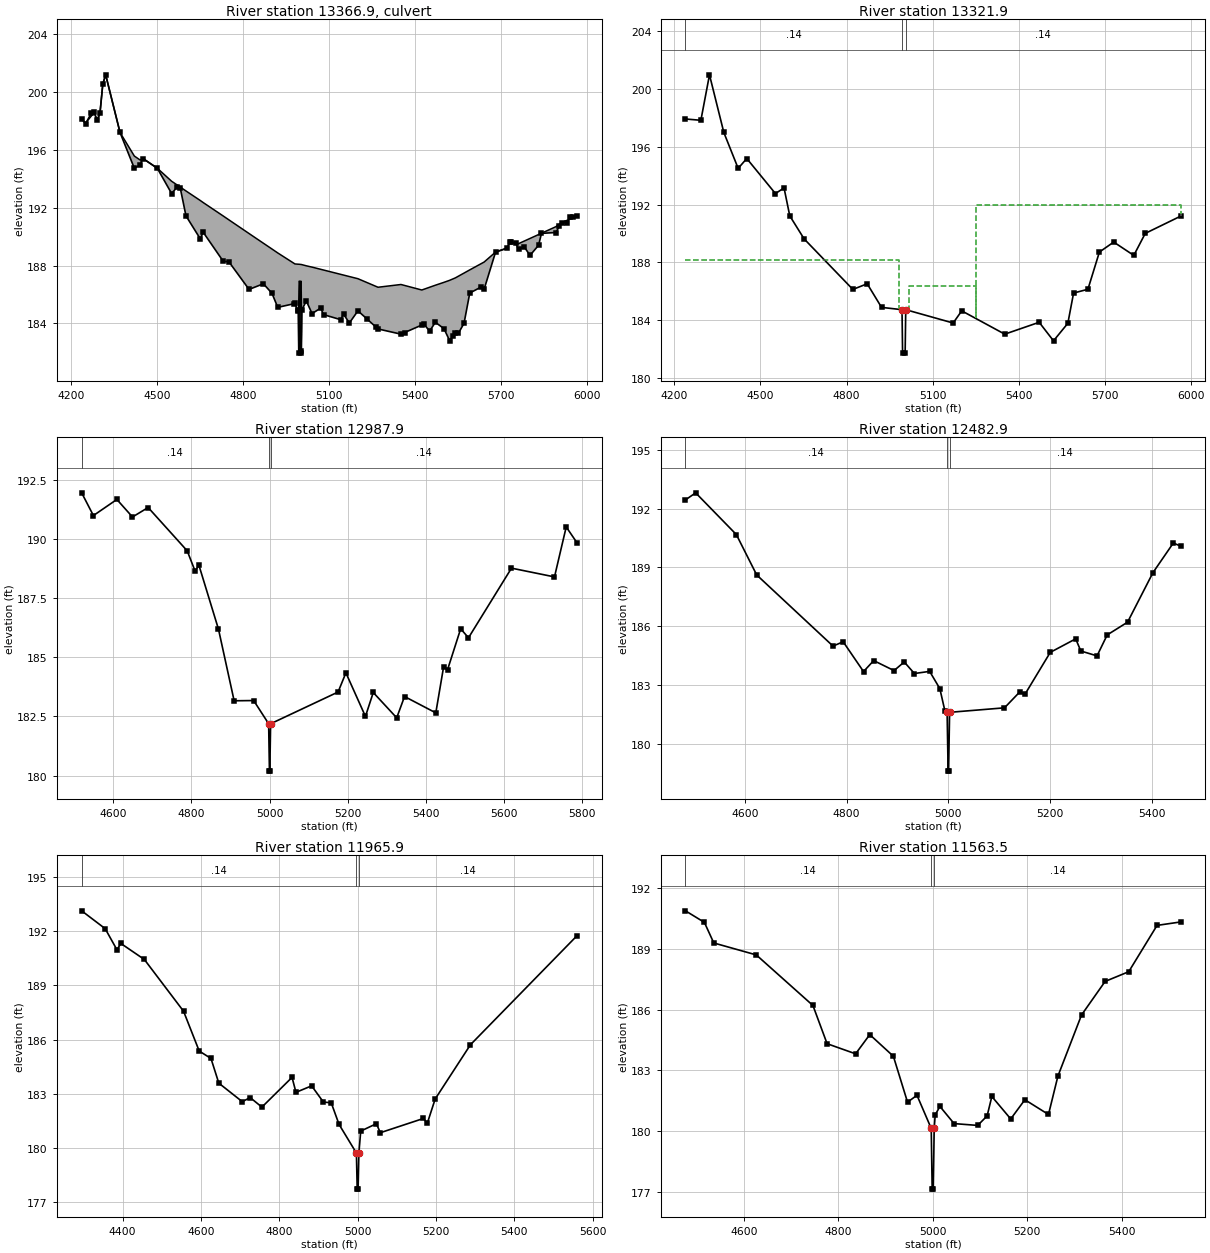
Type RM Length L Ch R = 2 ,13366.9 ,,,
BEGIN DESCRIPTION:
US Hwy 264 (Alt)-TOR
Structure ID: US Hwy 264 Alt
Approximate Survey Structure
END DESCRIPTION:
Bridge Culvert--1,0,-1,-1, 0
Deck Dist Width WeirC Skew NumUp NumDn MinLoCord MaxHiCord MaxSubmerge Is_Ogee
10,70,3,0, 60, 60, , , 0.95, 0, 1,1,,
  4238.4  4252.1  4282.1  4292.1  4302.1  4312.1  4322.1  4372.1  4422.1  4442.1
  4452.1  4502.1  4552.1  4582.1  4602.1  4652.1  4662.1  4732.1  4752.1  4822.1
  4872.1  4902.1  4922.1  4982.1  4993.5  4995.5  5004.4  5006.5  5021.8  5041.8
  5071.8  5081.8  5141.8  5151.8  5171.8  5201.8  5271.8  5351.8  5424.5  5451.8
  5471.8  5501.8  5521.8  5541.8  5551.8  5571.8  5591.8  5641.8  5681.8  5721.8
  5731.8  5751.8  5761.8  5781.8  5801.8  5831.8  5841.8  5891.8  5911.8  5965.2
  198.12  197.84  198.57  198.03   198.5  200.54  201.17  197.19  195.56  195.29
  195.39  194.72  193.82  193.42  193.15  192.49  192.35  191.42  191.15  190.21
  189.54  189.14  188.87  188.11  188.09  188.09  188.07  188.06  187.98  187.89
  187.74  187.69  187.39  187.34  187.24  187.09   186.5  186.69  186.31   186.5
  186.64  186.84  186.98  187.15  187.26  187.48   187.7  188.24  188.93   189.2
  189.62  189.55  189.51  189.69  189.87  190.14  190.23  190.68  190.96  191.41
  198.12   197.8  198.57  198.03   198.5  200.54  201.17  197.19  194.71  194.95
  195.39  194.72  192.97  193.36  191.43  189.84   190.3  188.29  188.25  186.35
  186.74  186.08  185.11  185.38  184.95  181.95  181.95  184.95  185.55  184.68
  185.06  184.61  184.26  184.64  184.03  184.87  183.62  183.26  183.89  183.47
  184.08  183.64   182.8  183.37  183.31  184.01   186.1  186.36  188.93   189.2
  189.62  189.55  189.11  189.29   188.7   189.4  190.22  190.28  190.96  191.41
  4238.4  4252.1  4282.1  4292.1  4302.1  4312.1  4322.1  4372.1  4422.1  4442.1
  4452.1  4502.1  4552.1  4582.1  4602.1  4652.1  4662.1  4732.1  4752.1  4822.1
  4872.1  4902.1  4922.1  4982.1  4993.5  4995.5  5004.4  5006.5  5021.8  5041.8
  5071.8  5081.8  5141.8  5151.8  5171.8  5201.8  5271.8  5351.8  5424.5  5451.8
  5471.8  5501.8  5521.8  5541.8  5551.8  5571.8  5591.8  5641.8  5681.8  5721.8
  5731.8  5751.8  5761.8  5781.8  5801.8  5831.8  5841.8  5891.8  5911.8  5965.2
  198.02  197.84  198.48  197.94  198.41  200.45  201.08   197.1  195.56  195.29
   195.3  194.63  193.82  193.42  193.15  192.49  192.35  191.42  191.15  190.21
  189.54  189.14  188.87  188.11  188.09  188.09  188.07  188.06  187.98  187.89
  187.74  187.69  187.39  187.34  187.24  187.09   186.5  186.69  186.31   186.5
  186.64  186.84  186.98  187.15  187.26  187.48   187.7  188.24  188.84  189.12
  189.53  189.46  189.51  189.69  189.87  190.14  190.23  190.68  190.87  191.31
  197.92   197.6  198.37  197.83   198.3  200.34  200.97  196.99  194.51  194.75
  195.19  194.52  192.77  193.16  191.23  189.64   190.1  188.09  188.05  186.15
  186.54  185.88  184.91  185.18  184.75  181.75  181.75  184.75  185.35  184.48
  184.86  184.41  184.06  184.44  183.83  184.67  183.42  183.06  183.69  183.27
  183.88  183.44   182.6  183.17  183.11  183.81   185.9  186.16  188.73     189
  189.42  189.35  188.91  189.09   188.5   189.2  190.02  190.08  190.76  191.21
BR Coef= 1 , 0 , 0 ,1.25, 0 ,,,0.8,-1,2,0,
WSPro=,,,, 1 ,,,, 0 ,,,, 0 ,,,,-1 ,-1 ,-1 , 0 , 0 , 0 , 0 , 0
Culvert=1,5,,70,0.015,0.2,1,1,2,181.95,4997.55,181.75,4997.55,Culvert #1  , 0 ,10
Culvert Bottom n=0.015
Culvert=1,5,,70,0.015,0.2,1,1,2,181.95,5002.55,181.75,5002.55,Culvert #2  , 0 ,10
Culvert Bottom n=0.015
BR U #Sta/Elev= 76
  4238.4  198.12  4252.1   197.8  4272.1  198.52  4282.1  198.57  4292.1  198.03
  4302.1   198.5  4312.1  200.54  4322.1  201.17  4372.1  197.19  4422.1  194.71
  4442.1  194.95  4452.1  195.39  4502.1  194.72  4552.1  192.97  4572.1  193.44
  4582.1  193.36  4602.1  191.43  4652.1  189.84  4662.1   190.3  4732.1  188.29
  4752.1  188.25  4822.1  186.35  4872.1  186.74  4902.1  186.08  4922.1  185.11
  4978.4  185.36  4982.1  185.38  4992.1  184.84  4993.5  184.95  4995.5  181.95
  5004.4  181.95  5004.5  182.09  5006.5  184.95  5021.8  185.55  5041.8  184.68
  5071.8  185.06  5081.8  184.61  5141.8  184.26  5151.8  184.64  5171.8  184.03
  5201.8  184.87  5234.5  184.29  5264.5  183.75  5271.8  183.62  5351.8  183.26
  5364.5  183.37  5424.5  183.89  5431.8  183.95  5451.8  183.47  5471.8  184.08
  5501.8  183.64  5521.8   182.8  5534.5  183.16  5541.8  183.37  5551.8  183.31
  5571.8  184.01  5591.8   186.1  5631.8  186.52  5641.8  186.36  5681.8  188.93
  5721.8   189.2  5731.8  189.62  5734.5  189.61  5751.8  189.55  5761.8  189.11
  5781.8  189.29  5801.8   188.7  5831.8   189.4  5841.8  190.22  5891.8  190.28
  5904.5  190.71  5911.8  190.96  5931.8  190.96  5941.8  191.36  5950.2  191.38
  5965.2  191.41
BR U #Mann= 3
  4238.4     .14  4993.5    .048  5006.5     .14
BR U Banks=4993.5,5006.5
BR D #Sta/Elev= 76
  4238.4  197.92  4252.1   197.6  4272.1  198.32  4282.1  198.37  4292.1  197.83
  4302.1   198.3  4312.1  200.34  4322.1  200.97  4372.1  196.99  4422.1  194.51
  4442.1  194.75  4452.1  195.19  4502.1  194.52  4552.1  192.77  4572.1  193.24
  4582.1  193.16  4602.1  191.23  4652.1  189.64  4662.1   190.1  4732.1  188.09
  4752.1  188.05  4822.1  186.15  4872.1  186.54  4902.1  185.88  4922.1  184.91
  4978.4  185.16  4982.1  185.18  4992.1  184.64  4993.5  184.75  4995.5  181.75
  5004.4  181.75  5004.5  181.89  5006.5  184.75  5021.8  185.35  5041.8  184.48
  5071.8  184.86  5081.8  184.41  5141.8  184.06  5151.8  184.44  5171.8  183.83
  5201.8  184.67  5234.5  184.09  5264.5  183.55  5271.8  183.42  5351.8  183.06
  5364.5  183.17  5424.5  183.69  5431.8  183.75  5451.8  183.27  5471.8  183.88
  5501.8  183.44  5521.8   182.6  5534.5  182.96  5541.8  183.17  5551.8  183.11
  5571.8  183.81  5591.8   185.9  5631.8  186.32  5641.8  186.16  5681.8  188.73
  5721.8     189  5731.8  189.42  5734.5  189.41  5751.8  189.35  5761.8  188.91
  5781.8  189.09  5801.8   188.5  5831.8   189.2  5841.8  190.02  5891.8  190.08
  5904.5  190.51  5911.8  190.76  5931.8  190.76  5941.8  191.16  5950.2  191.18
  5965.2  191.21
BR D #Mann= 3
  4238.4     .14  4993.5    .048  5006.5     .14
BR D Banks=4993.5,5006.5
BC Design=,, 0 ,, 0 ,,,,,,
BC HTab HWMax=201.18
BC Use User HTab Curves=0
BC User HTab FreeFlow(D)= 0

Type RM Length L Ch R = 1 ,13321.9 ,334,334,334
BEGIN DESCRIPTION:
Downstream Section of Bridge/Culvert/Weir
END DESCRIPTION:
#Sta/Elev= 30
  4238.4  197.91  4292.1  197.82  4322.1  200.96  4372.1  196.98  4422.1   194.5
  4452.1  195.18  4552.1  192.76  4582.1  193.15  4602.1  191.22  4652.1  189.63
  4822.1  186.14  4872.1  186.53  4922.1   184.9  4993.5  184.74  4995.5  181.74
  5004.4  181.74  5006.5  184.74  5171.8  183.82  5201.8  184.66  5351.8  183.05
  5471.8  183.87  5521.8  182.59  5571.8   183.8  5591.8  185.89  5641.8  186.15
  5681.8  188.72  5731.8  189.41  5801.8  188.49  5841.8  190.01  5965.2   191.2
#Mann= 3 ,-1 , 0
  4238.4     .14       0  4993.5    .048       0  5006.5     .14       0
#XS Ineff= 3 ,-1
    4200    4983   188.2    5017    5250   186.4    5250    6000     192
Permanent Ineff=
       F       F       F
Bank Sta=4993.5,5006.5
XS Rating Curve= 0 ,0
Exp/Cntr=0.5,0.3

Type RM Length L Ch R = 1 ,12987.9 ,505,505,505
BEGIN DESCRIPTION:
Millstone Creek 20.0
END DESCRIPTION:
#Sta/Elev= 30
  4519.2  191.94  4549.2  190.98  4609.2  191.66  4649.2  190.92  4689.2  191.32
  4789.2  189.49  4809.2  188.64  4819.2  188.88  4869.2  186.18  4909.2  183.16
  4959.2  183.17  4997.5  182.19  4999.5  180.19  5000.5  180.19  5002.5  182.19
  5175.1  183.53  5195.1  184.34  5245.1   182.5  5265.1  183.51  5325.1  182.44
  5345.1  183.34  5425.1  182.65  5445.1   184.6  5455.1  184.47  5488.7   186.2
  5508.7  185.82  5618.7  188.76  5728.7  188.39  5758.7   190.5  5785.9  189.84
#Mann= 3 , 1 , 0
  4519.2     .14       0  4997.5    .048       0  5002.5     .14       0
Bank Sta=4997.5,5002.5
XS Rating Curve= 0 ,0
Exp/Cntr=0.3,0.1

Type RM Length L Ch R = 1 ,12482.9 ,517,517,517
BEGIN DESCRIPTION:
Millstone Creek 19.5
END DESCRIPTION:
#Sta/Elev= 30
  4483.2  192.44  4503.2   192.8  4583.2  190.67  4623.2  188.61  4773.2  184.98
  4793.2   185.2  4833.2  183.68  4853.2  184.24  4893.2  183.73  4913.2  184.17
  4933.2  183.58  4963.2  183.69  4983.2  182.81  4993.2  181.67  4997.5   181.6
  4999.5   178.6  5000.4   178.6  5002.4   181.6  5110.3  181.83  5140.3  182.64
  5150.3  182.51  5200.3  184.66  5250.3  185.35  5260.3  184.73  5292.2  184.48
  5312.2  185.55  5352.2   186.2  5402.2  188.73  5442.2  190.24  5456.6  190.08
#Mann= 3 , 1 , 0
  4483.2     .14       0  4997.5    .048       0  5002.4     .14       0
Bank Sta=4997.5,5002.4
XS Rating Curve= 0 ,0
Exp/Cntr=0.3,0.1

Type RM Length L Ch R = 1 ,11965.9 ,402.4,402.4,402.4
BEGIN DESCRIPTION:
Millstone Creek 19.0
END DESCRIPTION:
#Sta/Elev= 30
  4295.6  193.14  4355.6  192.15  4385.6  190.98  4395.6  191.33  4455.6  190.44
  4555.6  187.57  4595.6  185.36  4625.6  184.95  4645.6  183.58  4705.6  182.55
  4725.6  182.78  4755.6  182.25  4832.5   183.9  4842.5  183.07  4882.5  183.43
  4912.5  182.53  4932.5  182.49  4952.5  181.29  4996.8   179.7  4998.8   177.7
  5001.1   177.7  5003.1   179.7  5007.8  180.92  5047.8  181.33  5057.8  180.83
  5167.8  181.62  5177.8  181.36  5197.8   182.7  5287.8  185.71  5559.4  191.75
#Mann= 3 , 1 , 0
  4295.6     .14       0  4996.8    .048       0  5003.1     .14       0
Bank Sta=4996.8,5003.1
XS Rating Curve= 0 ,0
Exp/Cntr=0.3,0.1

Type RM Length L Ch R = 1 ,11563.5 ,425.8,425.8,425.8
BEGIN DESCRIPTION:
Millstone Creek 18.0
END DESCRIPTION:
#Sta/Elev= 30
  4476.3  190.88  4516.3  190.31  4536.3  189.29  4626.3   188.7  4746.3   186.2
  4776.3  184.31  4836.7  183.81  4866.7  184.76  4916.7  183.69  4946.7  181.42
  4966.7  181.76  4996.9  180.12  4998.9  177.12  5001.2  177.12  5003.2  180.12
  5005.3  180.79  5015.3  181.21  5045.3  180.36  5095.3  180.27  5115.3  180.74
  5125.3   181.7  5165.3  180.59  5195.3  181.54  5245.3  180.81  5265.3  182.71
  5315.3  185.73  5365.3  187.39  5415.3  187.87  5475.3  190.16  5525.3  190.33
#Mann= 3 , 1 , 0
  4476.3     .14       0  4996.9    .048       0  5003.2     .14       0
Bank Sta=4996.9,5003.2
XS Rating Curve= 0 ,0
Exp/Cntr=0.3,0.1

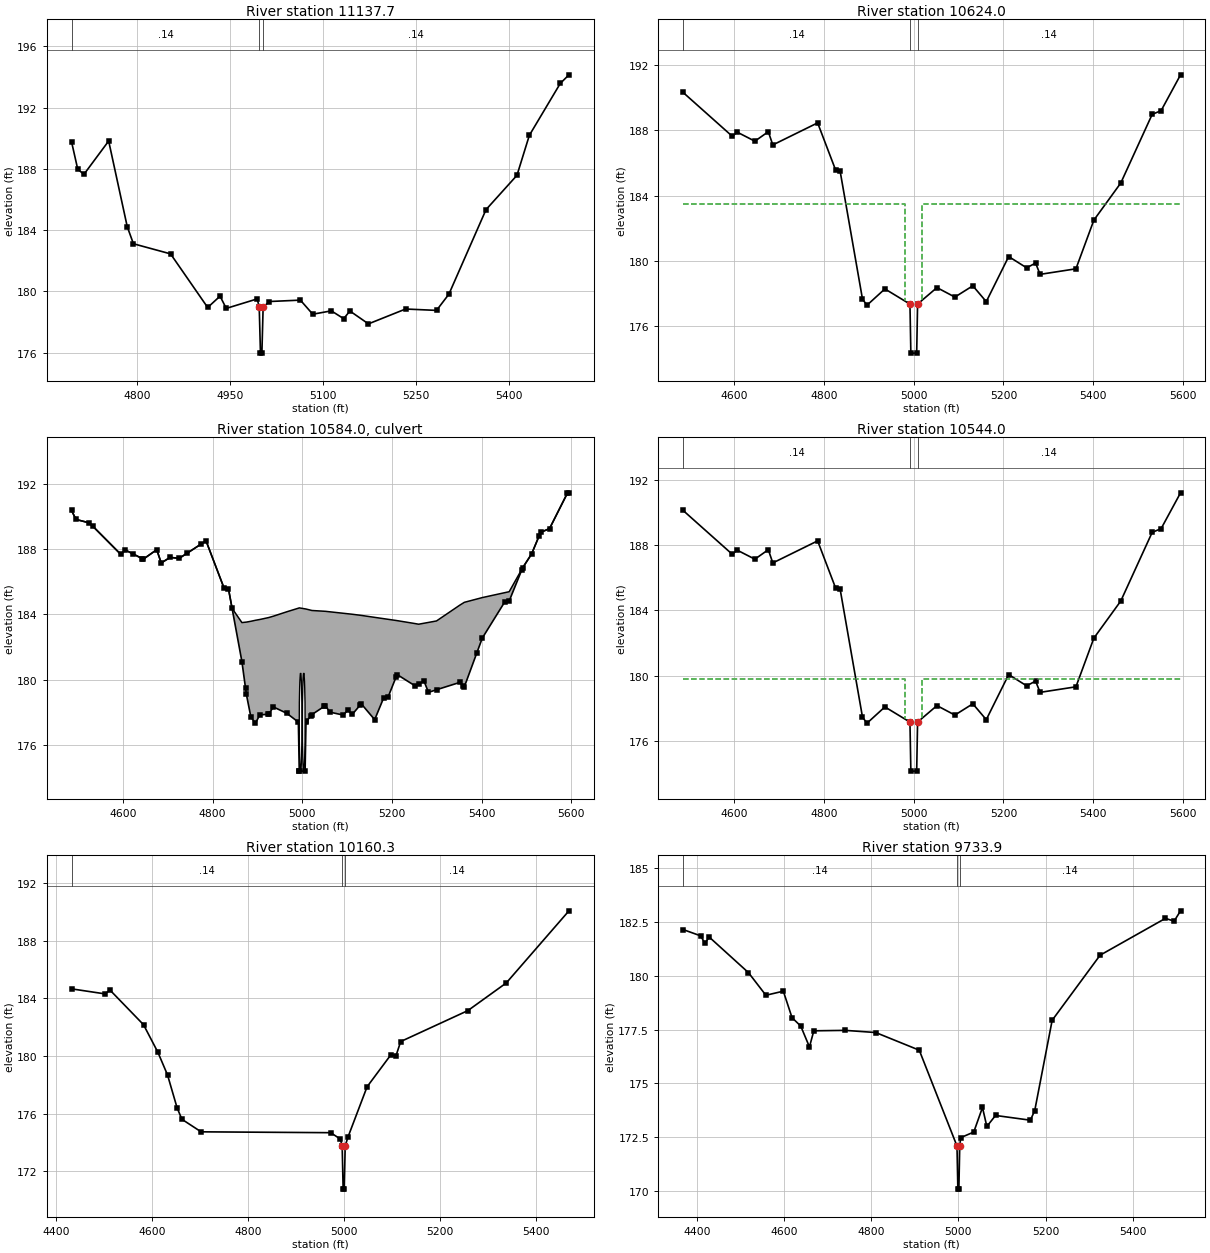
Type RM Length L Ch R = 1 ,11137.7 ,513.7,513.7,513.7
BEGIN DESCRIPTION:
Millstone Creek 17.0
END DESCRIPTION:
#Sta/Elev= 30
  4693.6  189.77  4703.6  187.98  4713.6  187.64  4753.6  189.82  4783.6  184.23
  4793.6  183.11  4853.6  182.45  4913.6  178.95  4933.6  179.69  4943.6  178.89
  4993.6  179.51  4996.9  178.97  4998.9  175.97  5001.2  175.97  5003.2  178.97
  5013.4  179.34  5063.4  179.43  5083.4  178.51  5113.4  178.73  5133.4  178.22
  5143.4  178.72  5173.4  177.88  5233.4  178.85  5283.4  178.76  5303.4  179.82
  5363.4  185.34  5413.4  187.58  5433.4  190.19  5483.4  193.58  5497.4  194.14
#Mann= 3 , 1 , 0
  4693.6     .14       0  4996.9    .048       0  5003.2     .14       0
Bank Sta=4996.9,5003.2
XS Rating Curve= 0 ,0
Exp/Cntr=0.5,0.3

Type RM Length L Ch R = 1 ,10624.0 ,80,80,80
BEGIN DESCRIPTION:
Upstream Section of Bridge/Culvert/Weir
END DESCRIPTION:
#Sta/Elev= 30
  4485.6  190.31  4595.6  187.62  4605.6  187.89  4645.6  187.33  4675.6  187.91
  4685.6   187.1  4785.6  188.45  4825.6  185.57  4835.6  185.52  4885.6  177.67
  4895.6  177.29  4935.6  178.29  4991.5  177.36  4993.5  174.36  5006.5  174.36
  5008.5  177.36  5051.7  178.37  5091.7  177.79  5131.7  178.48  5161.7  177.51
  5211.7  180.27  5251.7  179.58  5271.7  179.87  5281.7  179.18  5361.7  179.52
  5401.7   182.5  5461.7  184.77  5531.7  188.97  5551.7   189.2    5595  191.39
#Mann= 3 , 1 , 0
  4485.6     .14       0  4991.5    .048       0  5008.5     .14       0
#XS Ineff= 2 , 0
       0    4981   183.5    5019       0   183.5
Permanent Ineff=
       F       F
Bank Sta=4991.5,5008.5
XS Rating Curve= 0 ,0
Exp/Cntr=0.5,0.3

Type RM Length L Ch R = 2 ,10584.0 ,,,
BEGIN DESCRIPTION:
Green Pond Rd-TOR
Structure ID: MC - Green Pond Rd
Approximate Survey Structure
END DESCRIPTION:
Bridge Culvert--1,0,-1,-1, 0
Deck Dist Width WeirC Skew NumUp NumDn MinLoCord MaxHiCord MaxSubmerge Is_Ogee
10,60,3,0, 53, 53, , , 0.95, 0, 1,1,,
  4485.6  4495.6  4525.6  4595.6  4605.6  4645.6  4675.6  4685.6  4705.6  4725.6
  4785.6  4825.6  4835.6  4843.7  4865.6  4875.6  4885.6  4895.6  4905.6  4925.6
  4935.6  4965.6  4991.5  4993.5  5006.5  5008.5  5021.7  5051.7  5061.7  5091.7
  5101.7  5111.7  5131.7  5161.7  5181.7  5191.7  5211.7  5251.7  5259.6  5271.7
  5281.7  5299.6  5351.7  5361.7  5401.7  5451.7  5461.7  5491.7  5511.7  5531.7
  5551.7  5591.7    5595
  190.35   189.8  189.59  187.66  187.93  187.37  187.95  187.14  187.48  187.42
  188.49  185.61  185.56  184.36  183.49  183.52  183.57  183.63  183.68   183.8
  183.88  184.15  184.37  184.39  184.33  184.32  184.23  184.18  184.15  184.06
  184.03     184  183.93  183.81  183.73  183.69  183.61  183.43  183.39  183.45
   183.5  183.59  184.56  184.73  185.02  185.32  185.38  186.84  187.69  189.01
  189.24  191.42  191.43
  190.35   189.8  189.59  187.66  187.93  187.37  187.95  187.14  187.48  187.42
  188.49  185.61  185.56  184.36   181.1  179.09  177.71  177.33  177.84  177.88
  178.33  177.94   177.4   174.4   174.4   177.4  177.86  178.41  178.01  177.83
  178.13  177.87  178.52  177.55  178.88  178.94  180.31  179.62  179.73  179.91
  179.22  179.38  179.83  179.56  182.54  184.75  184.81  186.84  187.69  189.01
  189.24  191.42  191.43
  4485.6  4495.6  4525.6  4595.6  4605.6  4645.6  4675.6  4685.6  4705.6  4725.6
  4785.6  4825.6  4835.6  4843.7  4865.6  4875.6  4885.6  4895.6  4905.6  4925.6
  4935.6  4965.6  4991.5  4993.5  5006.5  5008.5  5021.7  5051.7  5061.7  5091.7
  5101.7  5111.7  5131.7  5161.7  5181.7  5191.7  5211.7  5251.7  5259.6  5271.7
  5281.7  5299.6  5351.7  5361.7  5401.7  5451.7  5461.7  5491.7  5511.7  5531.7
  5551.7  5591.7    5595
  190.25   189.7  189.49  187.57  187.84  187.28  187.86  187.05  187.39  187.33
   188.4  185.52  185.47  184.27  183.49  183.52  183.57  183.63  183.68   183.8
  183.88  184.15  184.37  184.39  184.33  184.32  184.23  184.18  184.15  184.06
  184.03     184  183.93  183.81  183.73  183.69  183.61  183.43  183.39  183.45
   183.5  183.59  184.56  184.73  185.02  185.32  185.38  186.75   187.6  188.91
  189.14  191.32  191.33
  190.15   189.6  189.39  187.46  187.73  187.17  187.75  186.94  187.28  187.22
  188.29  185.41  185.36  184.16   180.9  178.89  177.51  177.13  177.64  177.68
  178.13  177.74   177.2   174.2   174.2   177.2  177.66  178.21  177.81  177.63
  177.93  177.67  178.32  177.35  178.68  178.74  180.11  179.42  179.53  179.71
  179.02  179.18  179.63  179.36  182.34  184.55  184.61  186.64  187.49  188.81
  189.04  191.22  191.23
BR Coef= 1 , 0 , 0 ,1.25, 0 ,,,0.8,-1,2,0,
WSPro=,,,, 1 ,,,, 0 ,,,, 0 ,,,,-1 ,-1 ,-1 , 0 , 0 , 0 , 0 , 0
Culvert=1,6,,60,0.024,0.9,1,2,3,174.4,4996.51,174.2,4996.51,Culvert #1  , 0 ,10
Culvert Bottom n=0.024
Culvert=1,6,,60,0.024,0.9,1,2,3,174.4,5003.51,174.2,5003.51,Culvert #2  , 0 ,10
Culvert Bottom n=0.024
BR U #Sta/Elev= 70
  4485.6  190.35  4495.6   189.8  4525.6  189.59  4533.7  189.37  4595.6  187.66
  4605.6  187.93  4623.7  187.68  4643.7   187.4  4645.6  187.37  4675.6  187.95
  4685.6  187.14  4705.6  187.48  4725.6  187.42  4743.7  187.74  4773.7  188.28
  4785.6  188.49  4825.6  185.61  4835.6  185.56  4843.7  184.36  4865.6   181.1
  4873.7  179.47  4875.6  179.09  4885.6  177.71  4895.6  177.33  4905.6  177.84
  4923.7  177.88  4925.6  177.88  4935.6  178.33  4965.6  177.94  4991.5   177.4
  4993.5   174.4  4993.7   174.4  5006.5   174.4  5008.5   177.4  5009.6  177.44
  5019.6  177.79  5021.7  177.86  5049.6  178.37  5051.7  178.41  5061.7  178.01
  5091.7  177.83  5101.7  178.13  5111.7  177.87  5129.6  178.45  5131.7  178.52
  5161.7  177.55  5181.7  178.88  5191.7  178.94  5209.6  180.17  5211.7  180.31
  5251.7  179.62  5259.6  179.73  5271.7  179.91  5281.7  179.22  5299.6  179.38
  5351.7  179.83  5359.6  179.62  5361.7  179.56  5389.6  181.64  5401.7  182.54
  5451.7  184.75  5461.7  184.81  5489.6   186.7  5491.7  186.84  5511.7  187.69
  5528.1  188.77  5531.7  189.01  5551.7  189.24  5591.7  191.42    5595  191.43
BR U #Mann= 3
  4485.6     .14  4991.5    .048  5008.5     .14
BR U Banks=4991.5,5008.5
BR D #Sta/Elev= 70
  4485.6  190.15  4495.6   189.6  4525.6  189.39  4533.7  189.17  4595.6  187.46
  4605.6  187.73  4623.7  187.48  4643.7   187.2  4645.6  187.17  4675.6  187.75
  4685.6  186.94  4705.6  187.28  4725.6  187.22  4743.7  187.54  4773.7  188.08
  4785.6  188.29  4825.6  185.41  4835.6  185.36  4843.7  184.16  4865.6   180.9
  4873.7  179.27  4875.6  178.89  4885.6  177.51  4895.6  177.13  4905.6  177.64
  4923.7  177.68  4925.6  177.68  4935.6  178.13  4965.6  177.74  4991.5   177.2
  4993.5   174.2  4993.7   174.2  5006.5   174.2  5008.5   177.2  5009.6  177.24
  5019.6  177.59  5021.7  177.66  5049.6  178.17  5051.7  178.21  5061.7  177.81
  5091.7  177.63  5101.7  177.93  5111.7  177.67  5129.6  178.25  5131.7  178.32
  5161.7  177.35  5181.7  178.68  5191.7  178.74  5209.6  179.97  5211.7  180.11
  5251.7  179.42  5259.6  179.53  5271.7  179.71  5281.7  179.02  5299.6  179.18
  5351.7  179.63  5359.6  179.42  5361.7  179.36  5389.6  181.44  5401.7  182.34
  5451.7  184.55  5461.7  184.61  5489.6   186.5  5491.7  186.64  5511.7  187.49
  5528.1  188.57  5531.7  188.81  5551.7  189.04  5591.7  191.22    5595  191.23
BR D #Mann= 3
  4485.6     .14  4991.5    .048  5008.5     .14
BR D Banks=4991.5,5008.5
BC Design=,, 0 ,, 0 ,,,,,,
BC HTab HWMax=191.39
BC Use User HTab Curves=0
BC User HTab FreeFlow(D)= 0

Type RM Length L Ch R = 1 ,10544.0 ,383.7,383.7,383.7
BEGIN DESCRIPTION:
Downstream Section of Bridge/Culvert/Weir
END DESCRIPTION:
#Sta/Elev= 30
  4485.6  190.12  4595.6  187.43  4605.6   187.7  4645.6  187.14  4675.6  187.72
  4685.6  186.91  4785.6  188.26  4825.6  185.38  4835.6  185.33  4885.6  177.48
  4895.6   177.1  4935.6   178.1  4991.5  177.17  4993.5  174.17  5006.5  174.17
  5008.5  177.17  5051.7  178.18  5091.7   177.6  5131.7  178.29  5161.7  177.32
  5211.7  180.08  5251.7  179.39  5271.7  179.68  5281.7  178.99  5361.7  179.33
  5401.7  182.31  5461.7  184.58  5531.7  188.78  5551.7  189.01    5595   191.2
#Mann= 3 , 1 , 0
  4485.6     .14       0  4991.5    .048       0  5008.5     .14       0
#XS Ineff= 2 , 0
       0    4981   179.8    5019       0   179.8
Permanent Ineff=
       F       F
Bank Sta=4991.5,5008.5
XS Rating Curve= 0 ,0
Exp/Cntr=0.5,0.3

Type RM Length L Ch R = 1 ,10160.3 ,426.4,426.4,426.4
BEGIN DESCRIPTION:
Millstone Creek 16.0
END DESCRIPTION:
#Sta/Elev= 23
  4432.9  184.66  4502.9  184.31  4512.9  184.58  4582.9  182.17  4612.9  180.25
  4632.9  178.68  4652.9  176.39  4662.9   175.6  4702.9  174.73  4972.9  174.67
  4992.9  174.23  4996.8  173.75  4998.8  170.75  5001.1  170.75  5003.1  173.75
  5008.7  174.35  5048.7  177.86  5098.7   180.1  5108.7  179.99  5118.7     181
  5258.7  183.15  5338.7  185.07  5469.3  190.08
#Mann= 3 , 1 , 0
  4432.9     .14       0  4996.8    .048       0  5003.1     .14       0
Bank Sta=4996.8,5003.1
XS Rating Curve= 0 ,0
Exp/Cntr=0.3,0.1

Type RM Length L Ch R = 1 ,9733.9  ,380.2,380.2,380.2
BEGIN DESCRIPTION:
Millstone Creek 15.0
END DESCRIPTION:
#Sta/Elev= 30
  4368.1  182.14  4408.1  181.85  4418.1  181.51  4428.1  181.79  4518.1  180.14
  4558.1  179.09  4598.1  179.28  4618.1  178.05  4638.1  177.66  4658.1  176.69
  4668.1  177.44  4740.2  177.46  4810.2  177.36  4910.2  176.54  4996.8  172.09
  4998.8  170.09  5001.1  170.09  5003.1  172.09  5005.3  172.48  5035.3  172.74
  5055.3  173.88  5065.3     173  5085.3  173.51  5165.3  173.29  5175.3  173.74
  5215.3  177.93  5325.3  180.95  5475.3  182.66  5495.3  182.53    5510  183.01
#Mann= 3 , 1 , 0
  4368.1     .14       0  4996.8    .048       0  5003.1     .14       0
Bank Sta=4996.8,5003.1
XS Rating Curve= 0 ,0
Exp/Cntr=0.3,0.1