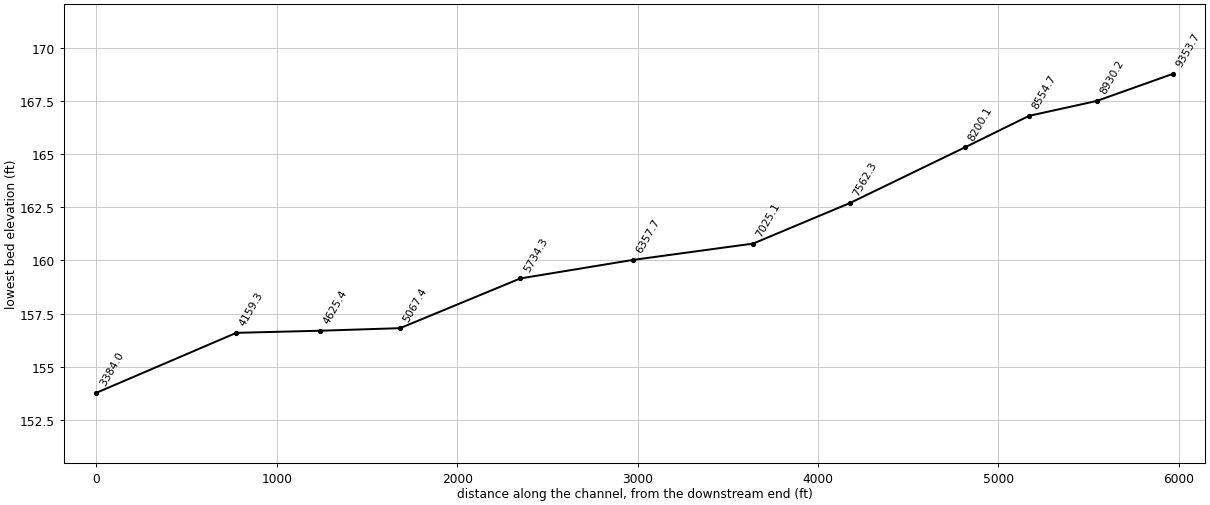
HEC-RAS study Millstone_Creek_021220.prj: Millstone Creek

--- Millstone_Creek_021220.g01 (geometry) --- (continued)

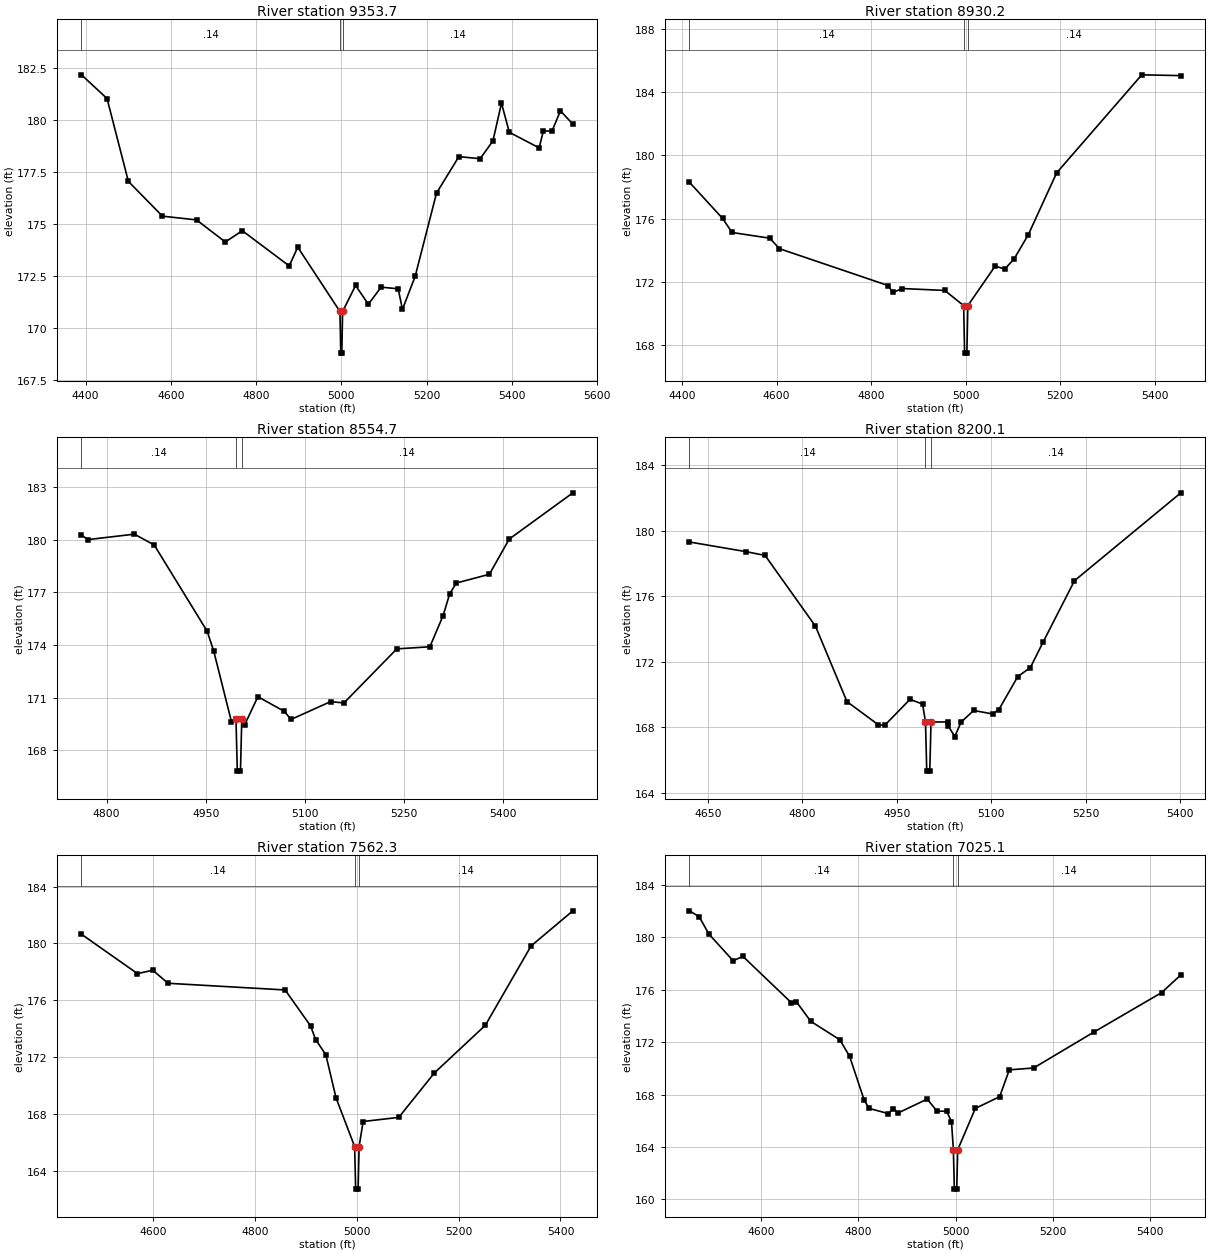
Type RM Length L Ch R = 1 ,9353.7  ,423.5,423.5,423.5
BEGIN DESCRIPTION:
Millstone Creek 14.5
END DESCRIPTION:
#Sta/Elev= 30
  4390.3  182.15  4450.3  181.01  4500.3  177.03  4580.3  175.36  4660.3  175.18
  4727.8  174.12  4767.8  174.66  4877.8  172.97  4897.8  173.87  4996.8  170.78
  4998.8  168.78  5001.1  168.78  5003.1  170.78  5033.5  172.03  5063.5  171.13
  5093.5  171.95  5133.5  171.87  5143.5  170.88  5173.5  172.48  5223.5  176.47
  5275.9  178.22  5325.9  178.12  5355.9  178.98  5375.9  180.79  5394.3  179.39
  5464.3  178.64  5474.3  179.46  5494.3  179.44  5514.3  180.42  5543.4  179.78
#Mann= 3 , 1 , 0
  4390.3     .14       0  4996.8    .048       0  5003.1     .14       0
Bank Sta=4996.8,5003.1
XS Rating Curve= 0 ,0
Exp/Cntr=0.3,0.1

Type RM Length L Ch R = 1 ,8930.2  ,375.5,375.5,375.5
BEGIN DESCRIPTION:
Millstone Creek 14.0
END DESCRIPTION:
#Sta/Elev= 20
  4415.8  178.29  4485.8  176.01  4505.8  175.12  4585.8  174.76  4605.8   174.1
  4835.8  171.77  4845.8  171.33  4865.8  171.58  4955.8  171.46  4995.6   170.5
  4997.6   167.5  5002.4   167.5  5004.4   170.5  5062.3     173  5082.3  172.81
  5102.3  173.45  5132.3  174.98  5192.3  178.89  5372.3  185.08  5454.9  185.03
#Mann= 3 , 1 , 0
  4415.8     .14       0  4995.6    .048       0  5004.4     .14       0
Bank Sta=4995.6,5004.4
XS Rating Curve= 0 ,0
Exp/Cntr=0.3,0.1

Type RM Length L Ch R = 1 ,8554.7  ,354.6,354.6,354.6
BEGIN DESCRIPTION:
Millstone Creek 13.0
END DESCRIPTION:
#Sta/Elev= 25
    4762  180.27    4772  180.02    4842  180.33    4872  179.71    4952  174.79
    4962  173.65  4988.8  169.62  4995.6   169.8  4997.6   166.8  5002.4   166.8
  5004.4   169.8  5008.8  169.45  5028.8  171.05  5068.8  170.21  5078.8  169.75
  5138.8  170.77  5158.8  170.69  5238.8  173.78  5288.8   173.9  5308.8  175.68
  5318.8  176.93  5328.8  177.54  5378.8  178.04  5408.8  180.05    5505  182.69
#Mann= 3 , 1 , 0
    4762     .14       0  4995.6    .048       0  5004.4     .14       0
Bank Sta=4995.6,5004.4
XS Rating Curve= 0 ,0
Exp/Cntr=0.3,0.1

Type RM Length L Ch R = 1 ,8200.1  ,637.8,637.8,637.8
BEGIN DESCRIPTION:
Millstone Creek 12.0
END DESCRIPTION:
#Sta/Elev= 25
    4621   179.3    4711  178.71    4741  178.48    4821  174.16    4871  169.56
    4921  168.14    4931  168.12    4971   169.7    4991  169.41  4995.6  168.32
  4997.6  165.32  5002.4  165.32  5004.4  168.32    5031  168.32  5032.1  168.05
  5042.1  167.43  5052.1  168.31  5072.1  169.02  5102.1  168.81  5112.1  169.08
  5142.1  171.09  5162.1  171.64  5182.1  173.18  5232.1  176.94  5400.9   182.3
#Mann= 3 , 1 , 0
    4621     .14       0  4995.6    .048       0  5004.4     .14       0
Bank Sta=4995.6,5004.4
XS Rating Curve= 0 ,0
Exp/Cntr=0.3,0.1

Type RM Length L Ch R = 1 ,7562.3  ,537.2,537.2,537.2
BEGIN DESCRIPTION:
Millstone Creek 11.0
END DESCRIPTION:
#Sta/Elev= 19
    4459  180.64    4569  177.87    4599  178.11    4629  177.19    4859  176.72
    4909  174.19    4919  173.23    4939  172.16    4959  169.13  4995.6   165.7
  4997.6   162.7  5002.4   162.7  5004.4   165.7  5012.3  167.46  5082.3  167.75
  5152.3  170.88  5252.3  174.23  5342.3  179.82  5424.3  182.29
#Mann= 3 , 1 , 0
    4459     .14       0  4995.6    .048       0  5004.4     .14       0
Bank Sta=4995.6,5004.4
XS Rating Curve= 0 ,0
Exp/Cntr=0.3,0.1

Type RM Length L Ch R = 1 ,7025.1  ,667.4,667.4,667.4
BEGIN DESCRIPTION:
Millstone Creek 10.0
END DESCRIPTION:
#Sta/Elev= 30
  4451.7  182.02  4471.7  181.57  4491.7  180.25  4541.7  178.21  4561.7  178.55
  4661.7  175.01  4671.7   175.1  4701.7  173.59  4761.7  172.18  4781.7  170.92
  4811.7  167.59  4821.7  166.95  4861.7  166.55  4871.7  166.94  4881.7   166.6
  4941.7  167.66  4961.7  166.74  4981.7  166.73  4991.7  165.94  4995.6  163.79
  4997.6  160.79  5002.5  160.79  5004.5  163.79  5040.9  166.95  5090.9  167.84
  5110.9  169.89  5160.9  170.03  5284.7  172.76  5424.7  175.78  5464.4  177.13
#Mann= 3 , 1 , 0
  4451.7     .14       0  4995.6    .048       0  5004.5     .14       0
Bank Sta=4995.6,5004.5
XS Rating Curve= 0 ,0
Exp/Cntr=0.3,0.1

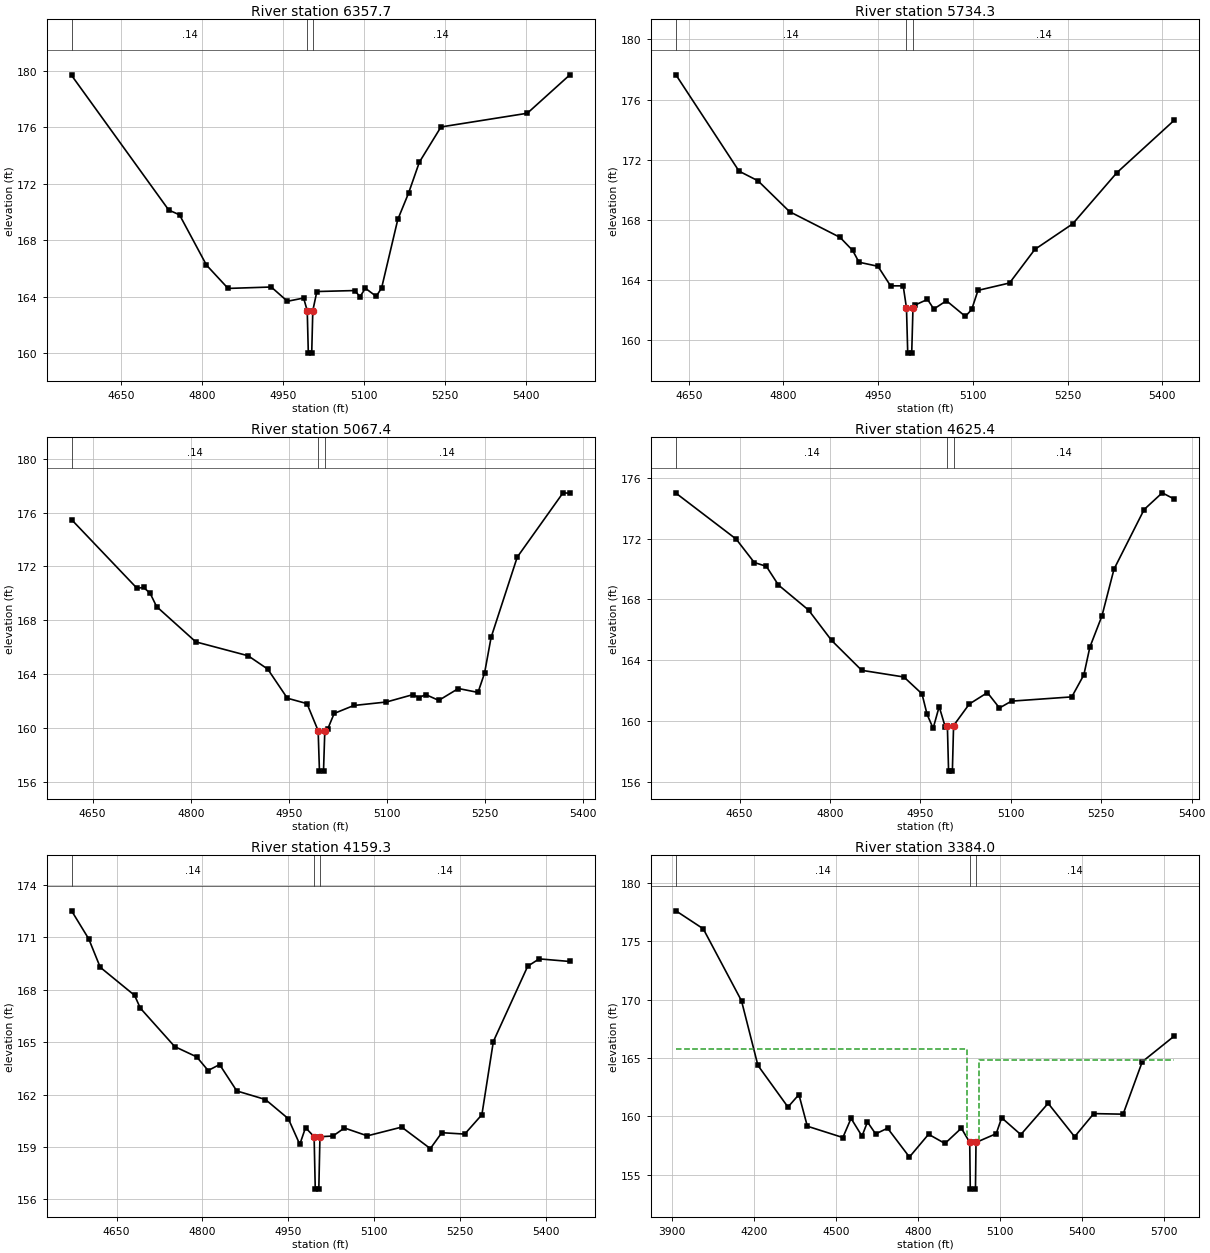
Type RM Length L Ch R = 1 ,6357.7  ,623.4,623.4,623.4
BEGIN DESCRIPTION:
Millstone Creek 9.0
END DESCRIPTION:
#Sta/Elev= 24
  4558.1  179.68  4738.1  170.15  4758.1  169.81  4808.1  166.25  4848.1   164.6
  4928.1   164.7  4958.1  163.69  4988.1  163.92  4994.8  163.02  4996.8  160.02
  5003.1  160.02  5005.1  163.02  5012.6  164.38  5082.6  164.45  5092.6  164.02
  5102.6  164.61  5122.6  164.04  5132.6  164.63  5162.6  169.48  5182.6  171.35
  5202.6  173.54  5242.6  176.03  5402.6     177  5481.5  179.72
#Mann= 3 , 1 , 0
  4558.1     .14       0  4994.8    .048       0  5005.1     .14       0
Bank Sta=4994.8,5005.1
XS Rating Curve= 0 ,0
Exp/Cntr=0.3,0.1

Type RM Length L Ch R = 1 ,5734.3  ,666.9,666.9,666.9
BEGIN DESCRIPTION:
Millstone Creek 8.0
END DESCRIPTION:
#Sta/Elev= 26
  4629.7  177.64  4729.7  171.24  4759.7   170.6  4809.7  168.55  4889.7  166.84
  4909.7  165.97  4919.7  165.19  4949.7  164.92  4969.7  163.62  4989.7  163.62
  4994.9  162.15  4996.9  159.15  5003.2  159.15  5005.2  162.15  5008.2  162.34
  5028.2  162.72  5038.2  162.08  5058.2  162.63  5088.2  161.59  5098.2  162.05
  5108.2  163.32  5158.2  163.81  5198.2  166.04  5258.2  167.74  5328.2  171.14
    5419  174.62
#Mann= 3 , 1 , 0
  4629.7     .14       0  4994.9    .048       0  5005.2     .14       0
Bank Sta=4994.9,5005.2
XS Rating Curve= 0 ,0
Exp/Cntr=0.3,0.1

Type RM Length L Ch R = 1 ,5067.4  ,442,442,442
BEGIN DESCRIPTION:
Millstone Creek 7.0
END DESCRIPTION:
#Sta/Elev= 29
  4617.8  175.47  4717.8  170.38  4727.8  170.44  4737.8  170.02  4747.8  169.02
  4807.8   166.4  4887.8  165.37  4917.8  164.38  4947.8  162.22  4977.8  161.82
  4994.9  159.81  4996.9  156.81  5003.1  156.81  5005.1  159.81  5009.4  159.92
  5019.4  161.09  5049.4  161.68  5099.4  161.94  5139.4  162.48  5149.4  162.27
  5159.4  162.49  5179.4  162.06  5209.4  162.94  5239.4  162.65  5249.4  164.08
  5259.4  166.73  5299.4  172.69  5369.4  177.46  5379.9  177.43
#Mann= 3 , 1 , 0
  4617.8     .14       0  4994.9    .048       0  5005.1     .14       0
Bank Sta=4994.9,5005.1
XS Rating Curve= 0 ,0
Exp/Cntr=0.3,0.1

Type RM Length L Ch R = 1 ,4625.4  ,466.1,466.1,466.1
BEGIN DESCRIPTION:
Millstone Creek 6.0
END DESCRIPTION:
#Sta/Elev= 30
  4544.5     175  4644.5  171.97  4674.5  170.43  4694.5  170.18  4714.5  168.95
  4764.5   167.3  4802.7   165.3  4852.7  163.33  4922.7  162.89  4952.7  161.78
  4961.2  160.42  4971.2  159.51  4981.2  160.94  4991.2  159.61  4994.8  159.69
  4996.8  156.69  5003.1  156.69  5005.1  159.69  5031.2  161.11  5061.2  161.86
  5081.2  160.85  5101.2   161.3  5201.2  161.58  5221.2  163.03  5231.2  164.86
  5251.2  166.91  5271.2  169.99  5321.2  173.92  5351.2  175.02  5371.1  174.61
#Mann= 3 , 1 , 0
  4544.5     .14       0  4994.8    .048       0  5005.1     .14       0
Bank Sta=4994.8,5005.1
XS Rating Curve= 0 ,0
Exp/Cntr=0.3,0.1

Type RM Length L Ch R = 1 ,4159.3  ,775.3,775.3,775.3
BEGIN DESCRIPTION:
Millstone Creek 5.0
END DESCRIPTION:
#Sta/Elev= 30
  4571.5  172.52  4601.5  170.91  4621.5  169.29  4681.5  167.68  4691.5  166.95
  4751.5  164.75  4789.9  164.16  4809.9  163.38  4829.9  163.72  4859.9  162.21
  4909.9  161.72  4949.9  160.62  4969.9  159.15  4979.9  160.11  4994.9  159.59
  4996.9  156.59  5003.1  156.59  5005.1  159.59  5027.8  159.63  5047.8  160.09
  5087.8  159.64  5147.8  160.14  5197.8  158.91  5217.8  159.82  5257.8  159.74
  5287.8  160.85  5307.8  165.04  5367.8  169.35  5387.8  169.77  5441.4  169.62
#Mann= 3 , 1 , 0
  4571.5     .14       0  4994.9    .048       0  5005.1     .14       0
Bank Sta=4994.9,5005.1
XS Rating Curve= 0 ,0
Exp/Cntr=0.5,0.3

Type RM Length L Ch R = 1 ,3384.0  ,260,260,260
BEGIN DESCRIPTION:
Upstream Section of Bridge/Culvert/Weir
END DESCRIPTION:
#Sta/Elev= 30
  3913.5  177.61  4013.5  176.07  4153.5   169.9  4213.5  164.37  4323.5   160.8
  4363.5  161.87  4394.3  159.16  4524.3  158.19  4554.3  159.83  4594.3  158.31
  4614.3  159.52  4644.3   158.5  4687.9  158.99  4767.9  156.52  4837.9  158.47
  4897.9  157.68  4957.9  158.99  4988.5  157.77  4990.5  153.77  5009.5  153.77
  5011.5  157.77  5085.4  158.52  5105.4  159.88  5175.4  158.44  5275.4  161.12
  5372.3  158.26  5442.3  160.24  5549.7  160.19  5619.7  164.68  5736.7  166.88
#Mann= 3 ,-1 , 0
  3913.5     .14       0  4988.5    .048       0  5011.5     .14       0
#XS Ineff= 2 , 0
       0    4978   165.8    5022       0   164.8
Permanent Ineff=
       F       F
Bank Sta=4988.5,5011.5
XS Rating Curve= 0 ,0
Exp/Cntr=0.5,0.3