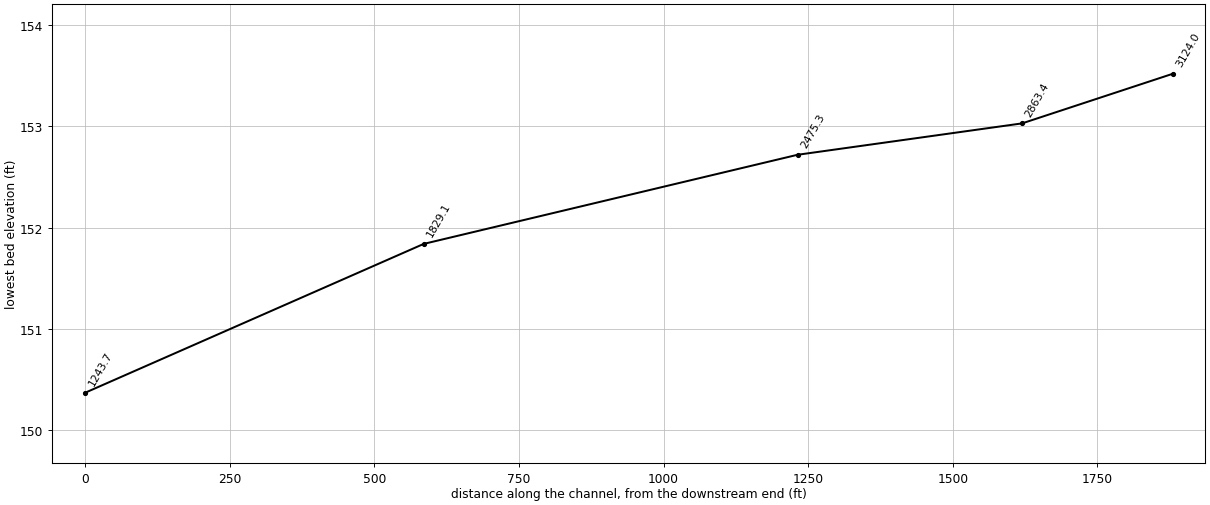
HEC-RAS study Millstone_Creek_021220.prj: Millstone Creek

--- Millstone_Creek_021220.g01 (geometry) --- (continued)

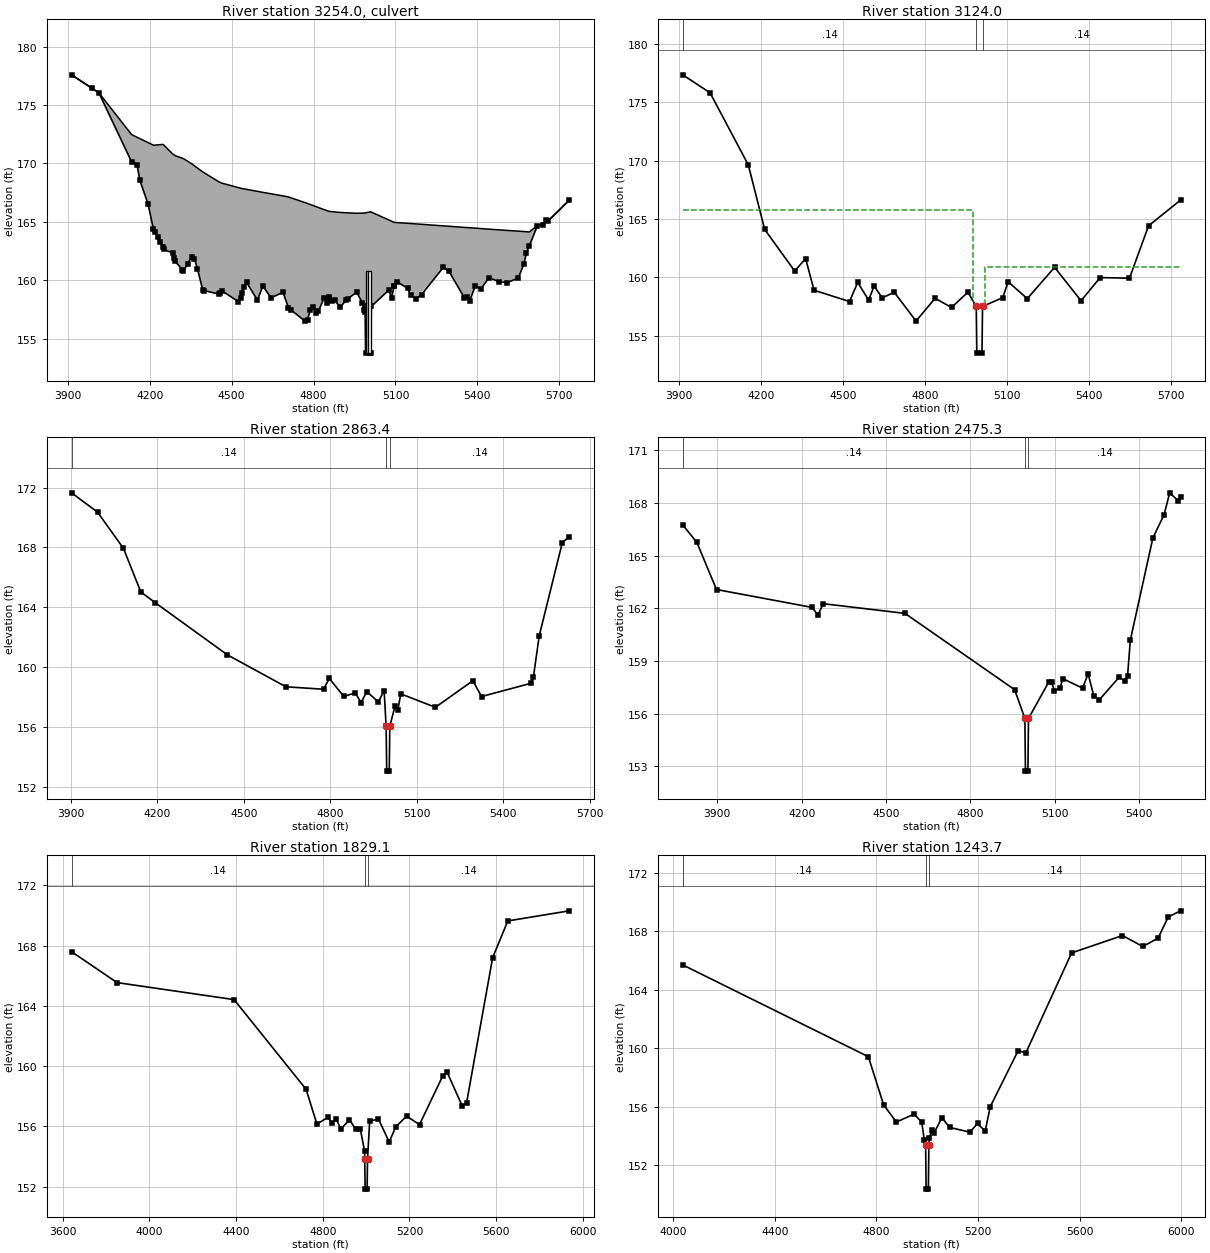
Type RM Length L Ch R = 2 ,3254.0  ,,,
BEGIN DESCRIPTION:
US Hwy 264-TOR
Structure ID: MC - US 264
Approximate Survey Structure
END DESCRIPTION:
Bridge Culvert--1,0,-1,-1, 0
Deck Dist Width WeirC Skew NumUp NumDn MinLoCord MaxHiCord MaxSubmerge Is_Ogee
10,240,3,0, 60, 60, , , 0.95, 0, 1,1,,
  3913.5  4013.5  4133.5  4153.5  4163.5  4193.5  4213.5    4249  4283.5  4293.5
  4323.5  4353.5  4363.5  4394.3  4454.3  4464.3  4524.3  4534.3  4544.3  4554.3
  4594.3  4614.3  4644.3  4687.9  4707.9  4767.9  4777.9  4787.9  4797.9  4807.9
  4817.9  4837.9  4847.9  4857.9  4897.9  4957.9  4987.9  4988.5  4990.5  5009.5
  5011.5  5075.4  5085.4  5095.4  5105.4  5145.4  5175.4  5275.4  5295.4  5352.3
  5372.3  5392.3  5412.3  5442.3  5509.7  5549.7  5589.5  5619.7  5659.7  5736.7
  177.59  176.05  172.47  172.24  172.13  171.79  171.56  171.63  170.82  170.66
  170.41  169.97   169.8  169.27  168.41  168.31  167.93  167.87  167.82  167.78
  167.61  167.52   167.4  167.22  167.13  166.65  166.57  166.48   166.4  166.31
  166.22  166.05  165.97  165.89   165.8  165.73  165.75  165.75  165.77  165.86
  165.83  165.16  165.05  164.95  164.93  164.87  164.82  164.65  164.62  164.52
  164.49  164.46  164.42  164.37  164.26   164.2  164.13  164.66  165.09  166.86
  177.59  176.05  170.13  169.88  168.56  166.54  164.35  162.82  162.32   161.6
  160.78     162  161.85  159.14   158.8  159.08  158.17  158.46  159.42  159.81
  158.29   159.5  158.48  158.97  157.63   156.5  156.63  157.43  157.68   157.2
  157.35  158.45  158.05  158.56  157.66  158.97  157.28  157.75  153.75  153.75
  157.75  159.15   158.5  159.49  159.86  159.29  158.42   161.1  160.78  158.49
  158.24  159.52  159.22  160.22   159.8  160.17  162.89  164.66  165.09  166.86
  3913.5  4013.5  4133.5  4153.5  4163.5  4193.5  4213.5    4249  4283.5  4293.5
  4323.5  4353.5  4363.5  4394.3  4454.3  4464.3  4524.3  4534.3  4544.3  4554.3
  4594.3  4614.3  4644.3  4687.9  4707.9  4767.9  4777.9  4787.9  4797.9  4807.9
  4817.9  4837.9  4847.9  4857.9  4897.9  4957.9  4987.9  4988.5  4990.5  5009.5
  5011.5  5075.4  5085.4  5095.4  5105.4  5145.4  5175.4  5275.4  5295.4  5352.3
  5372.3  5392.3  5412.3  5442.3  5509.7  5549.7  5589.5  5619.7  5659.7  5736.7
  177.47  175.94  172.47  172.24  172.13  171.79  171.56  171.63  170.82  170.66
  170.41  169.97   169.8  169.27  168.41  168.31  167.93  167.87  167.82  167.78
  167.61  167.52   167.4  167.22  167.13  166.65  166.57  166.48   166.4  166.31
  166.22  166.05  165.97  165.89   165.8  165.73  165.75  165.75  165.77  165.86
  165.83  165.16  165.05  164.95  164.93  164.87  164.82  164.65  164.62  164.52
  164.49  164.46  164.42  164.37  164.26   164.2  164.13  164.54  164.97  166.74
  177.34   175.8  169.88  169.63  168.31  166.29   164.1  162.57  162.07  161.35
  160.53  161.75   161.6  158.89  158.55  158.83  157.92  158.21  159.17  159.56
  158.04  159.25  158.23  158.72  157.38  156.25  156.38  157.18  157.43  156.95
   157.1   158.2   157.8  158.31  157.41  158.72  157.03   157.5   153.5   153.5
   157.5   158.9  158.25  159.24  159.61  159.04  158.17  160.85  160.53  158.24
  157.99  159.27  158.97  159.97  159.55  159.92  162.64  164.41  164.84  166.61
BR Coef= 1 , 0 , 0 ,1.25, 0 ,,,0.8,-1,2,0,
WSPro=,,,, 1 ,,,, 0 ,,,, 0 ,,,,-1 ,-1 ,-1 , 0 , 0 , 0 , 0 , 0
Culvert=2,7,9,240,0.015,0.4,1,8,1,153.75,4994.96,153.5,4994.96,Culvert #1  , 0 ,10
Culvert Bottom n=0.015
Culvert=2,7,9,240,0.015,0.4,1,8,1,153.75,5004.96,153.5,5004.96,Culvert #2  , 0 ,10
Culvert Bottom n=0.015
BR U #Sta/Elev= 90
  3913.5  177.59    3989  176.43  4013.5  176.05  4133.5  170.13  4153.5  169.88
  4163.5  168.56  4193.5  166.54  4213.5  164.35    4219  164.11    4229  163.68
    4239  163.25    4249  162.82  4253.5  162.63  4283.5  162.32    4289  161.92
  4293.5   161.6    4319   160.9  4323.5  160.78    4339  161.41  4353.5     162
  4363.5  161.85  4374.3  160.99  4394.3  159.14    4399  159.11  4454.3   158.8
    4459  158.93  4464.3  159.08  4524.3  158.17  4534.3  158.46    4539  158.91
  4544.3  159.42  4554.3  159.81  4594.3  158.29  4614.3   159.5  4644.3  158.48
  4687.9  158.97  4707.9  157.63  4715.8  157.48  4767.9   156.5  4777.9  156.63
  4787.9  157.43  4797.9  157.68  4807.9   157.2  4817.9  157.35  4837.9  158.45
  4847.9  158.05  4855.8  158.45  4857.9  158.56  4867.9  158.18  4877.9  158.26
  4897.9  157.66  4917.9  158.28  4925.8  158.42  4957.9  158.97  4977.9  158.08
  4985.8  157.45  4987.9  157.28  4988.5  157.75  4990.5  153.75  5005.3  153.75
  5009.5  153.75  5011.5  157.75  5075.4  159.15  5085.4   158.5  5095.3  159.48
  5095.4  159.49  5105.4  159.86  5145.4  159.29  5155.4  158.69  5175.4  158.42
  5195.4  158.77  5275.4   161.1  5295.4  160.78  5352.3  158.49  5362.3  158.57
  5372.3  158.24  5392.3  159.52  5412.3  159.22  5442.3  160.22  5479.7  159.86
  5509.7   159.8  5549.7  160.17  5569.7  161.35  5579.7  162.32  5589.5  162.89
  5619.7  164.66  5639.7  164.73  5649.7  165.12  5659.7  165.09  5736.7  166.86
BR U #Mann= 3
  3913.5     .14  4988.5    .048  5011.5     .14
BR U Banks=4988.5,5011.5
BR D #Sta/Elev= 90
  3913.5  177.34    3989  176.18  4013.5   175.8  4133.5  169.88  4153.5  169.63
  4163.5  168.31  4193.5  166.29  4213.5   164.1    4219  163.86    4229  163.43
    4239     163    4249  162.57  4253.5  162.38  4283.5  162.07    4289  161.67
  4293.5  161.35    4319  160.65  4323.5  160.53    4339  161.16  4353.5  161.75
  4363.5   161.6  4374.3  160.74  4394.3  158.89    4399  158.86  4454.3  158.55
    4459  158.68  4464.3  158.83  4524.3  157.92  4534.3  158.21    4539  158.66
  4544.3  159.17  4554.3  159.56  4594.3  158.04  4614.3  159.25  4644.3  158.23
  4687.9  158.72  4707.9  157.38  4715.8  157.23  4767.9  156.25  4777.9  156.38
  4787.9  157.18  4797.9  157.43  4807.9  156.95  4817.9   157.1  4837.9   158.2
  4847.9   157.8  4855.8   158.2  4857.9  158.31  4867.9  157.93  4877.9  158.01
  4897.9  157.41  4917.9  158.03  4925.8  158.17  4957.9  158.72  4977.9  157.83
  4985.8   157.2  4987.9  157.03  4988.5   157.5  4990.5   153.5  5005.3   153.5
  5009.5   153.5  5011.5   157.5  5075.4   158.9  5085.4  158.25  5095.3  159.23
  5095.4  159.24  5105.4  159.61  5145.4  159.04  5155.4  158.44  5175.4  158.17
  5195.4  158.52  5275.4  160.85  5295.4  160.53  5352.3  158.24  5362.3  158.32
  5372.3  157.99  5392.3  159.27  5412.3  158.97  5442.3  159.97  5479.7  159.61
  5509.7  159.55  5549.7  159.92  5569.7   161.1  5579.7  162.07  5589.5  162.64
  5619.7  164.41  5639.7  164.48  5649.7  164.87  5659.7  164.84  5736.7  166.61
BR D #Mann= 3
  3913.5     .14  4988.5    .048  5011.5     .14
BR D Banks=4988.5,5011.5
BC Design=,, 0 ,, 0 ,,,,,,
BC HTab HWMax=177.61
BC Use User HTab Curves=0
BC User HTab FreeFlow(D)= 0

Type RM Length L Ch R = 1 ,3124.0  ,260.6,260.6,260.6
BEGIN DESCRIPTION:
Downstream Section of Bridge/Culvert/Weir
END DESCRIPTION:
#Sta/Elev= 30
  3913.5  177.36  4013.5  175.82  4153.5  169.65  4213.5  164.12  4323.5  160.55
  4363.5  161.62  4394.3  158.91  4524.3  157.94  4554.3  159.58  4594.3  158.06
  4614.3  159.27  4644.3  158.25  4687.9  158.74  4767.9  156.27  4837.9  158.22
  4897.9  157.43  4957.9  158.74  4988.5  157.52  4990.5  153.52  5009.5  153.52
  5011.5  157.52  5085.4  158.27  5105.4  159.63  5175.4  158.19  5275.4  160.87
  5372.3  158.01  5442.3  159.99  5549.7  159.94  5619.7  164.43  5736.7  166.63
#Mann= 3 , 1 , 0
  3913.5     .14       0  4988.5    .048       0  5011.5     .14       0
#XS Ineff= 2 , 0
       0    4978   165.8    5022       0   160.9
Permanent Ineff=
       F       F
Bank Sta=4988.5,5011.5
XS Rating Curve= 0 ,0
Exp/Cntr=0.5,0.3

Type RM Length L Ch R = 1 ,2863.4  ,388.1,388.1,388.1
BEGIN DESCRIPTION:
Millstone Creek 4.0
END DESCRIPTION:
#Sta/Elev= 30
  3903.3  171.65  3993.3  170.36  4083.3  167.93  4143.3  165.02  4193.3   164.3
  4443.3  160.81  4646.7  158.67  4776.7  158.51  4796.7  159.23  4846.7  158.03
  4886.7  158.26  4906.7  157.62  4926.7  158.35  4966.7  157.66  4986.7  158.42
  4993.6  156.03  4995.6  153.03  5004.4  153.03  5006.4  156.03  5024.3  157.38
  5034.3  157.12  5044.3   158.2  5164.3   157.3  5294.3  159.08  5324.3  158.02
  5494.3   158.9  5504.3  159.35  5524.3  162.09  5604.3  168.32  5628.6  168.72
#Mann= 3 , 1 , 0
  3903.3     .14       0  4993.6    .048       0  5006.4     .14       0
Bank Sta=4993.6,5006.4
XS Rating Curve= 0 ,0
Exp/Cntr=0.3,0.1

Type RM Length L Ch R = 1 ,2475.3  ,646.2,646.2,646.2
BEGIN DESCRIPTION:
Millstone Creek 3.0
END DESCRIPTION:
#Sta/Elev= 30
  3777.4  166.75  3827.4  165.76  3897.4  163.07  4237.4  162.05  4257.4  161.61
  4277.4  162.26  4567.3  161.71  4957.3  157.36  4993.6  155.72  4995.6  152.72
  5004.4  152.72  5006.4  155.72  5078.5   157.8  5088.5  157.79  5098.5  157.31
  5118.5  157.46  5128.5  157.99  5198.5  157.45  5218.5  158.26  5238.5  157.02
  5258.5  156.79  5328.5  158.07  5348.5  157.87  5358.5  158.13  5368.5  160.19
  5448.5     166  5488.5  167.34  5508.5  168.58  5538.5  168.13  5546.9  168.35
#Mann= 3 , 1 , 0
  3777.4     .14       0  4993.6    .048       0  5006.4     .14       0
Bank Sta=4993.6,5006.4
XS Rating Curve= 0 ,0
Exp/Cntr=0.3,0.1

Type RM Length L Ch R = 1 ,1829.1  ,585.4,585.4,585.4
BEGIN DESCRIPTION:
Millstone Creek 2.0
END DESCRIPTION:
#Sta/Elev= 30
  3640.7  167.59  3850.7  165.54  4390.7  164.41    4723  158.46    4773  156.15
    4823   156.6    4843  156.23    4863  156.47    4883  155.82    4923  156.44
    4953   155.8    4973  155.84    4993  154.35  4993.6  153.84  4995.6  151.84
  5004.5  151.84  5006.5  153.84  5016.4  156.34  5056.4   156.5  5106.4  154.97
  5136.4  155.96  5186.4  156.68  5246.4  156.12  5353.8  159.36  5373.8  159.59
  5443.8  157.34  5463.8  157.58  5583.8  167.19  5653.8  169.63  5937.7   170.3
#Mann= 3 , 1 , 0
  3640.7     .14       0  4993.6    .048       0  5006.5     .14       0
Bank Sta=4993.6,5006.5
XS Rating Curve= 0 ,0
Exp/Cntr=0.3,0.1

Type RM Length L Ch R = 1 ,1243.7  ,0,0,0
BEGIN DESCRIPTION:
Millstone Creek 1.0 (Tie-in to Effective Study)
END DESCRIPTION:
#Sta/Elev= 28
  4038.4  165.71  4768.4  159.43  4828.4  156.14  4878.4  154.96  4948.4   155.5
  4978.4  154.95  4988.4  153.72  4993.6  153.37  4995.6  150.37  5004.4  150.37
  5006.4  153.37  5007.8  153.85  5017.8  154.44  5027.8  154.24  5057.8  155.27
  5087.8  154.59  5167.8  154.27  5197.8  154.86  5227.8  154.34  5247.8  156.01
  5357.8  159.85  5387.8  159.69  5567.8  166.53  5767.8  167.72  5847.8  166.97
  5907.8  167.54  5947.8  168.99  5996.2  169.41
#Mann= 3 , 1 , 0
  4038.4     .14       0  4993.6    .048       0  5006.4     .14       0
Bank Sta=4993.6,5006.4
XS Rating Curve= 0 ,0
Exp/Cntr=0.3,0.1

Chan Stop Cuts=-1
Use User Specified Reach Order=0