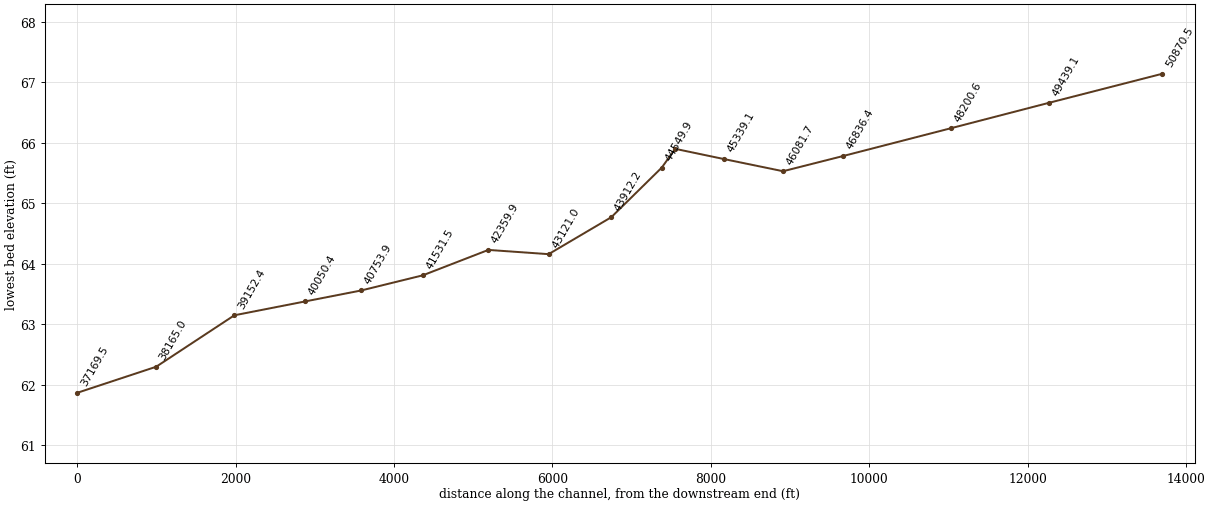
--- Toisnot_Swamp_DS_021220.prj (project) ---

Proj Title=Toisnot Swamp DS
Current Plan=p02
Default Exp/Contr=0.3,0.1
English Units
Geom File=g01
Flow File=f01
Flow File=f02
Plan File=p01
Plan File=p02
Y Axis Title=Elevation
X Axis Title(PF)=Main Channel Distance
X Axis Title(XS)=Station
BEGIN DESCRIPTION:
NEUSE RIVER BASIN
Little Contentnea Creek Sub-basin
TOISNOT SWAMP DS
(Flood Hazard, Floodway) Model
Prepared by: Andrew J. Bonner   Date: 11/7/2002
Watershed Concepts
3333 Regency Pkwy
Cary, North Carolina 27511
END DESCRIPTION:
DSS Export Rating Curves= 0
DSS Export Rating Curve Sorted= 0
DSS Export Volume Flow Curves= 0
DXF OffsetX= 0
DXF OffsetY= 0
DXF ScaleX= 1
DXF ScaleY= 10

--- Toisnot_Swamp_DS_021220.p02 (plan) ---

Plan Title=Multi Profile
Program Version=4.00
Short Identifier=Multi Profile
Geom File=g01
Flow File=f02
Subcritical Flow
K Sum by GR= 0
Std Step Tol= 0.01
Critical Tol= 0.01
Num of Std Step Trials= 20
Max Error Tol= 0.3
Flow Tol Ratio= 0.001
Split Flow NTrial= 30
Split Flow Tol= 0.02
Split Flow Ratio= 0.02
Log Output Level= 0
Friction Slope Method= 1
Unsteady Friction Slope Method= 2
Unsteady Bridges Friction Slope Method= 1
Parabolic Critical Depth
Global Vel Dist= 0 , 0 , 0
Global Log Level= 0
CheckData=True
Encroach Param=-1 ,10,10, 2
Computation Interval=1HOUR
Output Interval=1HOUR
Run HTab= 0
Run UNet= 0
Run PostProcess= 0
Run WQNet= 0
UNET Theta= 1
UNET Theta Warmup= 1
UNET ZTol= 0.02
UNET ZSATol= 0.1
UNET MxIter= 20
UNET MaxInSteps= 20
UNET DtIC= 0
UNET DtMin= 0
UNET MaxCRTS= 20
UNET WFStab= 2
UNET SFStab= 1
UNET WFX= 1
UNET SFX= 1
UNET DSS MLevel= 4
UNET DZMax Abort= 100
UNET Convert EG Bridges=-1
UNET Use Existing IB Tables=-1
UNET Froude Reduction=False
UNET Froude Limit= 1
UNET Froude Power= 10
UNET Time Slicing=0,0, 5
Instantaneous Interval=1HOUR
Write IC File= 0
Echo Input=False
Echo Output=False
Write Detailed= 0
Detailed Automatic Start=False, 10
WQ ULTIMATE=-1
WQ Max Comp Step=1HOUR
WQ Output Interval=15MIN
WQ Output Selected Increments= 0
WQ Output face flow=0
WQ Output face velocity=0
WQ Output face area=0
WQ Output face dispersion=0
WQ Output cell volume=0
WQ Output cell surface area=0
WQ Output cell continuity=0
WQ Output face conc=0
WQ Output face dconc_dx=0
WQ Output face courant=0
WQ Output face peclet=0
WQ Output face adv mass=0
WQ Output face disp mass=0
WQ Output cell mass=0
WQ Output cell source sink temp=0
WQ Output cell source sink nsm=0
WQ Output MaxMinRange=-1
WQ Daily Max Min Mean=-1
WQ Daily Range=0
WQ Daily Time=0
WQ Create Restart=0
WQ Fixed Restart=0
WQ System Summary=False
Sorting and Armoring Iterations= 10
XS Update Threshold= 0.02
Hydraulics Update Threshold= 0.02
Energy Slope Method= 1
Volume Change Method= 0
XS Weighting Method= 0
Number of US Weighted Cross Sections= 1
Number of DS Weighted Cross Sections= 1
Upstream XS Weight=0.25
Main XS Weight=0.5
Downstream XS Weight=0.25
Number of DS XS's Weighted with US Boundary= 1
Upstream Boundary Weight= 1
Weight of XSs Associated with US Boundary= 0
Number of US XS's Weighted with DS Boundary= 1
Downstream Boundary Weight= 0.5
Weight of XSs Associated with DS Boundary= 0.5
Sediment Output Level= 4
Mass or Volume Output= 0
Output Increment Type= 1
Profile and TS Output Increment= 10
XS Output Flag= 0
XS Output Increment= 10
Disregard all LS=0
Disregard all Conn=0
Disregard all Breaches=0
Disregard all Pumps=0

--- Toisnot_Swamp_DS_021220.p01 (plan) ---

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Plan Title=100 Year Single
Short Identifier=Plan01
Geom File=g01
Flow File=f01
Encroach River=Toisnot Swamp DS
Encroach Reach=Reach - 1
Encroach Node=50870.5
       1    4625    5725
Encroach Node=49439.1
       1    4650    5900
Encroach Node=48200.6
       4      .8
Encroach Node=46836.4
       4      .8
Encroach Node=46081.7
       4      .8
Encroach Node=45339.1
       4      .8
Encroach Node=44718.9
       1    4750    5250
Encroach Node=44549.9
       1    4750    5250
Encroach Node=43912.2
       4      .7
Encroach Node=43121.0
       4      .7
Encroach Node=42359.9
       4      .7
Encroach Node=41531.5
       4      .7
Encroach Node=40753.9
       4      .7
Encroach Node=40050.4
       4      .7
Encroach Node=39152.4
       4      .7
Encroach Node=38165.0
       4      .7
Encroach Node=37169.5
       4      .7
Encroach Node=35201.5
       4      .7
Encroach Node=33877.0
       4      .7
Encroach Node=33313.1
       4      .7
Encroach Node=33269.1
       4      .7
Encroach Node=32814.2
       4      .7
Encroach Node=32204.5
       4      .7
Encroach Node=31153.2
       4      .7
Encroach Node=30156.9
       4      .7
Encroach Node=29157.6
       4      .7
Encroach Node=27905.9
       4      .7
Encroach Node=27000.0
       4      .7
Encroach Node=25913.0
       4      .7
Encroach Node=25079.6
       4      .7
Encroach Node=24253.7
       4      .7
Encroach Node=23199.2
       4      .7
Encroach Node=21967.5
       4      .7
Encroach Node=20715.5
       4      .7
Encroach Node=19937.7
       4      .7
Encroach Node=19097.9
       4      .7
Encroach Node=18360.6
       4      .7
Encroach Node=17583.7
       4      .7
Encroach Node=16532.3
       4      .7
Encroach Node=15758.8
       4      .7
Encroach Node=14483.7
       4      .7
Encroach Node=14432.7
       4      .7
Encroach Node=13873.1
       4      .7
Encroach Node=13205.9
       4      .7
Encroach Node=12661.0
       4      .7
Encroach Node=11362.9
       4      .7
Encroach Node=10733.8
       4      .7
Encroach Node=10167.3
       4      .7
Encroach Node=9514.2
       4      .7
Encroach Node=8782.6
       1    4935    5225
Encroach Node=8317.3
       4      .7
Encroach Node=7829.7
       1  4148.3  5375.6

--- Toisnot_Swamp_DS_021220.f02 (steady flow) ---

Flow Title=Multi Profile
Program Version=4.00
Number of Profiles= 7
Profile Names=10-yr,25-yr,50-yr,500-yr,100-yr-10%,100-yr-20%,100-yr-35%
River Rch & RM=Toisnot Swamp DS,Reach - 1       ,50870.5
    5385    7146    8666   14721   10291   13190   16116
River Rch & RM=Toisnot Swamp DS,Reach - 1       ,48200.6
    5460    7243    8781   14909   10420   13354   16317
River Rch & RM=Toisnot Swamp DS,Reach - 1       ,43121.0
    5513    7311    8862   15040   10509   13469   16457
River Rch & RM=Toisnot Swamp DS,Reach - 1       ,39152.4
    5548    7357    8917   15128   10570   13547    1652
River Rch & RM=Toisnot Swamp DS,Reach - 1       ,35201.5
    7141    9408   11360   19053   13252   16984   20752
River Rch & RM=Toisnot Swamp DS,Reach - 1       ,31153.2
    7168    9443   11401   19119   13297   17042   20822
River Rch & RM=Toisnot Swamp DS,Reach - 1       ,29157.6
    7417    9761   11780   19724   13709   17570   21467
River Rch & RM=Toisnot Swamp DS,Reach - 1       ,20715.5
    7465    9823   11853   19841   13788   17672   21592
River Rch & RM=Toisnot Swamp DS,Reach - 1       ,16532.3
    7587    9979   12039   20137   13990   17931   21908
River Rch & RM=Toisnot Swamp DS,Reach - 1       ,13873.1
    7756   10196   12286   20546   14269   18288   22344
River Rch & RM=Toisnot Swamp DS,Reach - 1       ,10733.8
    7795   10245   12355   20641   14333   18370   22445
River Rch & RM=Toisnot Swamp DS,Reach - 1       ,7829.7
    7822   10280   12397   20706   14400   18400   22500
Boundary for River Rch & Prof#=Toisnot Swamp DS,Reach - 1       , 1
Up Type= 0
Dn Type= 1
Dn Known WS=61.73
Boundary for River Rch & Prof#=Toisnot Swamp DS,Reach - 1       , 2
Up Type= 0
Dn Type= 1
Dn Known WS=62.21
Boundary for River Rch & Prof#=Toisnot Swamp DS,Reach - 1       , 3
Up Type= 0
Dn Type= 1
Dn Known WS=63.28
Boundary for River Rch & Prof#=Toisnot Swamp DS,Reach - 1       , 4
Up Type= 0
Dn Type= 1
Dn Known WS=65.38
Boundary for River Rch & Prof#=Toisnot Swamp DS,Reach - 1       , 5
Up Type= 0
Dn Type= 1
Dn Known WS=63.48
Boundary for River Rch & Prof#=Toisnot Swamp DS,Reach - 1       , 6
Up Type= 0
Dn Type= 1
Dn Known WS=64.6
Boundary for River Rch & Prof#=Toisnot Swamp DS,Reach - 1       , 7
Up Type= 0
Dn Type= 1
Dn Known WS=65.7
DSS Import GetInterval= 0
DSS Import GetPeak= 0
DSS Import FillOption= 0

--- Toisnot_Swamp_DS_021220.f01 (steady flow) ---

Flow Title= 100 Year Single
Program Version=4.00
Number of Profiles= 2
Profile Names=100-Year,AFW
River Rch & RM=Toisnot Swamp DS,Reach - 1       ,50870.5
   10283   10283
River Rch & RM=Toisnot Swamp DS,Reach - 1       ,48200.6
   10418   10418
River Rch & RM=Toisnot Swamp DS,Reach - 1       ,43121
   10513   10513
River Rch & RM=Toisnot Swamp DS,Reach - 1       ,39152.4
   10577   10577
River Rch & RM=Toisnot Swamp DS,Reach - 1       ,35201.5
   13423   13423
River Rch & RM=Toisnot Swamp DS,Reach - 1       ,31153.2
   13471   13471
River Rch & RM=Toisnot Swamp DS,Reach - 1       ,29157.6
   13911   13911
River Rch & RM=Toisnot Swamp DS,Reach - 1       ,21967.5
   13996   13996
River Rch & RM=Toisnot Swamp DS,Reach - 1       ,20715.5
   14213   14213
River Rch & RM=Toisnot Swamp DS,Reach - 1       ,16532.3
   14511   14511
River Rch & RM=Toisnot Swamp DS,Reach - 1       ,13873.1
   14580   14580
River Rch & RM=Toisnot Swamp DS,Reach - 1       ,10733.8
   14630   14630
River Rch & RM=Toisnot Swamp DS,Reach - 1       ,7829.7
   14628   14628
Boundary for River Rch & Prof#=Toisnot Swamp DS,Reach - 1       , 1
Up Type= 0
Dn Type= 1
Dn Known WS=63.55
Boundary for River Rch & Prof#=Toisnot Swamp DS,Reach - 1       , 2
Up Type= 0
Dn Type= 1
Dn Known WS=64.46
DSS Import GetInterval= 0
DSS Import GetPeak= 0
DSS Import FillOption= 0

--- Toisnot_Swamp_DS_021220.g01 (geometry) ---

Geom Title=Geom 01 by CodeH2 for Windows
Program Version=4.00

River Reach=Toisnot Swamp DS,Reach - 1
Reach XY= 30
  0.091669847416  0.938529540218  0.099125001246  0.930410944364
  0.112581381706   0.88023974203  0.102869705662  0.856761085349
  0.134358137495  0.821468127871  0.251601214757  0.740018521074
  0.322520717961  0.659230866211  0.326696187469   0.64260108713
  0.313123560517  0.604435404541  0.325241147106  0.543648677033
  0.321177221985  0.498682444038  0.335073510519  0.435231973877
  0.349116870456   0.42119122622  0.353876184705  0.371558676171
  0.394194125382  0.329201327934  0.404868426871  0.325461848079
  0.425090875631  0.261416039141  0.453298282876  0.239065887733
  0.460234410651  0.207313354319   0.47804624676  0.180222958311
  0.504611574343  0.176752020914  0.504678187501  0.161467043949
  0.518428188314   0.14571499119  0.505212137681  0.141710103614
  0.516292126367  0.123821988908  0.511887037384  0.117280837978
  0.516559101457  0.104999461388   0.53004212718  0.095387835696
  0.540254316209  0.095721685173  0.548193296382  0.065789525604

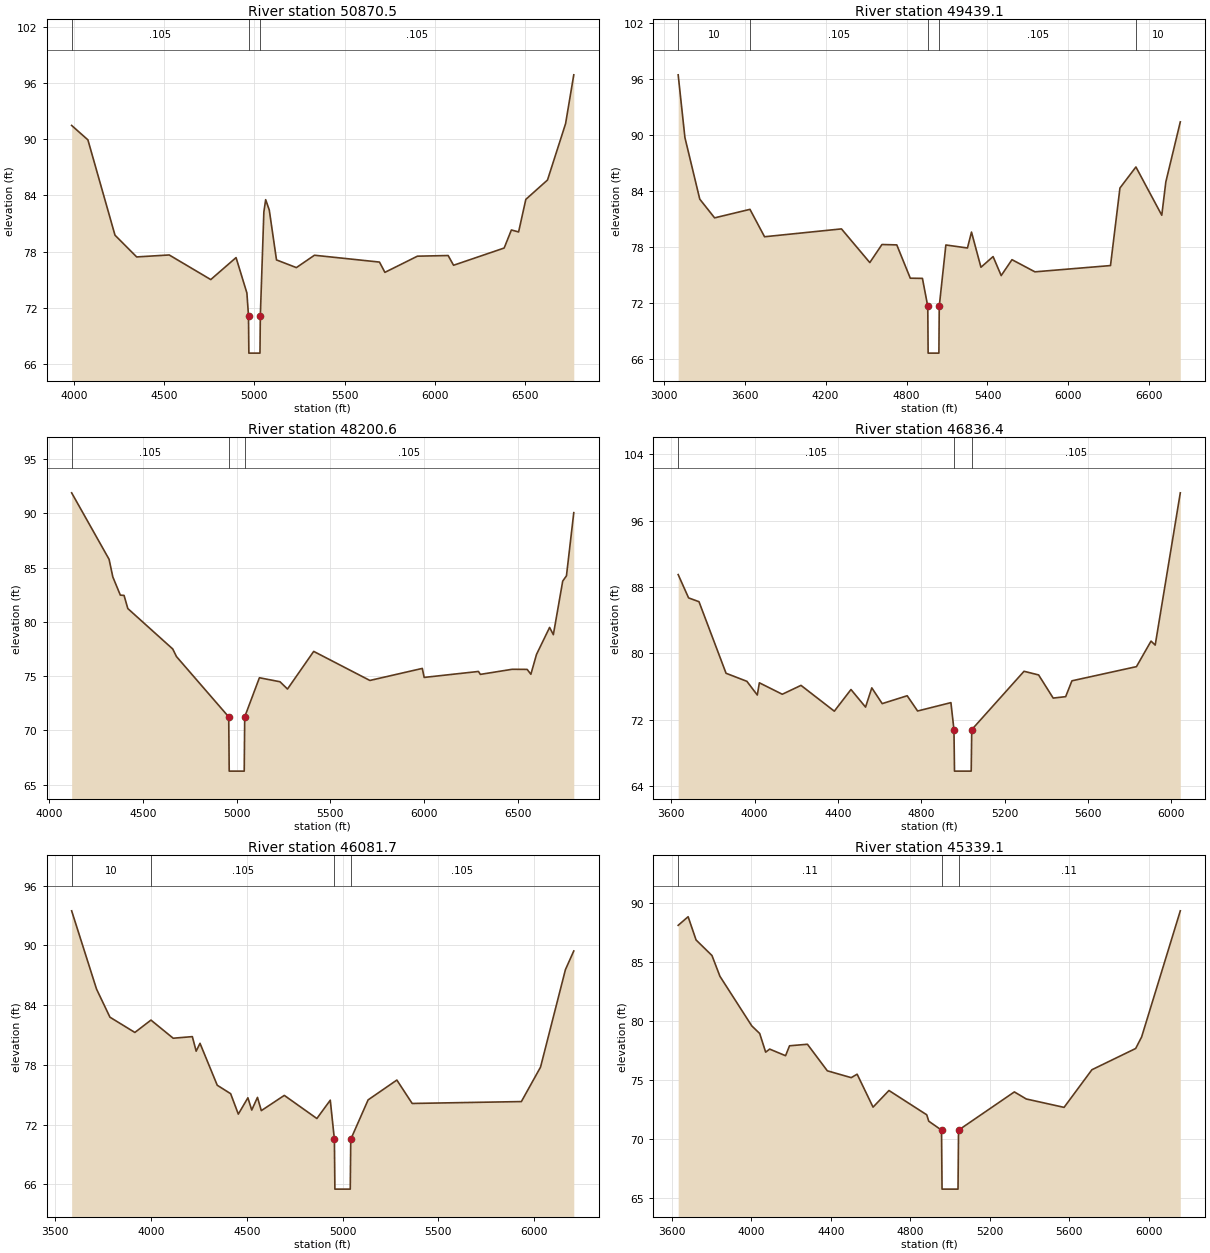
Type RM Length L Ch R = 1 ,50870.5 ,1431.4,1431.4,1431.4
BEGIN DESCRIPTION:
Toisnot Swamp DS 49.0 (Tie-in to Effective Study)
END DESCRIPTION:
#Sta/Elev= 30
  3988.3   91.47  4078.3   89.93  4228.3   79.74  4348.3   77.42  4528.3   77.63
  4758.3      75  4898.3   77.35  4958.3   73.57  4967.2   71.14  4969.2   67.14
  5030.7   67.14  5032.7   71.14  5052.2   82.22  5062.2   83.54  5082.2   82.43
  5122.2    77.1  5232.2   76.28  5332.2    77.6  5692.2   76.87  5722.2   75.77
  5902.2    77.5  6072.2   77.57  6102.2   76.53  6382.2   78.37  6422.2    80.3
  6462.2   80.09  6502.2   83.57  6622.2   85.64  6722.2   91.66  6767.6   96.88
#Mann= 3 , 1 , 0
  3988.3    .105       0  4967.2    .041       0  5032.7    .105       0
Bank Sta=4967.2,5032.7
XS Rating Curve= 0 ,0
Exp/Cntr=0.3,0.1

Type RM Length L Ch R = 1 ,49439.1 ,1238.5,1238.5,1238.5
BEGIN DESCRIPTION:
Toisnot Swamp DS 48.0
END DESCRIPTION:
#Sta/Elev= 30
  3107.9   96.41  3157.9    89.7  3267.9   83.12  3377.9   81.12  3639.9   82.03
  3747.9    79.1  4317.9   79.94  4527.9   76.34  4617.9   78.27  4727.9   78.23
  4827.9   74.67  4917.9   74.65 4957.49   71.66 4960.09   66.66 5039.91   66.66
 5042.51   71.66  5091.5   78.22  5251.5    77.9  5281.5    79.6  5351.5   75.84
  5441.5   76.98  5501.5   74.95  5581.5   76.65  5751.5   75.35  6311.5   76.02
  6381.5   84.31  6499.9   86.56  6691.5    81.4  6721.5   84.96  6828.8   91.38
#Mann= 5 , 1 , 0
  3107.9      10       0  3639.9    .105       0 4957.49    .041       0
 5042.51    .105       0  6499.9      10       0
Bank Sta=4957.49,5042.51
XS Rating Curve= 0 ,0
Exp/Cntr=0.3,0.1

Type RM Length L Ch R = 1 ,48200.6 ,1364.2,1364.2,1364.2
BEGIN DESCRIPTION:
Toisnot Swamp DS 47.0
END DESCRIPTION:
#Sta/Elev= 30
  4118.4    91.9  4318.4   85.77  4338.4   84.14  4378.4   82.47  4398.4   82.44
  4418.4   81.23  4658.4    77.5  4678.4    76.8 4957.36   71.24 4959.96   66.24
 5040.17   66.24 5042.77   71.24  5121.3   74.85  5231.3   74.48  5271.3   73.81
  5411.3   77.28  5711.3    74.6  5991.3   75.71  6001.3   74.88  6291.3   75.43
  6301.3   75.16  6471.3   75.63  6551.3   75.62  6571.3   75.17  6601.3      77
  6671.3   79.49  6691.3   78.82  6741.3   83.76  6761.3   84.25  6800.4   90.07
#Mann= 3 , 1 , 0
  4118.4    .105       0 4957.36    .041       0 5042.77    .105       0
Bank Sta=4957.36,5042.77
XS Rating Curve= 0 ,0
Exp/Cntr=0.3,0.1

Type RM Length L Ch R = 1 ,46836.4 ,754.7,754.7,754.7
BEGIN DESCRIPTION:
Toisnot Swamp DS 46.0
END DESCRIPTION:
#Sta/Elev= 30
  3632.6   89.48  3682.6   86.67  3732.6   86.21  3862.6   77.58  3962.6   76.61
  4012.6   74.96  4022.6   76.43  4132.6   75.05  4222.6   76.12  4382.6   73.01
  4462.6   75.62  4532.6    73.5  4562.6   75.82  4612.6   73.92  4732.6   74.87
  4782.6   73.03  4942.6   74.04 4957.23   70.78 4959.83   65.78 5040.04   65.78
 5042.64   70.78  5293.8   77.82  5363.8   77.38  5433.8   74.59  5493.8   74.76
  5523.8   76.67  5833.8   78.38  5903.8   81.46  5923.8   80.98  6044.4   99.34
#Mann= 3 , 1 , 0
  3632.6    .105       0 4957.23    .041       0 5042.64    .105       0
Bank Sta=4957.23,5042.64
XS Rating Curve= 0 ,0
Exp/Cntr=0.3,0.1

Type RM Length L Ch R = 1 ,46081.7 ,742.6,742.6,742.6
BEGIN DESCRIPTION:
Toisnot Swamp DS 45.0
END DESCRIPTION:
#Sta/Elev= 30
  3585.9   93.47  3715.9   85.61  3785.9   82.79  3915.9   81.26  3999.9    82.5
  4115.9   80.68  4215.9   80.84  4235.9   79.38  4255.9   80.17  4345.9   75.96
  4415.9   75.11  4455.9   73.06  4505.9    74.7  4525.9   73.47  4555.9   74.74
  4575.9   73.41  4695.9   74.94  4865.9   72.62  4935.9   74.46 4957.36   70.53
 4959.96   65.53 5040.17   65.53 5042.77   70.53  5133.4   74.49  5283.4   76.48
  5363.4   74.13  5933.4   74.32  6033.4   77.78  6163.4   87.57  6206.9   89.44
#Mann= 4 , 1 , 0
  3585.9      10       0  3999.9    .105       0 4957.36    .041       0
 5042.77    .105       0
Bank Sta=4957.36,5042.77
XS Rating Curve= 0 ,0
Exp/Cntr=0.3,0.1

Type RM Length L Ch R = 1 ,45339.1 ,620.2,620.2,620.2
BEGIN DESCRIPTION:
Toisnot Swamp DS 44.0
END DESCRIPTION:
#Sta/Elev= 30
  3632.9   88.09  3682.9   88.82  3722.9   86.85  3802.9   85.53  3842.9   83.77
  4002.9   79.57  4042.9   78.92  4072.9   77.34  4092.9    77.6  4172.9   77.04
  4192.9   77.88  4282.9   78.01  4382.9   75.76  4502.9   75.18  4532.9   75.47
  4612.9   72.68  4692.9   74.09  4882.9   72.03  4892.9   71.49 4957.23   70.73
 4959.83   65.73 5040.17   65.73 5042.77   70.73  5323.5   73.97  5383.5   73.37
  5573.5   72.66  5713.5   75.85  5933.5   77.65  5963.5   78.63    6158   89.32
#Mann= 3 , 1 , 0
  3632.9     .11       0 4957.23    .041       0 5042.77     .11       0
Bank Sta=4957.23,5042.77
XS Rating Curve= 0 ,0
Exp/Cntr=0.5,0.3

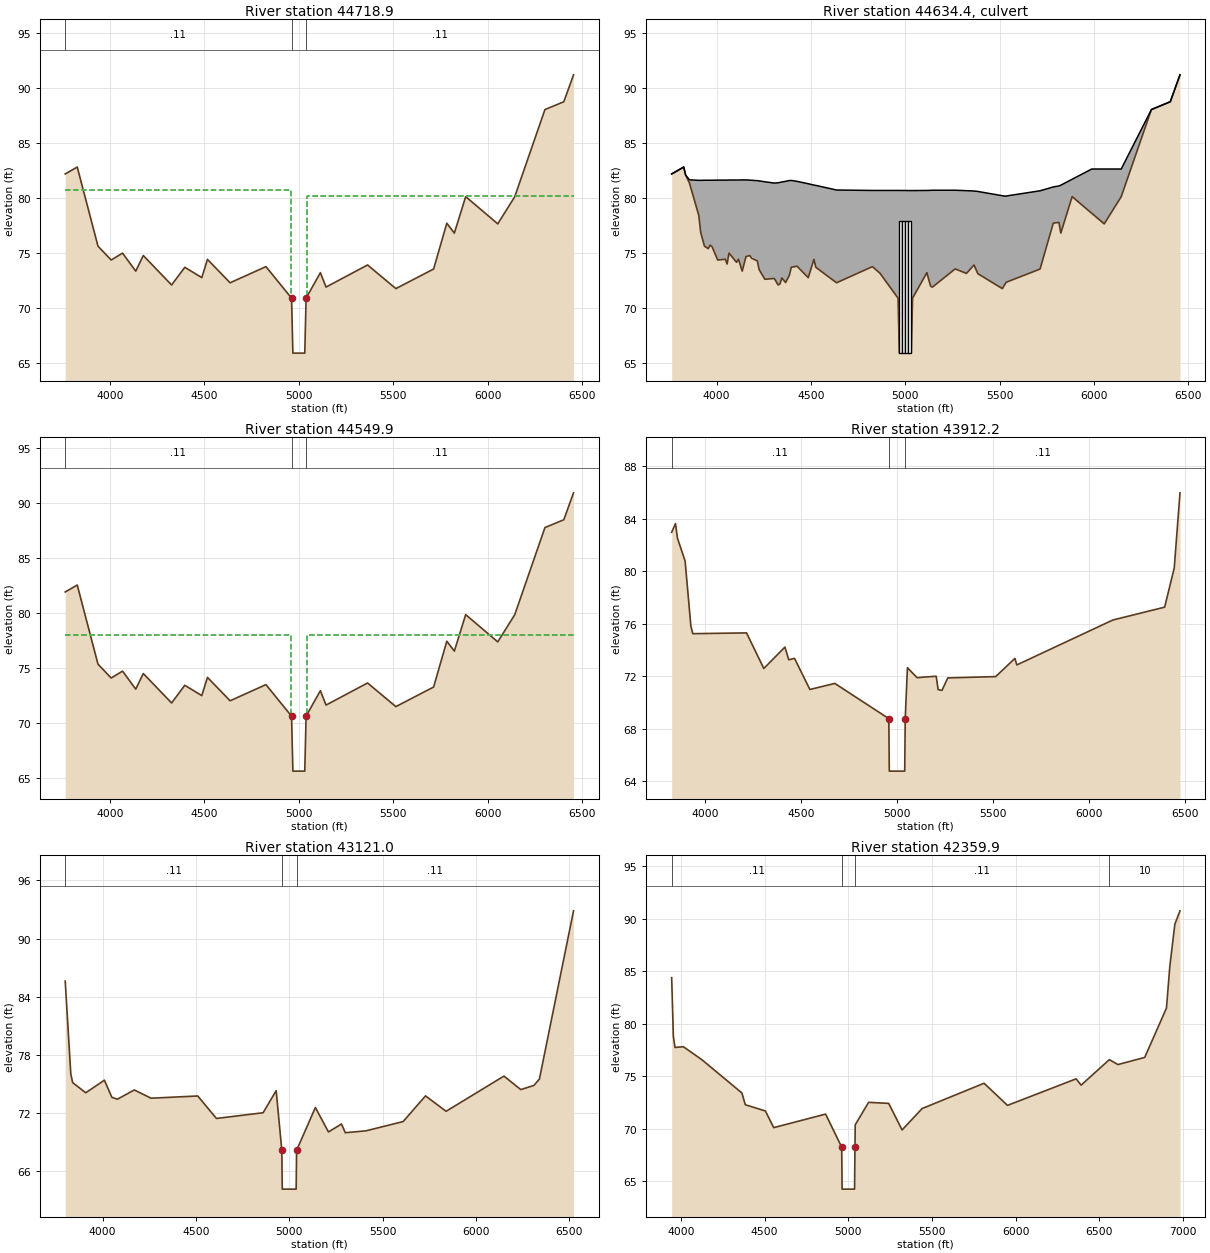
Type RM Length L Ch R = 1 ,44718.9 ,169,169,169
BEGIN DESCRIPTION:
Upstream Section of Bridge/Culvert/Weir
END DESCRIPTION:
#Sta/Elev= 30
    3762    82.2  3825.8   82.83  3935.8   75.63  4005.8   74.37  4065.8      75
  4135.8   73.36  4175.8   74.78  4325.8    72.1  4395.8   73.71  4485.8   72.77
  4515.8   74.43  4635.8    72.3  4825.8   73.77  4961.5    70.9  4968.5    65.9
  5031.5    65.9  5038.5    70.9  5114.2   73.22  5144.2   71.91  5364.2   73.92
  5514.2   71.77  5714.2   73.55  5784.2   77.72  5824.2   76.82  5884.2   80.14
  6054.2   77.66  6144.2   80.13  6304.2   88.06  6404.2   88.77  6455.7   91.22
#Mann= 3 , 1 , 0
    3762     .11       0  4961.5    .041       0  5038.5     .11       0
#XS Ineff= 2 , 0
       0    4956    80.7    5044       0    80.2
Permanent Ineff=
       F       F
Bank Sta=4961.5,5038.5
XS Rating Curve= 0 ,0
Exp/Cntr=0.5,0.3

Type RM Length L Ch R = 2 ,44634.4 ,,,
BEGIN DESCRIPTION:
US Hwy 264-TOR
Structure ID: TS - US 264
Approximate Survey Structure
END DESCRIPTION:
Bridge Culvert--1,0,-1,-1, 0
Deck Dist Width WeirC Skew NumUp NumDn MinLoCord MaxHiCord MaxSubmerge Is_Ogee
10,149,3,0, 60, 60, , , 0.95, 0, 1,1,,
    3762  3825.8  3835.8  3855.8  3905.8  3915.8  3935.8  3955.8  3965.8  3975.8
  4005.8  4045.8  4055.8  4065.8  4105.8  4115.8  4135.8  4155.8  4175.8  4215.8
  4225.8  4255.8  4305.8  4325.8  4335.8  4345.8  4365.8  4385.8  4395.8  4425.8
  4485.8  4515.8  4525.8  4635.8  4825.8  4865.8  4961.5  4968.5  5031.5  5038.5
  5114.2  5134.2  5144.2  5264.2  5324.2  5364.2  5384.2  5514.2  5529.1  5714.2
  5784.2  5814.2  5824.2  5884.2  5988.1  6054.2  6144.2  6304.2  6404.2  6455.7
    82.2   82.83   82.11   81.67   81.62   81.62   81.63   81.63   81.63   81.63
   81.64   81.64   81.64   81.65   81.65   81.65   81.66   81.66   81.64   81.59
   81.57   81.49   81.37    81.4   81.43   81.47   81.53    81.6   81.61   81.53
   81.31   81.19   81.16   80.74    80.7    80.7    80.7    80.7   80.69   80.69
    80.7   80.71   80.72   80.72   80.68   80.65   80.61   80.22   80.18   80.67
   81.02   81.11   81.18   81.72   82.65   82.65   82.65   88.06   88.77   91.22
    82.2   82.83   82.11   81.39   78.42   76.88   75.63   75.41   75.72   75.59
   74.37   74.44   74.01      75   74.16   74.44   73.36   74.68   74.78   74.29
   73.49   72.62   72.69    72.1   72.19   72.74   72.32   72.99   73.71   73.81
   72.77   74.43   73.71    72.3   73.77   73.17    70.9    65.9    65.9    70.9
   73.22   71.98   71.91   73.56   73.15   73.92   73.13   71.77   72.19   73.55
   77.72    77.8   76.82   80.14   78.62   77.66   80.13   88.06   88.77   91.22
    3762  3825.8  3835.8  3855.8  3905.8  3915.8  3935.8  3955.8  3965.8  3975.8
  4005.8  4045.8  4055.8  4065.8  4105.8  4115.8  4135.8  4155.8  4175.8  4215.8
  4225.8  4255.8  4305.8  4325.8  4335.8  4345.8  4365.8  4385.8  4395.8  4425.8
  4485.8  4515.8  4525.8  4635.8  4825.8  4865.8  4961.5  4968.5  5031.5  5038.5
  5114.2  5134.2  5144.2  5264.2  5324.2  5364.2  5384.2  5514.2  5529.1  5714.2
  5784.2  5814.2  5824.2  5884.2  5988.1  6054.2  6144.2  6304.2  6404.2  6455.7
   82.05   82.69   81.97   81.67   81.62   81.62   81.63   81.63   81.63   81.63
   81.64   81.64   81.64   81.65   81.65   81.65   81.66   81.66   81.64   81.59
   81.57   81.49   81.37    81.4   81.43   81.47   81.53    81.6   81.61   81.53
   81.31   81.19   81.16   80.74    80.7    80.7    80.7    80.7   80.69   80.69
    80.7   80.71   80.72   80.72   80.68   80.65   80.61   80.22   80.18   80.67
   81.02   81.11   81.18   81.72   82.65   82.65   82.65   87.92   88.62   91.07
    81.9   82.53   81.81   81.09   78.12   76.58   75.33   75.11   75.42   75.29
   74.07   74.14   73.71    74.7   73.86   74.14   73.06   74.38   74.48   73.99
   73.19   72.32   72.39    71.8   71.89   72.44   72.02   72.69   73.41   73.51
   72.47   74.13   73.41      72   73.47   72.87    70.6    65.6    65.6    70.6
   72.92   71.68   71.61   73.26   72.85   73.62   72.83   71.47   71.89   73.25
   77.42    77.5   76.52   79.84   78.32   77.36   79.83   87.76   88.47   90.92
BR Coef= 1 , 0 , 0 ,1.25, 0 ,,,0.8,-1,2,0,
WSPro=,,,, 1 ,,,, 0 ,,,, 0 ,,,,-1 ,-1 ,-1 , 0 , 0 , 0 , 0 , 0
Culvert=2,12,15,149,0.015,0.4,1,8,1,65.9,4976.01,65.6,4976.01,Culvert #1  , 0 ,10
Culvert Bottom n=0.015
Culvert=2,12,15,149,0.015,0.4,1,8,1,65.9,4992.01,65.6,4992.01,Culvert #2  , 0 ,10
Culvert Bottom n=0.015
Culvert=2,12,15,149,0.015,0.4,1,8,1,65.9,5008.01,65.6,5008.01,Culvert #3  , 0 ,10
Culvert Bottom n=0.015
Culvert=2,12,15,149,0.015,0.4,1,8,1,65.9,5024.01,65.6,5024.01,Culvert #4  , 0 ,10
Culvert Bottom n=0.015
BR U #Sta/Elev= 79
    3762    82.2  3825.8   82.83    3832   82.38  3835.8   82.11  3855.8   81.39
    3902   78.65  3905.8   78.42  3915.8   76.88  3935.8   75.63  3955.8   75.41
  3965.8   75.72  3975.8   75.59  4005.8   74.37  4045.8   74.44  4055.8   74.01
  4065.8      75  4105.8   74.16  4115.8   74.44  4135.8   73.36  4155.8   74.68
    4162   74.71  4175.8   74.78  4185.8   74.53  4215.8   74.29    4222   73.79
  4225.8   73.49  4255.8   72.62  4305.8   72.69    4312   72.51  4325.8    72.1
  4335.8   72.19  4345.8   72.74  4365.8   72.32    4382   72.86  4385.8   72.99
  4395.8   73.71    4402   73.73  4425.8   73.81  4485.8   72.77  4515.8   74.43
  4525.8   73.71  4635.8    72.3  4644.8   72.37  4825.8   73.77  4865.8   73.17
  4961.5    70.9  4968.5    65.9  5031.5    65.9  5038.5    70.9  5079.1   72.14
  5109.1   73.06  5114.2   73.22  5134.2   71.98  5144.2   71.91  5219.1   72.94
  5264.2   73.56  5324.2   73.15  5364.2   73.92  5369.1   73.73  5384.2   73.13
  5514.2   71.77  5529.1   72.19  5534.2   72.34  5559.1   72.51  5649.1   73.11
  5714.2   73.55  5779.1   77.42  5784.2   77.72  5814.2    77.8  5819.1   77.32
  5824.2   76.82  5884.2   80.14  5988.1   78.62  6054.2   77.66  6144.2   80.13
  6304.2   88.06  6388.1   88.66  6404.2   88.77  6455.7   91.22
BR U #Mann= 3
    3762     .11  4961.5    .041  5038.5     .11
BR U Banks=4961.5,5038.5
BR D #Sta/Elev= 79
    3762    81.9  3825.8   82.53    3832   82.08  3835.8   81.81  3855.8   81.09
    3902   78.35  3905.8   78.12  3915.8   76.58  3935.8   75.33  3955.8   75.11
  3965.8   75.42  3975.8   75.29  4005.8   74.07  4045.8   74.14  4055.8   73.71
  4065.8    74.7  4105.8   73.86  4115.8   74.14  4135.8   73.06  4155.8   74.38
    4162   74.41  4175.8   74.48  4185.8   74.23  4215.8   73.99    4222   73.49
  4225.8   73.19  4255.8   72.32  4305.8   72.39    4312   72.21  4325.8    71.8
  4335.8   71.89  4345.8   72.44  4365.8   72.02    4382   72.56  4385.8   72.69
  4395.8   73.41    4402   73.43  4425.8   73.51  4485.8   72.47  4515.8   74.13
  4525.8   73.41  4635.8      72  4644.8   72.07  4825.8   73.47  4865.8   72.87
  4961.5    70.6  4968.5    65.6  5031.5    65.6  5038.5    70.6  5079.1   71.84
  5109.1   72.76  5114.2   72.92  5134.2   71.68  5144.2   71.61  5219.1   72.64
  5264.2   73.26  5324.2   72.85  5364.2   73.62  5369.1   73.43  5384.2   72.83
  5514.2   71.47  5529.1   71.89  5534.2   72.04  5559.1   72.21  5649.1   72.81
  5714.2   73.25  5779.1   77.12  5784.2   77.42  5814.2    77.5  5819.1   77.02
  5824.2   76.52  5884.2   79.84  5988.1   78.32  6054.2   77.36  6144.2   79.83
  6304.2   87.76  6388.1   88.36  6404.2   88.47  6455.7   90.92
BR D #Mann= 3
    3762     .11  4961.5    .041  5038.5     .11
BR D Banks=4961.5,5038.5
BC Design=,, 0 ,, 0 ,,,,,,
BC HTab HWMax=91.22
BC Use User HTab Curves=0
BC User HTab FreeFlow(D)= 0

Type RM Length L Ch R = 1 ,44549.9 ,637.7,637.7,637.7
BEGIN DESCRIPTION:
Downstream Section of Bridge/Culvert/Weir
END DESCRIPTION:
#Sta/Elev= 30
    3762   81.89  3825.8   82.52  3935.8   75.32  4005.8   74.06  4065.8   74.69
  4135.8   73.05  4175.8   74.47  4325.8   71.79  4395.8    73.4  4485.8   72.46
  4515.8   74.12  4635.8   71.99  4825.8   73.46  4961.5   70.59  4968.5   65.59
  5031.5   65.59  5038.5   70.59  5114.2   72.91  5144.2    71.6  5364.2   73.61
  5514.2   71.46  5714.2   73.24  5784.2   77.41  5824.2   76.51  5884.2   79.83
  6054.2   77.35  6144.2   79.82  6304.2   87.75  6404.2   88.46  6455.7   90.91
#Mann= 3 , 1 , 0
    3762     .11       0  4961.5    .041       0  5038.5     .11       0
#XS Ineff= 2 , 0
       0    4956      78    5044       0      78
Permanent Ineff=
       F       F
Bank Sta=4961.5,5038.5
XS Rating Curve= 0 ,0
Exp/Cntr=0.5,0.3

Type RM Length L Ch R = 1 ,43912.2 ,791.2,791.2,791.2
BEGIN DESCRIPTION:
Toisnot Swamp DS 42.0
END DESCRIPTION:
#Sta/Elev= 30
  3826.1   82.97  3846.1   83.63  3856.1   82.52  3896.1   80.78  3926.1   75.82
  3936.1   75.24  4216.1    75.3  4306.1   72.59  4416.1   74.22  4436.1   73.25
  4466.1   73.36  4546.1   70.99  4676.1   71.45 4957.23   68.77 4959.83   64.77
 5040.17   64.77 5042.77   68.77  5054.2   72.65  5104.2   71.89  5204.2      72
  5214.2   70.98  5234.2   70.92  5264.2   71.87  5514.2   71.97  5614.2   73.36
  5624.2   72.86  6124.2   76.28  6394.2   77.26  6444.2   80.24  6474.2   85.97
#Mann= 3 , 1 , 0
  3826.1     .11       0 4957.23    .041       0 5042.77     .11       0
Bank Sta=4957.23,5042.77
XS Rating Curve= 0 ,0
Exp/Cntr=0.3,0.1

Type RM Length L Ch R = 1 ,43121.0 ,761.1,761.1,761.1
BEGIN DESCRIPTION:
Toisnot Swamp DS 41.0
END DESCRIPTION:
#Sta/Elev= 30
  3800.2   85.62  3830.2   76.04  3840.2   75.15  3910.2    74.1  4010.2    75.4
  4050.2   73.63  4080.2   73.44  4170.2   74.39  4260.2   73.54  4510.2   73.77
  4610.2   71.45  4860.2   72.04  4930.2   74.32  4960.4   68.16  4962.8   64.16
  5037.2   64.16  5039.6   68.16  5140.2   72.58  5210.2   70.06  5280.2   70.88
  5300.2   69.98  5410.2   70.17  5610.2   71.13  5730.2   73.78  5840.2   72.19
  6150.2   75.82  6240.2   74.43  6310.2   74.85  6340.2   75.52  6522.9   92.87
#Mann= 3 , 1 , 0
  3800.2     .11       0  4960.4    .041       0  5039.6     .11       0
Bank Sta=4960.4,5039.6
XS Rating Curve= 0 ,0
Exp/Cntr=0.3,0.1

Type RM Length L Ch R = 1 ,42359.9 ,828.4,828.4,828.4
BEGIN DESCRIPTION:
Toisnot Swamp DS 40.0
END DESCRIPTION:
#Sta/Elev= 30
  3944.2   84.38  3954.2    78.8  3964.2   77.73  4014.2    77.8  4124.2   76.57
  4364.2   73.39  4384.2   72.27  4504.2   71.68  4554.2   70.09  4864.2   71.38
  4960.4   68.23  4962.8   64.23  5037.2   64.23  5039.6   68.23  5041.2   70.36
  5121.2    72.5  5241.2    72.4  5321.2   69.87  5441.2   71.91  5811.2   74.32
  5951.2   72.21  6361.2   74.74  6391.2   74.14  6559.9   76.57  6611.2    76.1
  6771.2   76.78  6901.2   81.48  6921.2   85.44  6951.2   89.47  6982.1   90.75
#Mann= 4 , 1 , 0
  3944.2     .11       0  4960.4    .041       0  5039.6     .11       0
  6559.9      10       0
Bank Sta=4960.4,5039.6
XS Rating Curve= 0 ,0
Exp/Cntr=0.3,0.1

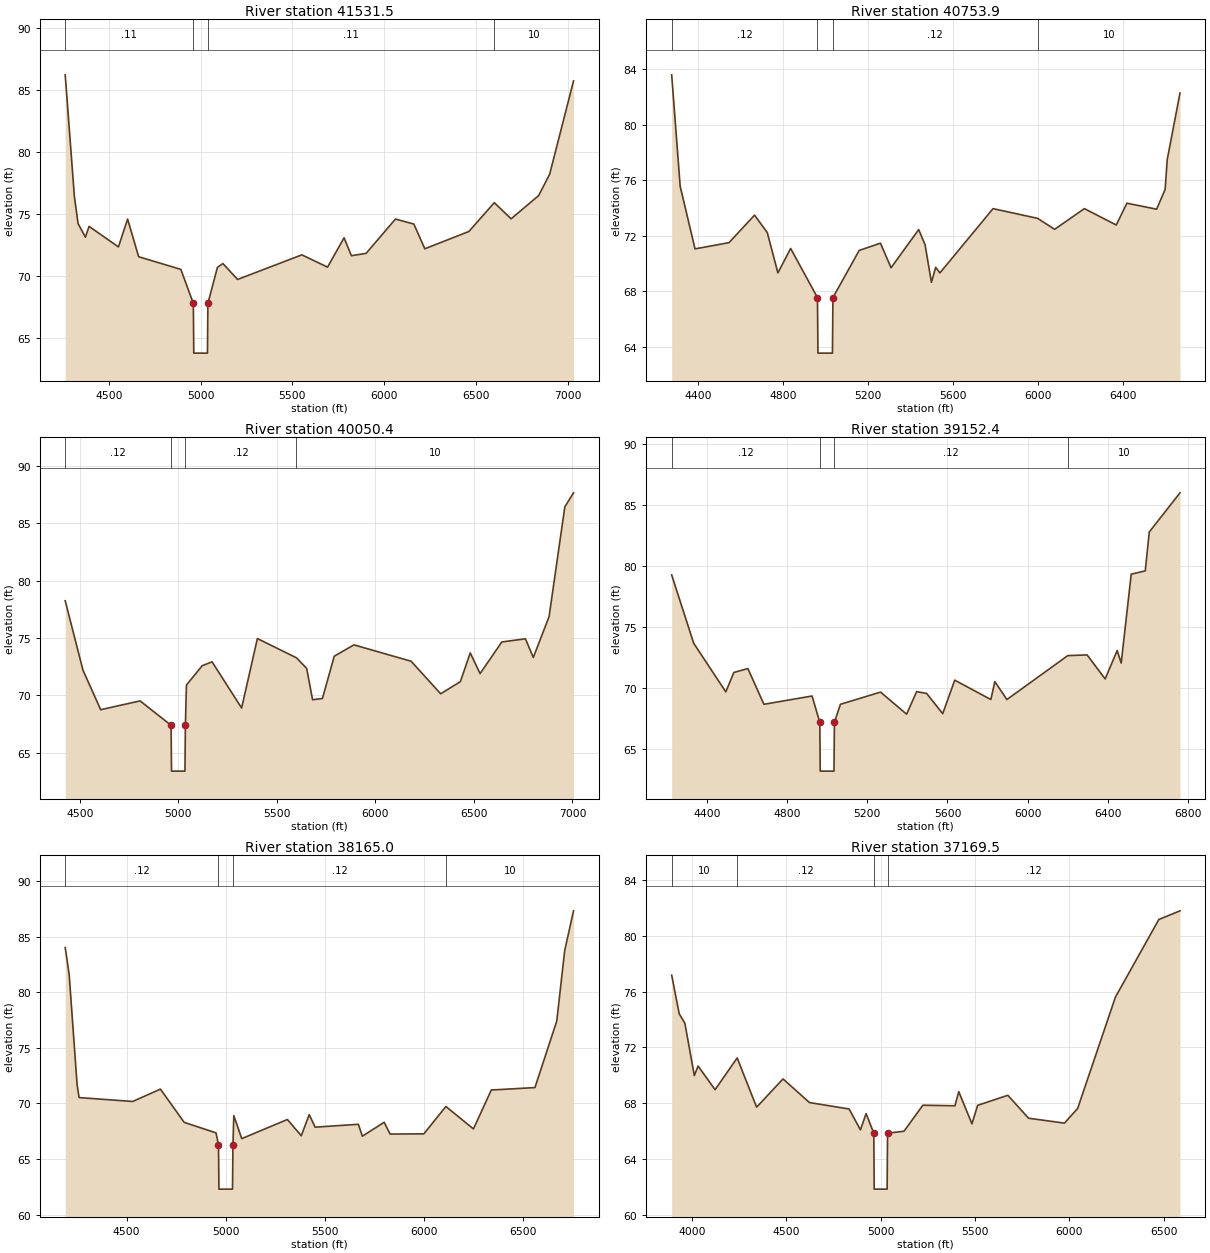
Type RM Length L Ch R = 1 ,41531.5 ,777.6,777.6,777.6
BEGIN DESCRIPTION:
Toisnot Swamp DS 39.0
END DESCRIPTION:
#Sta/Elev= 30
  4262.4   86.21  4312.4   76.42  4332.4   74.24  4372.4   73.14  4392.4   74.01
  4552.4   72.36  4602.4    74.6  4662.4   71.57  4892.4   70.55  4960.4   67.81
  4962.8   63.81 5037.32   63.81 5039.72   67.81  5091.5   70.71  5121.5   71.02
  5201.5   69.74  5551.5   71.72  5691.5   70.73  5781.5   73.09  5821.5   71.65
  5901.5   71.84  6061.5    74.6  6161.5    74.2  6221.5   72.21  6461.5    73.6
  6599.9   75.92  6691.5   74.62  6841.5   76.49  6901.5   78.21  7031.5   85.72
#Mann= 4 , 1 , 0
  4262.4     .11       0  4960.4    .041       0 5039.72     .11       0
  6599.9      10       0
Bank Sta=4960.4,5039.72
XS Rating Curve= 0 ,0
Exp/Cntr=0.3,0.1

Type RM Length L Ch R = 1 ,40753.9 ,703.5,703.5,703.5
BEGIN DESCRIPTION:
Toisnot Swamp DS 38.0
END DESCRIPTION:
#Sta/Elev= 30
  4277.4   83.61  4317.4   75.58  4387.4   71.07  4547.4   71.52  4667.4    73.5
  4727.4   72.25  4777.4   69.34  4837.4    71.1  4963.7   67.56  4965.9   63.56
 5034.21   63.56 5036.41   67.56  5160.1   70.96  5260.1   71.48  5310.1   69.71
  5440.1   72.46  5470.1   71.37  5500.1   68.66  5520.1   69.74  5540.1   69.34
  5790.1   73.97  5999.9   73.27  6080.1   72.48  6220.1   73.97  6370.1   72.79
  6420.1   74.36  6560.1   73.93  6600.1   75.35  6610.1   77.51  6670.1    82.3
#Mann= 4 , 1 , 0
  4277.4     .12       0  4963.7    .042       0 5036.41     .12       0
  5999.9      10       0
Bank Sta=4963.7,5036.41
XS Rating Curve= 0 ,0
Exp/Cntr=0.3,0.1

Type RM Length L Ch R = 1 ,40050.4 ,898,898,898
BEGIN DESCRIPTION:
Toisnot Swamp DS 37.0
END DESCRIPTION:
#Sta/Elev= 30
  4426.5   78.25  4516.5    72.2  4606.5   68.74  4806.5   69.51  4963.7   67.38
  4965.9   63.38  5034.1   63.38  5036.3   67.38  5041.6   70.89  5121.6   72.58
  5171.6   72.92  5321.6   68.89  5401.6   74.95  5599.9   73.27  5651.6   72.35
  5681.6   69.61  5731.6   69.72  5791.6   73.41  5891.6    74.4  6181.6   72.97
  6331.6   70.13  6431.6   71.19  6481.6    73.7  6531.6   71.89  6641.6   74.65
  6761.6   74.93  6801.6    73.3  6881.6   76.86  6961.6   86.45  7005.7   87.67
#Mann= 4 , 1 , 0
  4426.5     .12       0  4963.7    .042       0  5036.3     .12       0
  5599.9      10       0
Bank Sta=4963.7,5036.3
XS Rating Curve= 0 ,0
Exp/Cntr=0.3,0.1

Type RM Length L Ch R = 1 ,39152.4 ,987.4,987.4,987.4
BEGIN DESCRIPTION:
Toisnot Swamp DS 36.0
END DESCRIPTION:
#Sta/Elev= 30
  4224.9   79.24  4334.9   73.63  4494.9   69.65  4534.9   71.24  4604.9   71.56
  4684.9   68.63  4924.9   69.31 4963.48   67.15 4965.68   63.15 5034.21   63.15
 5036.41   67.15  5066.4   68.63  5266.4   69.63  5396.4   67.82  5446.4   69.67
  5496.4   69.52  5576.4   67.86  5636.4   70.61  5816.4   69.02  5836.4   70.49
  5896.4   69.02  6199.9   72.62  6296.4   72.68  6386.4   70.71  6446.4   73.04
  6466.4   72.01  6516.4    79.3  6586.4   79.57  6606.4   82.76  6759.6   85.97
#Mann= 4 , 1 , 0
  4224.9     .12       0 4963.48    .042       0 5036.41     .12       0
  6199.9      10       0
Bank Sta=4963.48,5036.41
XS Rating Curve= 0 ,0
Exp/Cntr=0.3,0.1

Type RM Length L Ch R = 1 ,38165.0 ,995.5,995.5,995.5
BEGIN DESCRIPTION:
Toisnot Swamp DS 35.0
END DESCRIPTION:
#Sta/Elev= 30
  4190.9   84.02  4210.9   81.59  4250.9   71.68  4260.9   70.53  4530.9   70.18
  4670.9   71.29  4790.9    68.3  4950.9   67.36 4963.59    66.3 4965.79    62.3
 5034.21    62.3 5036.41    66.3  5040.8   68.91  5080.8   66.84  5310.8   68.56
  5380.8    67.1  5420.8      69  5450.8   67.87  5668.7   68.13  5688.7   67.06
  5798.7   68.31  5828.7   67.25  5998.7   67.27  6109.9   69.73  6248.7   67.71
  6338.7   71.21  6558.7   71.43  6668.7   77.41  6708.7   83.75  6753.2   87.32
#Mann= 4 , 1 , 0
  4190.9     .12       0 4963.59    .042       0 5036.41     .12       0
  6109.9      10       0
Bank Sta=4963.59,5036.41
XS Rating Curve= 0 ,0
Exp/Cntr=0.3,0.1

Type RM Length L Ch R = 1 ,37169.5 ,1968,1968,1968
BEGIN DESCRIPTION:
Toisnot Swamp DS 34.0
END DESCRIPTION:
#Sta/Elev= 30
  3892.9   77.17  3932.9   74.41  3962.9   73.73  4012.9   69.99  4032.9   70.67
  4122.9   68.98  4239.9   71.25  4342.9   67.73  4482.9   69.75  4622.9   68.06
  4832.9    67.6  4892.9   66.11  4922.9   67.27 4963.59   65.87 4965.79   61.87
 5034.32   61.87 5036.52   65.87  5123.7   66.01  5223.7   67.87  5393.7   67.83
  5413.7   68.84  5483.7   66.54  5513.7   67.86  5673.7   68.58  5783.7   66.94
  5973.7   66.59  6043.7   67.64  6243.7    75.6  6473.7   81.15  6585.8   81.77
#Mann= 4 , 1 , 0
  3892.9      10       0  4239.9     .12       0 4963.59    .042       0
 5036.52     .12       0
Bank Sta=4963.59,5036.52
XS Rating Curve= 0 ,0
Exp/Cntr=0.3,0.1