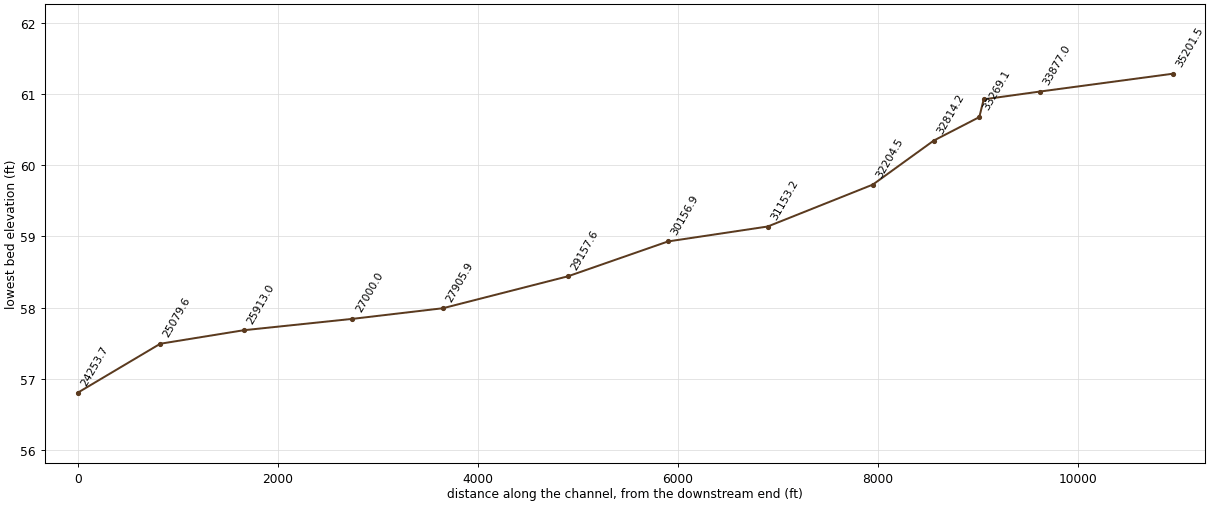
HEC-RAS study Toisnot_Swamp_DS_021220.prj: Toisnot Swamp DS

--- Toisnot_Swamp_DS_021220.g01 (geometry) --- (continued)

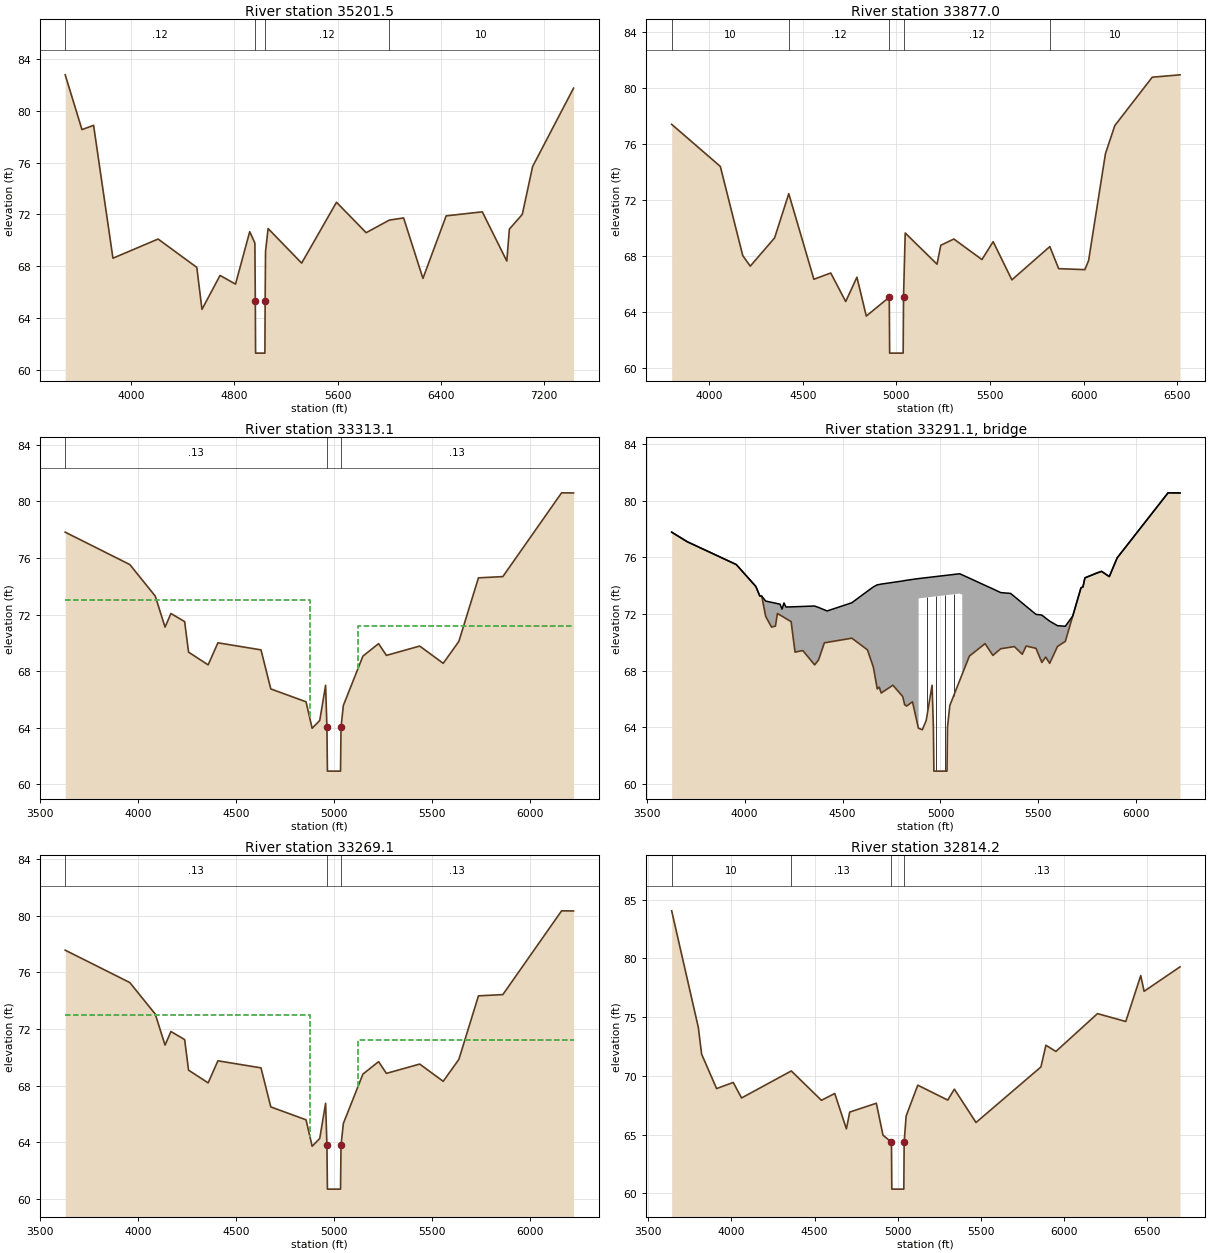
Type RM Length L Ch R = 1 ,35201.5 ,1324.5,1324.5,1324.5
BEGIN DESCRIPTION:
Toisnot Swamp DS 33.0
END DESCRIPTION:
#Sta/Elev= 30
  3488.5   82.78  3618.5   78.55  3708.5   78.88  3858.5   68.62  4208.5    70.1
  4508.5   67.91  4548.5   64.67  4688.5   67.29  4808.5   66.62  4918.5   70.67
  4958.5   69.79  4961.9   65.29  4963.9   61.29  5036.1   61.29  5038.1   65.29
    5041   69.13    5061   70.91    5321   68.24    5591   72.94    5821   70.59
  5999.9   71.56    6111   71.73    6261   67.06    6441   71.89    6721    72.2
    6911    68.4    6931   70.87    7031      72    7111    75.7  7428.1   81.75
#Mann= 4 , 1 , 0
  3488.5     .12       0  4961.9    .042       0  5038.1     .12       0
  5999.9      10       0
Bank Sta=4961.9,5038.1
XS Rating Curve= 0 ,0
Exp/Cntr=0.3,0.1

Type RM Length L Ch R = 1 ,33877.0 ,563.9,563.9,563.9
BEGIN DESCRIPTION:
Toisnot Swamp DS 32.0
END DESCRIPTION:
#Sta/Elev= 30
  3799.1    77.4  4059.1   74.39  4179.1   68.01  4219.1   67.26  4349.1   69.28
  4424.9   72.44  4559.1   66.32  4649.1   66.77  4729.1   64.73  4789.1   66.47
  4839.1   63.69  4961.9   65.04  4963.9   61.04  5036.1   61.04  5038.1   65.04
  5047.1   69.63  5217.1    67.4  5237.1   68.75  5307.1    69.2  5457.1   67.73
  5517.1   69.01  5617.1   66.28  5819.9   68.66  5867.1   67.08  6007.1   67.01
  6027.1   67.66  6117.1    75.3  6167.1   77.31  6367.1   80.77  6515.5   80.94
#Mann= 5 , 1 , 0
  3799.1      10       0  4424.9     .12       0  4961.9    .042       0
  5038.1     .12       0  5819.9      10       0
Bank Sta=4961.9,5038.1
XS Rating Curve= 0 ,0
Exp/Cntr=0.5,0.3

Type RM Length L Ch R = 1 ,33313.1 ,44,44,44
BEGIN DESCRIPTION:
Upstream Section of Bridge/Culvert/Weir
END DESCRIPTION:
#Sta/Elev= 30
  3627.3   77.82  3957.3   75.53  4087.3    73.3  4137.3   71.11  4167.3   72.07
  4237.3    71.5  4257.3   69.34  4357.3   68.44  4407.3      70  4627.3    69.5
  4677.3   66.74  4857.3   65.83 4888.41   63.96  4927.3   64.51  4957.3      67
    4964   64.03  4966.5   60.93  5033.5   60.93    5036   64.03  5047.9   65.57
  5147.9   69.06  5227.9   69.94  5267.9   69.11  5437.9   69.77  5557.9   68.55
  5637.9    70.1  5737.9   74.59  5862.5   74.68  6162.5    80.6  6223.5   80.59
#Mann= 3 , 1 , 0
  3627.3     .13       0    4964    .043       0    5036     .13       0
#XS Ineff= 2 , 0
       0    4878      73    5122       0    71.2
Permanent Ineff=
       F       F
Bank Sta=4964,5036
XS Rating Curve= 0 ,0
Exp/Cntr=0.5,0.3

Type RM Length L Ch R = 3 ,33291.1 ,,,
BEGIN DESCRIPTION:
Grimsley Store Rd-TOR
Structure ID: Grimsley Store Rd
Approximate Survey Structure
END DESCRIPTION:
Bridge Culvert--1,0,-1,-1, 0
Deck Dist Width WeirC Skew NumUp NumDn MinLoCord MaxHiCord MaxSubmerge Is_Ogee
10,24,2.6,0, 60, 60, , , 0.95, 0, 1,1,,
  3627.3  3707.3  3957.3  4057.3  4077.3  4087.3  4107.3  4137.3  4157.3  4167.3
  4180.9  4190.9  4200.9  4210.9  4237.3  4257.3  4297.3  4357.3  4377.3  4407.3
  4420.9  4547.3  4627.3  4657.3  4677.3  4687.3  4697.3  4757.3  4807.3  4817.3
  4827.3  4857.3 4888.41  4888.5  5098.2 5111.39  5111.5  5147.9  5227.9  5267.9
  5307.9  5358.2  5377.9  5417.9  5437.9  5487.9  5517.9  5537.9  5557.9  5597.9
  5637.9  5675.9  5717.9  5727.9  5737.9  5822.5  5862.5  5902.5  6162.5  6223.5
   77.79   77.11    75.5   73.95   73.28   73.27   72.92   72.83   72.77   72.74
    72.7   72.35   72.79    72.5   72.51   72.52   72.54   72.57   72.47    72.3
   72.22    72.8   73.62   73.92   74.07   74.09   74.12   74.24   74.34   74.37
   74.39   74.45   74.51   74.51   74.85   74.77   74.77   74.54   74.03   73.78
   73.52   73.46   73.24   72.78   72.55   71.98   71.93   71.71    71.5   71.18
   71.14   71.87   73.86   73.92   74.56   75.02   74.65   75.97   80.57   80.56
   77.79   77.11    75.5   73.95   73.28   73.27   71.84   71.08   71.15   72.04
   71.93   71.85   71.77   71.68   71.47   69.31   69.42   68.41   68.75   69.97
      70    70.3   69.47   68.25   66.71   66.84   66.42   66.97   66.17   65.59
    65.5    65.8   63.93   73.11   73.45   73.37   67.76   69.03   69.91   69.08
   69.55   69.66    69.7   69.16   69.74   69.58   68.58   68.96   68.52   69.71
   70.07   71.87   73.86   73.92   74.56   75.02   74.65   75.97   80.57   80.56
  3627.3  3707.3  3957.3  4057.3  4077.3  4087.3  4107.3  4137.3  4157.3  4167.3
  4180.9  4190.9  4200.9  4210.9  4237.3  4257.3  4297.3  4357.3  4377.3  4407.3
  4420.9  4547.3  4627.3  4657.3  4677.3  4687.3  4697.3  4757.3  4807.3  4817.3
  4827.3  4857.3 4888.41  4888.5  5098.2 5111.39  5111.5  5147.9  5227.9  5267.9
  5307.9  5358.2  5377.9  5417.9  5437.9  5487.9  5517.9  5537.9  5557.9  5597.9
  5637.9  5675.9  5717.9  5727.9  5737.9  5822.5  5862.5  5902.5  6162.5  6223.5
   77.69   77.01    75.4   73.86   73.19   73.18   72.92   72.83   72.77   72.74
    72.7   72.35   72.79    72.5   72.51   72.52   72.54   72.57   72.47    72.3
   72.22    72.8   73.62   73.92   74.07   74.09   74.12   74.24   74.34   74.37
   74.39   74.45   74.51   74.51   74.85   74.77   74.77   74.54   74.03   73.78
   73.52   73.46   73.24   72.78   72.55   71.98   71.93   71.71    71.5   71.18
   71.14   71.78   73.77   73.83   74.47   74.93   74.56   75.88   80.48   80.46
   77.59   76.91    75.3   73.75   73.08   73.07   71.64   70.88   70.95   71.84
   71.73   71.65   71.57   71.48   71.27   69.11   69.22   68.21   68.55   69.77
    69.8    70.1   69.27   68.05   66.51   66.64   66.22   66.77   65.97   65.39
    65.3    65.6   63.73   72.91   73.25   73.17   67.56   68.83   69.71   68.88
   69.35   69.46    69.5   68.96   69.54   69.38   68.38   68.76   68.32   69.51
   69.87   71.67   73.66   73.72   74.36   74.82   74.45   75.77   80.37   80.36
Pier Skew, UpSta & Num, DnSta & Num=  ,4932.1, 2 ,4932.1, 2 , 0 , 0 , 0 ,,
       1       1
   63.84   74.19
       1       1
   63.64   73.99
Pier Skew, UpSta & Num, DnSta & Num=  ,4977.4, 2 ,4977.4, 2 , 0 , 0 , 0 ,,
       1       1
    59.9   74.26
       1       1
    59.7   74.06
Pier Skew, UpSta & Num, DnSta & Num=  ,5022.6, 2 ,5022.6, 2 , 0 , 0 , 0 ,,
       1       1
    59.9   74.33
       1       1
    59.7   74.13
Pier Skew, UpSta & Num, DnSta & Num=  ,5067.9, 2 ,5067.9, 2 , 0 , 0 , 0 ,,
       1       1
   65.22    74.4
       1       1
   65.02    74.2
Abutment Skew #Up #Dn= , 2 , 2
  4888.3  4909.5
   73.11   63.89
  4888.3  4909.5
   72.91   63.69
Abutment Skew #Up #Dn= , 2 , 2
  5090.5 5111.59
   67.03   73.37
  5090.5 5111.59
   66.83   73.17
BR Coef= 1 , 1 , 0 ,1.25, 0 ,,,0.8,0,2,0,
WSPro=,,,, 1 ,,,, 0 ,,,, 0 ,,,,-1 ,-1 ,-1 , 0 , 0 , 0 , 0 , 0
BR U #Sta/Elev= 91
  3627.3   77.79  3707.3   77.11  3957.3    75.5  4030.9   74.36  4040.9    74.2
  4057.3   73.95  4077.3   73.28  4087.3   73.27  4107.3   71.84  4137.3   71.08
  4157.3   71.15  4167.3   72.04  4180.9   71.93  4190.9   71.85  4200.9   71.77
  4210.9   71.68  4237.3   71.47  4257.3   69.31  4297.3   69.42  4357.3   68.41
  4360.9   68.47  4377.3   68.75  4407.3   69.97  4420.9      70  4540.9   70.28
  4547.3    70.3  4627.3   69.47  4657.3   68.25  4670.9    67.2  4677.3   66.71
  4687.3   66.84  4697.3   66.42  4757.3   66.97  4807.3   66.17  4817.3   65.59
  4827.3    65.5  4857.3    65.8  4887.3   63.94 4888.41   63.93  4888.5   63.93
  4900.9   63.86  4907.3   63.82  4909.5   63.89  4927.3   64.48  4957.3   66.97
    4964      64  4966.5    60.9  5033.5    60.9    5036      64  5047.9   65.54
  5090.5   67.03  5098.2    67.3 5111.39   67.76  5111.5   67.76  5147.9   69.03
  5227.9   69.91  5267.9   69.08  5307.9   69.55  5308.2   69.55  5358.2   69.66
  5377.9    69.7  5417.9   69.16  5437.9   69.74  5487.9   69.58  5488.2   69.57
  5517.9   68.58  5518.2   68.59  5537.9   68.96  5557.9   68.52  5585.9   69.35
  5597.9   69.71  5637.9   70.07  5675.9   71.87  5717.9   73.86  5727.9   73.92
  5735.9   74.43  5737.9   74.56  5775.9   74.78  5785.9   74.84  5792.5   74.88
  5795.9    74.9  5822.5   75.02  5835.9    74.9  5845.9    74.8  5862.5   74.65
  5902.5   75.97  6125.9   79.92  6135.9    80.1  6162.5   80.57  6185.9   80.57
  6223.5   80.56
BR U #Mann= 3
  3627.3     .13    4964    .043    5036     .13
BR U Banks=4964,5036
BR D #Sta/Elev= 91
  3627.3   77.59  3707.3   76.91  3957.3    75.3  4030.9   74.16  4040.9      74
  4057.3   73.75  4077.3   73.08  4087.3   73.07  4107.3   71.64  4137.3   70.88
  4157.3   70.95  4167.3   71.84  4180.9   71.73  4190.9   71.65  4200.9   71.57
  4210.9   71.48  4237.3   71.27  4257.3   69.11  4297.3   69.22  4357.3   68.21
  4360.9   68.27  4377.3   68.55  4407.3   69.77  4420.9    69.8  4540.9   70.08
  4547.3    70.1  4627.3   69.27  4657.3   68.05  4670.9      67  4677.3   66.51
  4687.3   66.64  4697.3   66.22  4757.3   66.77  4807.3   65.97  4817.3   65.39
  4827.3    65.3  4857.3    65.6  4887.3   63.74 4888.41   63.73  4888.5   63.73
  4900.9   63.66  4907.3   63.62  4909.5   63.69  4927.3   64.28  4957.3   66.77
    4964    63.8  4966.5    60.7  5033.5    60.7    5036    63.8  5047.9   65.34
  5090.5   66.83  5098.2    67.1 5111.39   67.56  5111.5   67.56  5147.9   68.83
  5227.9   69.71  5267.9   68.88  5307.9   69.35  5308.2   69.35  5358.2   69.46
  5377.9    69.5  5417.9   68.96  5437.9   69.54  5487.9   69.38  5488.2   69.37
  5517.9   68.38  5518.2   68.39  5537.9   68.76  5557.9   68.32  5585.9   69.15
  5597.9   69.51  5637.9   69.87  5675.9   71.67  5717.9   73.66  5727.9   73.72
  5735.9   74.23  5737.9   74.36  5775.9   74.58  5785.9   74.64  5792.5   74.68
  5795.9    74.7  5822.5   74.82  5835.9    74.7  5845.9    74.6  5862.5   74.45
  5902.5   75.77  6125.9   79.72  6135.9    79.9  6162.5   80.37  6185.9   80.37
  6223.5   80.36
BR D #Mann= 3
  3627.3     .13    4964    .043    5036     .13
BR D Banks=4964,5036
BC Design=,, 0 ,, 0 ,,,,,,
BC HTab HWMax=80.6
BC Use User HTab Curves=0
BC User HTab FreeFlow(D)= 0

Type RM Length L Ch R = 1 ,33269.1 ,454.9,454.9,454.9
BEGIN DESCRIPTION:
Downstream Section of Bridge/Culvert/Weir
END DESCRIPTION:
#Sta/Elev= 30
  3627.3   77.57  3957.3   75.28  4087.3   73.05  4137.3   70.86  4167.3   71.82
  4237.3   71.25  4257.3   69.09  4357.3   68.19  4407.3   69.75  4627.3   69.25
  4677.3   66.49  4857.3   65.58 4888.41   63.71  4927.3   64.26  4957.3   66.75
    4964   63.78  4966.5   60.68  5033.5   60.68    5036   63.78  5047.9   65.32
  5147.9   68.81  5227.9   69.69  5267.9   68.86  5437.9   69.52  5557.9    68.3
  5637.9   69.85  5737.9   74.34  5862.5   74.43  6162.5   80.35  6223.5   80.34
#Mann= 3 , 1 , 0
  3627.3     .13       0    4964    .043       0    5036     .13       0
#XS Ineff= 2 , 0
       0    4878      73    5122       0    71.2
Permanent Ineff=
       F       F
Bank Sta=4964,5036
XS Rating Curve= 0 ,0
Exp/Cntr=0.5,0.3

Type RM Length L Ch R = 1 ,32814.2 ,609.7,609.7,609.7
BEGIN DESCRIPTION:
Toisnot Swamp DS 31.0
END DESCRIPTION:
#Sta/Elev= 30
    3641   84.04    3801   74.13    3821   71.84    3911   68.91    4011   69.43
    4061   68.11  4359.9   70.41    4541   67.91    4621   68.49    4691   65.48
    4711   66.91    4871   67.66    4911   64.94  4961.9   64.35  4963.9   60.35
  5036.1   60.35  5038.1   64.35    5050   66.57    5120    69.2    5300   67.93
    5340   68.86    5470   66.02    5860   70.75    5890    72.6    5950   72.07
    6200   75.29    6370   74.62    6460   78.53    6480   77.19  6695.8   79.27
#Mann= 4 , 1 , 0
    3641      10       0  4359.9     .13       0  4961.9    .043       0
  5038.1     .13       0
Bank Sta=4961.9,5038.1
XS Rating Curve= 0 ,0
Exp/Cntr=0.3,0.1

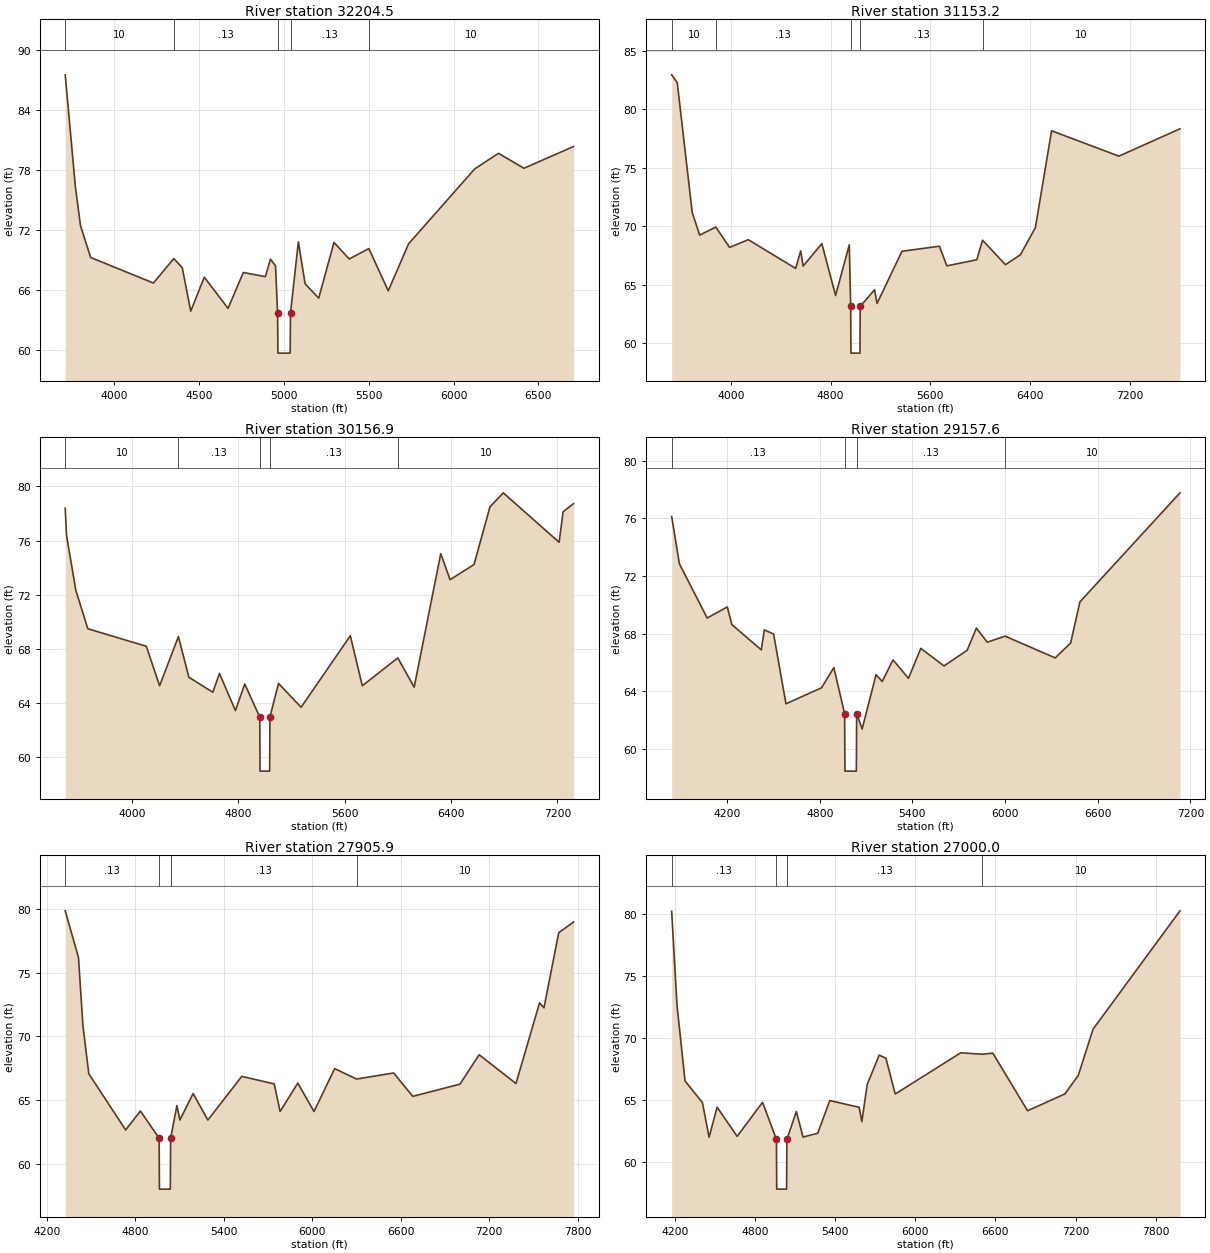
Type RM Length L Ch R = 1 ,32204.5 ,1051.3,1051.3,1051.3
BEGIN DESCRIPTION:
Toisnot Swamp DS 30.0
END DESCRIPTION:
#Sta/Elev= 30
  3709.8   87.52  3769.8   76.34  3799.8   72.47  3859.8   69.28  4229.8   66.73
  4349.9   69.17  4399.8   68.27  4449.8   63.92  4529.8   67.31  4669.8    64.2
  4759.8   67.78  4889.8   67.37  4919.8   69.11  4949.8   68.44  4961.9   63.73
  4963.9   59.73    5036   59.73    5038   63.73  5084.3   70.84  5124.3   66.65
  5204.3   65.22  5294.3   70.78  5384.3   69.13  5499.9   70.17  5614.3   65.95
  5734.3   70.65  6124.3   78.13  6264.3   79.68  6414.3   78.19  6706.6   80.36
#Mann= 5 , 1 , 0
  3709.8      10       0  4349.9     .13       0  4961.9    .043       0
    5038     .13       0  5499.9      10       0
Bank Sta=4961.9,5038
XS Rating Curve= 0 ,0
Exp/Cntr=0.3,0.1

Type RM Length L Ch R = 1 ,31153.2 ,996.3,996.3,996.3
BEGIN DESCRIPTION:
Toisnot Swamp DS 29.0
END DESCRIPTION:
#Sta/Elev= 30
    3526   82.96  3570.7   82.29  3690.7   71.18  3750.7   69.24  3879.9   69.93
  3990.7   68.19  4140.7   68.85  4520.7   66.39  4560.7   67.89  4580.7   66.59
  4730.7   68.51  4840.7   64.07  4950.7   68.41  4961.8   63.14  4963.8   59.14
  5036.2   59.14  5038.2   63.14  5153.4   64.56  5173.4   63.39  5373.4   67.86
  5673.4   68.29  5733.4   66.61  5973.4   67.13  6019.9    68.8  6203.4   66.71
  6323.4   67.56  6443.4   69.88  6573.4   78.17  7113.4      76  7603.4   78.34
#Mann= 5 , 1 , 0
    3526      10       0  3879.9     .13       0  4961.8    .043       0
  5038.2     .13       0  6019.9      10       0
Bank Sta=4961.8,5038.2
XS Rating Curve= 0 ,0
Exp/Cntr=0.3,0.1

Type RM Length L Ch R = 1 ,30156.9 ,999.3,999.3,999.3
BEGIN DESCRIPTION:
Toisnot Swamp DS 28.0
END DESCRIPTION:
#Sta/Elev= 30
  3498.7   78.39  3508.7   76.38  3578.7   72.31  3668.7   69.47  4108.7   68.17
  4208.7   65.25  4349.9   68.89  4428.7   65.88  4608.7   64.77  4658.7   66.16
  4778.7   63.41  4848.7   65.38  4961.8   62.93  4963.8   58.93  5036.1   58.93
  5038.1   62.93  5102.8   65.42  5272.8   63.66  5642.8   68.95  5732.8   65.25
  5999.9   67.31  6122.8   65.14  6322.8   75.03  6392.8    73.1  6572.8   74.22
  6692.8   78.49  6792.8   79.53  7212.8   75.87  7242.8   78.13  7321.2   78.73
#Mann= 5 , 1 , 0
  3498.7      10       0  4349.9     .13       0  4961.8    .043       0
  5038.1     .13       0  5999.9      10       0
Bank Sta=4961.8,5038.1
XS Rating Curve= 0 ,0
Exp/Cntr=0.3,0.1

Type RM Length L Ch R = 1 ,29157.6 ,1251.7,1251.7,1251.7
BEGIN DESCRIPTION:
Toisnot Swamp DS 27.0
END DESCRIPTION:
#Sta/Elev= 30
  3841.2   76.14  3891.2   72.85  4071.2   69.08  4201.2   69.85  4231.2   68.62
  4421.2   66.87  4441.2   68.25  4501.2   67.97  4581.2   63.12  4811.2   64.23
  4891.2   65.63    4961   62.44    4963   58.44    5037   58.44    5039   62.44
  5074.4   61.37  5164.4   65.14  5204.4   64.67  5274.4   66.17  5374.4   64.89
  5454.4   66.97  5604.4   65.75  5754.4   66.84  5814.4   68.38  5884.4    67.4
  5999.9   67.82  6324.4   66.31  6424.4   67.34  6484.4    70.2  7132.5   77.78
#Mann= 4 , 1 , 0
  3841.2     .13       0    4961    .043       0    5039     .13       0
  5999.9      10       0
Bank Sta=4961,5039
XS Rating Curve= 0 ,0
Exp/Cntr=0.3,0.1

Type RM Length L Ch R = 1 ,27905.9 ,905.9,905.9,905.9
BEGIN DESCRIPTION:
Toisnot Swamp DS 26.0
END DESCRIPTION:
#Sta/Elev= 30
  4323.9   79.86  4413.9    76.2  4443.9   70.86  4483.9   67.06  4733.9   62.64
  4833.9   64.13    4961   61.99    4963   57.99    5037   57.99    5039   61.99
  5081.7   64.56  5101.7   63.42  5191.7    65.5  5291.7   63.42  5521.7   66.85
  5741.7   66.26  5781.7   64.09  5901.7   66.32  6011.7   64.09  6151.7   67.46
  6299.9   66.64  6551.7   67.12  6681.7   65.28  7001.7   66.24  7131.7   68.55
  7381.7   66.29  7541.7   72.63  7571.7   72.24  7671.7   78.14  7772.1   78.98
#Mann= 4 , 1 , 0
  4323.9     .13       0    4961    .043       0    5039     .13       0
  6299.9      10       0
Bank Sta=4961,5039
XS Rating Curve= 0 ,0
Exp/Cntr=0.3,0.1

Type RM Length L Ch R = 1 ,27000.0 ,1087,1087,1087
BEGIN DESCRIPTION:
Toisnot Swamp DS 25.0
END DESCRIPTION:
#Sta/Elev= 30
    4177   80.21    4217   72.63    4277   66.55    4407   64.81    4457   62.02
    4517   64.44    4667   62.09    4857   64.83    4961   61.84    4963   57.84
    5037   57.84    5039   61.84    5110   64.09    5160   62.03    5270   62.34
    5360   64.97    5580   64.43    5600   63.28    5640   66.27    5730   68.63
    5780   68.38    5850    65.5    6340   68.82  6499.9    68.7    6580   68.79
    6840   64.15    7120   65.51    7220   67.01    7330   70.72  7980.6   80.25
#Mann= 4 , 1 , 0
    4177     .13       0    4961    .043       0    5039     .13       0
  6499.9      10       0
Bank Sta=4961,5039
XS Rating Curve= 0 ,0
Exp/Cntr=0.3,0.1

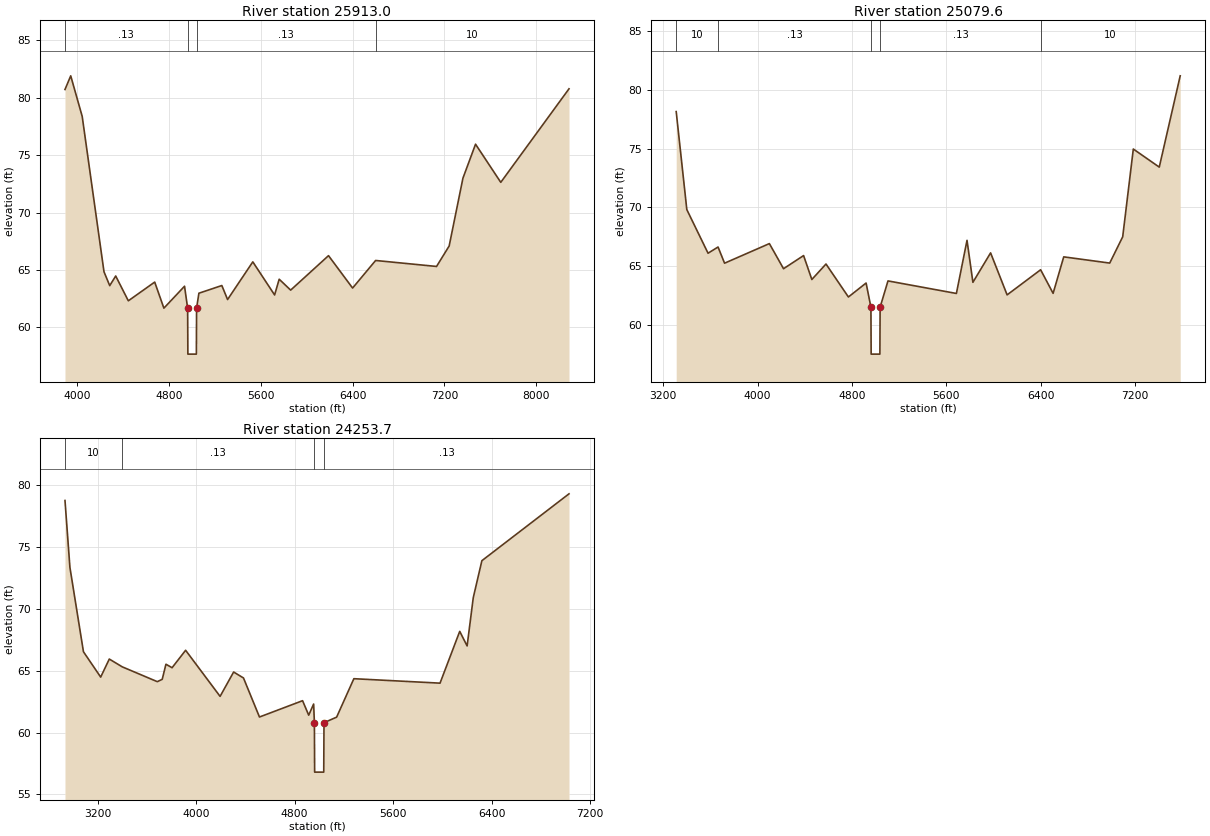
Type RM Length L Ch R = 1 ,25913.0 ,833.4,833.4,833.4
BEGIN DESCRIPTION:
Toisnot Swamp DS 24.0
END DESCRIPTION:
#Sta/Elev= 30
  3891.7   80.71  3941.7    81.9  4041.7   78.37  4231.7   64.85  4281.7   63.64
  4333.9   64.48  4443.9   62.32  4673.9   63.95  4753.9   61.68  4933.9   63.59
    4961   61.68    4963   57.68    5037   57.68    5039   61.68  5059.2   62.98
  5259.2   63.65  5309.2   62.43  5529.2   65.71  5719.2   62.83  5759.2    64.2
  5859.2   63.25  6189.2   66.25  6399.2   63.43  6599.9   65.83  7131.1   65.31
  7241.1   67.09  7361.1   72.99  7471.1   75.95  7691.1   72.63  8285.9   80.77
#Mann= 4 , 1 , 0
  3891.7     .13       0    4961    .043       0    5039     .13       0
  6599.9      10       0
Bank Sta=4961,5039
XS Rating Curve= 0 ,0
Exp/Cntr=0.3,0.1

Type RM Length L Ch R = 1 ,25079.6 ,825.9,825.9,825.9
BEGIN DESCRIPTION:
Toisnot Swamp DS 23.0
END DESCRIPTION:
#Sta/Elev= 30
  3310.1   78.16  3400.1   69.81  3580.1   66.09  3664.9   66.62  3720.1   65.24
  4100.1   66.91  4220.1   64.77  4390.1   65.89  4460.1   63.85  4580.1   65.17
  4770.1   62.36  4920.1   63.55    4961   61.49    4963   57.49    5037   57.49
    5039   61.49  5105.7   63.73  5685.7   62.66  5775.7   67.19  5825.7   63.61
  5975.7   66.12  6115.7   62.54  6399.9   64.68  6505.7   62.67  6595.7   65.78
  6985.7   65.25  7095.7   67.49  7185.7   74.97  7405.7   73.43  7583.3   81.21
#Mann= 5 , 1 , 0
  3310.1      10       0  3664.9     .13       0    4961    .043       0
    5039     .13       0  6399.9      10       0
Bank Sta=4961,5039
XS Rating Curve= 0 ,0
Exp/Cntr=0.3,0.1

Type RM Length L Ch R = 1 ,24253.7 ,1054.5,1054.5,1054.5
BEGIN DESCRIPTION:
Toisnot Swamp DS 22.0
END DESCRIPTION:
#Sta/Elev= 30
  2934.9   78.78  2974.9   73.37  3084.9   66.54  3224.9   64.49  3294.9   65.95
  3399.9   65.32  3684.9   64.12  3724.9   64.31  3754.9   65.53  3804.9   65.25
  3914.9   66.66  4194.9   62.93  4304.9    64.9  4384.9   64.42  4514.9   61.26
  4864.9   62.58  4914.9   61.41  4954.9   62.31    4961    60.8    4963    56.8
    5037    56.8    5039    60.8  5141.7   61.25  5281.7   64.36  5981.7      64
  6141.7   68.19  6201.7   67.01  6251.7   70.92  6321.7   73.91  7029.4   79.32
#Mann= 4 , 1 , 0
  2934.9      10       0  3399.9     .13       0    4961    .043       0
    5039     .13       0
Bank Sta=4961,5039
XS Rating Curve= 0 ,0
Exp/Cntr=0.3,0.1