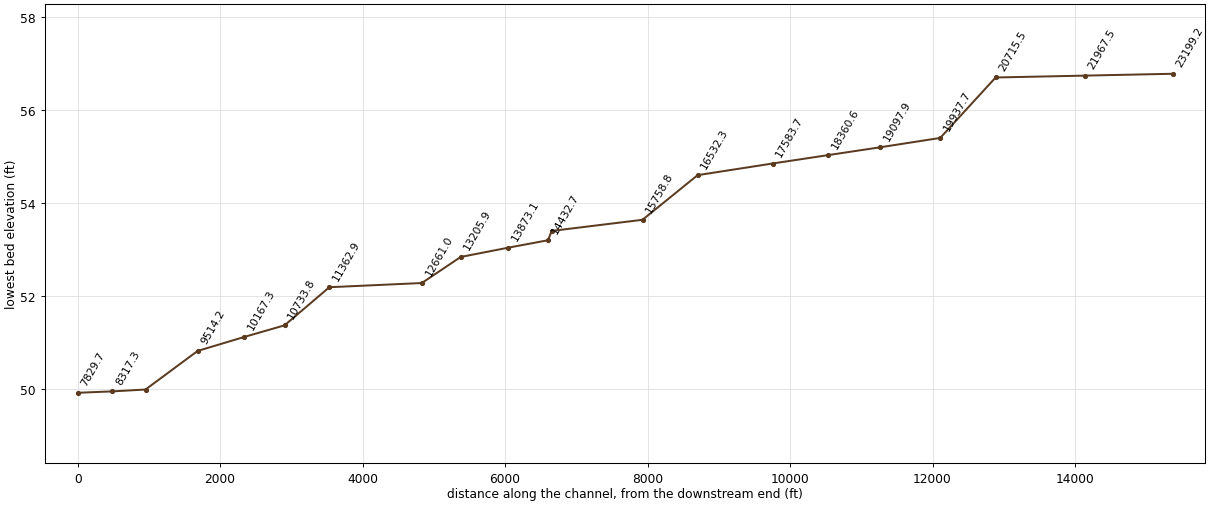
HEC-RAS study Toisnot_Swamp_DS_021220.prj: Toisnot Swamp DS

--- Toisnot_Swamp_DS_021220.g01 (geometry) --- (continued)

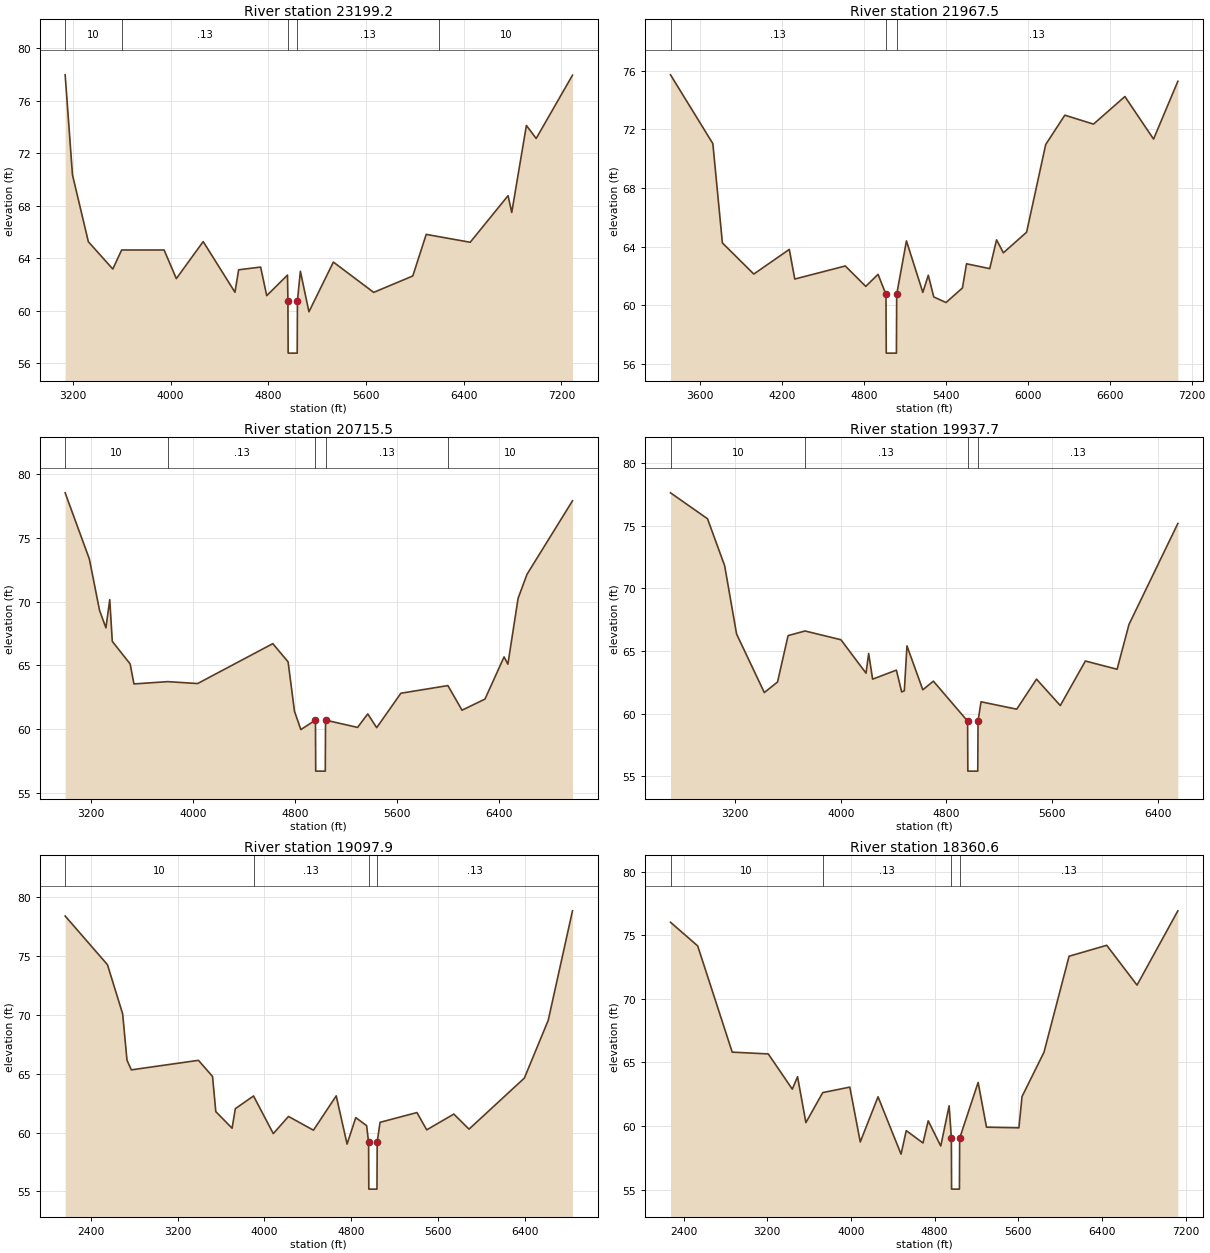
Type RM Length L Ch R = 1 ,23199.2 ,1231.7,1231.7,1231.7
BEGIN DESCRIPTION:
Toisnot Swamp DS 21.0
END DESCRIPTION:
#Sta/Elev= 30
  3137.6   77.99  3197.6   70.36  3327.6   65.27  3527.6   63.19  3599.9   64.64
  3947.6   64.64  4047.6   62.46  4267.6   65.28  4527.6   61.42  4557.6   63.13
  4737.6   63.34  4787.6   61.16  4957.6   62.73    4961   60.78    4963   56.78
    5037   56.78    5039   60.78  5063.1   63.02  5133.1   59.93  5333.1   63.72
  5663.1   61.41  5983.1   62.66  6093.1   65.83  6199.9   65.65  6453.1   65.23
  6763.1   68.78  6793.1    67.5  6913.1   74.13  6993.1   73.14  7290.3   77.96
#Mann= 5 , 1 , 0
  3137.6      10       0  3599.9     .13       0    4961    .043       0
    5039     .13       0  6199.9      10       0
Bank Sta=4961,5039
XS Rating Curve= 0 ,0
Exp/Cntr=0.3,0.1

Type RM Length L Ch R = 1 ,21967.5 ,1252,1252,1252
BEGIN DESCRIPTION:
Toisnot Swamp DS 20.0
END DESCRIPTION:
#Sta/Elev= 30
  3382.7   75.71  3692.7   71.02  3762.7   64.25  3992.7   62.13  4252.7   63.81
  4292.7   61.79  4662.7   62.68  4812.7   61.29  4902.7   62.11  4960.8   60.74
  4962.8   56.74  5037.2   56.74  5039.2   60.74  5110.7   64.39  5230.7   60.88
  5270.7   62.05  5310.7   60.57  5400.7   60.19  5520.7   61.18  5550.7   62.83
  5720.7    62.5  5770.7   64.46  5820.7   63.58  5990.7   64.98  6130.7   70.96
  6270.7   72.96  6480.7   72.35  6710.7   74.23  6920.7   71.33  7098.6   75.27
#Mann= 3 , 1 , 0
  3382.7     .13       0  4960.8    .043       0  5039.2     .13       0
Bank Sta=4960.8,5039.2
XS Rating Curve= 0 ,0
Exp/Cntr=0.3,0.1

Type RM Length L Ch R = 1 ,20715.5 ,777.8,777.8,777.8
BEGIN DESCRIPTION:
Toisnot Swamp DS 18.0
END DESCRIPTION:
#Sta/Elev= 30
  2995.6   78.53  3185.6   73.34  3265.6   69.31  3315.6   67.94  3345.6   70.15
  3365.6   66.88  3505.6   65.11  3535.6   63.54  3799.9   63.72  4035.6   63.57
  4625.6    66.7  4745.6   65.27  4795.6    61.4  4845.6   59.96  4960.4    60.7
  4962.4    56.7  5037.5    56.7  5039.5    60.7  5290.9   60.13  5370.9   61.19
  5440.9   60.11  5630.9   62.81  5999.9   63.41  6110.9   61.48  6290.9   62.35
  6440.9   65.66  6470.9   65.09  6550.9   70.25  6620.9   72.14  6977.9    77.9
#Mann= 5 , 1 , 0
  2995.6      10       0  3799.9     .13       0  4960.4    .044       0
  5039.5     .13       0  5999.9      10       0
Bank Sta=4960.4,5039.5
XS Rating Curve= 0 ,0
Exp/Cntr=0.3,0.1

Type RM Length L Ch R = 1 ,19937.7 ,839.8,839.8,839.8
BEGIN DESCRIPTION:
Toisnot Swamp DS 17.0
END DESCRIPTION:
#Sta/Elev= 30
  2711.6   77.64  2991.6   75.57  3121.6   71.81  3211.6   66.36  3421.6   61.68
  3521.6   62.52  3601.6   66.23  3729.9    66.6  4001.6    65.9  4191.6   63.23
  4211.6    64.8  4241.6   62.75  4421.6   63.47  4461.6   61.73  4481.6   61.82
  4501.6   65.41  4621.6    61.9  4701.6   62.59  4960.5    59.4  4962.5    55.4
  5037.6    55.4  5039.6    59.4  5062.4   60.94  5332.4   60.35  5482.4   62.75
  5662.4   60.64  5852.4    64.2  6092.4   63.54  6182.4   67.12  6552.4   75.19
#Mann= 4 , 1 , 0
  2711.6      10       0  3729.9     .13       0  4960.5    .044       0
  5039.6     .13       0
Bank Sta=4960.5,5039.6
XS Rating Curve= 0 ,0
Exp/Cntr=0.3,0.1

Type RM Length L Ch R = 1 ,19097.9 ,737.3,737.3,737.3
BEGIN DESCRIPTION:
Toisnot Swamp DS 16.0
END DESCRIPTION:
#Sta/Elev= 30
  2163.6   78.42  2553.6   74.28  2693.6    70.1  2733.6   66.16  2773.6   65.34
  3392.1   66.15  3522.1   64.78  3552.1   61.79  3702.1   60.38  3732.1   62.04
  3899.9   63.12  4082.1   59.92  4222.1   61.38  4452.1   60.21  4662.1   63.13
  4762.1   59.03  4842.1   61.28  4942.1    60.6  4960.4    59.2  4962.4    55.2
  5037.6    55.2  5039.6    59.2  5066.1   60.88  5406.1   61.71  5496.1   60.24
  5746.1   61.58  5886.1    60.3  6396.1   64.64  6616.1   69.55  6839.7   78.86
#Mann= 4 , 1 , 0
  2163.6      10       0  3899.9     .13       0  4960.4    .044       0
  5039.6     .13       0
Bank Sta=4960.4,5039.6
XS Rating Curve= 0 ,0
Exp/Cntr=0.3,0.1

Type RM Length L Ch R = 1 ,18360.6 ,776.9,776.9,776.9
BEGIN DESCRIPTION:
Toisnot Swamp DS 15.0
END DESCRIPTION:
#Sta/Elev= 30
  2273.9   76.01  2533.9   74.15  2863.9    65.8  3208.9   65.66  3438.9   62.89
  3488.9   63.87  3568.9   60.26  3729.9   62.62  3988.9   63.05  4088.9   58.74
  4258.9   62.29  4478.9   57.78  4528.9   59.63  4688.9   58.66  4738.9    60.4
  4858.9   58.42  4938.9   61.58  4960.4   59.03  4962.4   55.03  5037.6   55.03
  5039.6   59.03  5216.3   63.42  5296.3    59.9  5606.3   59.85  5636.3   62.31
  5846.3   65.79  6086.3   73.34  6446.3    74.2  6736.3   71.07  7126.8   76.91
#Mann= 4 , 1 , 0
  2273.9      10       0  3729.9     .13       0  4960.4    .044       0
  5039.6     .13       0
Bank Sta=4960.4,5039.6
XS Rating Curve= 0 ,0
Exp/Cntr=0.3,0.1

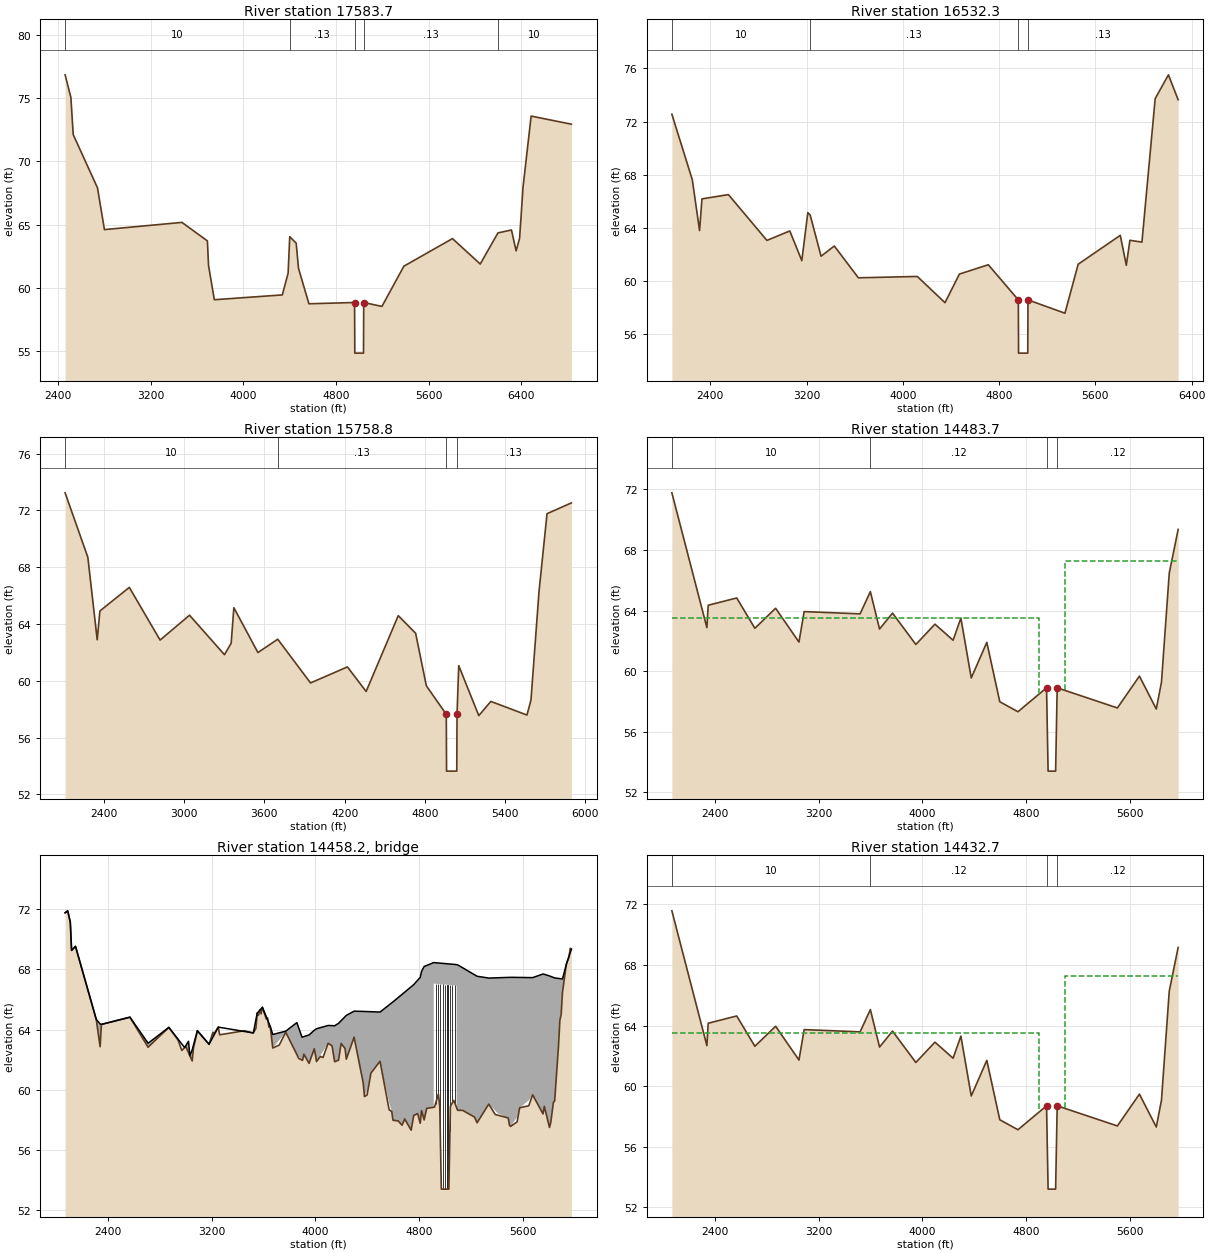
Type RM Length L Ch R = 1 ,17583.7 ,1051.4,1051.4,1051.4
BEGIN DESCRIPTION:
Toisnot Swamp DS 14.0
END DESCRIPTION:
#Sta/Elev= 30
  2457.9   76.84  2507.9   75.06  2527.9   72.12  2737.9   67.91  2797.9   64.61
  3467.9   65.18  3687.9   63.72  3697.9   61.78  3747.9   59.07  4335.7   59.45
  4385.7   61.16  4399.9   64.05  4455.7   63.54  4475.7   61.55  4565.7   58.75
  4960.4   58.85  4962.4   54.85  5037.6   54.85  5039.6   58.85  5196.8   58.54
  5386.8   61.72  5806.8    63.9  6046.8   61.89  6199.9   64.35  6316.8   64.58
  6356.8   62.93  6386.8   63.91  6416.8   67.97  6486.8   73.58  6834.6   72.94
#Mann= 5 , 1 , 0
  2457.9      10       0  4399.9     .13       0  4960.4    .044       0
  5039.6     .13       0  6199.9      10       0
Bank Sta=4960.4,5039.6
XS Rating Curve= 0 ,0
Exp/Cntr=0.3,0.1

Type RM Length L Ch R = 1 ,16532.3 ,773.5,773.5,773.5
BEGIN DESCRIPTION:
Toisnot Swamp DS 13.0
END DESCRIPTION:
#Sta/Elev= 30
  2080.2   72.55  2250.2   67.62  2310.2   63.81  2330.2   66.19  2550.2   66.51
  2870.2   63.07  3060.2   63.78  3160.2   61.55  3210.2   65.16  3229.9   64.97
  3320.2   61.88  3430.2   62.65  3630.2   60.26  4120.2   60.36  4350.2   58.39
  4470.2   60.54  4710.2   61.24  4959.8    58.6  4961.8    54.6  5038.1    54.6
  5040.1    58.6  5347.2    57.6  5457.2   61.28  5807.2   63.45  5857.2    61.2
  5887.2   63.08  5987.2   62.94  6097.2   73.72  6207.2   75.51  6288.1   73.64
#Mann= 4 , 1 , 0
  2080.2      10       0  3229.9     .13       0  4959.8    .044       0
  5040.1     .13       0
Bank Sta=4959.8,5040.1
XS Rating Curve= 0 ,0
Exp/Cntr=0.3,0.1

Type RM Length L Ch R = 1 ,15758.8 ,1275.1,1275.1,1275.1
BEGIN DESCRIPTION:
Toisnot Swamp DS 12.0
END DESCRIPTION:
#Sta/Elev= 30
  2110.6   73.24  2280.6    68.7  2350.6   62.89  2370.6   64.92  2590.6   66.58
  2820.6   62.87  3040.6   64.62  3301.9   61.84  3351.9   62.65  3371.9   65.15
  3551.9   61.99  3699.9   62.93  3945.1   59.85  4220.7   60.98  4360.7   59.25
  4600.7   64.59  4730.7   63.35  4810.7   59.65  4959.8   57.64  4961.8   53.64
  5038.1   53.64  5040.1   57.64  5052.8   61.07  5202.8   57.55  5292.8   58.55
  5562.8   57.59  5592.8   58.65  5652.8   66.28  5712.8   71.77  5894.7   72.53
#Mann= 4 , 1 , 0
  2110.6      10       0  3699.9     .13       0  4959.8    .044       0
  5040.1     .13       0
Bank Sta=4959.8,5040.1
XS Rating Curve= 0 ,0
Exp/Cntr=0.5,0.3

Type RM Length L Ch R = 1 ,14483.7 ,51,51,51
BEGIN DESCRIPTION:
Upstream Section of Bridge/Culvert/Weir
END DESCRIPTION:
#Sta/Elev= 30
  2069.3   71.77  2339.3   62.87  2349.3   64.35  2569.3   64.83  2709.3   62.83
  2869.3   64.15  3049.3   61.92  3089.3   63.93  3520.7   63.78  3599.9   65.25
  3670.7   62.78  3770.7   63.83  3950.7   61.76  4097.9    63.1  4237.9   62.04
  4297.9    63.5  4377.9   59.55  4497.9    61.9  4597.9   57.98  4737.9   57.32
  4958.5    58.9  4970.5    53.4  5028.5    53.4  5040.5    58.9  5504.7   57.57
  5674.7   59.67  5804.7    57.5  5844.7   59.27  5904.7   66.47  5973.3   69.35
#Mann= 4 , 1 , 0
  2069.3      10       0  3599.9     .12       0  4958.5    .042       0
  5040.5     .12       0
#XS Ineff= 2 , 0
       0    4902    63.5    5098       0    67.3
Permanent Ineff=
       F       F
Bank Sta=4958.5,5040.5
XS Rating Curve= 0 ,0
Exp/Cntr=0.5,0.3

Type RM Length L Ch R = 3 ,14458.2 ,,,
BEGIN DESCRIPTION:
NC 222-TOR
Structure ID: NC 222
Approximate Survey Structure
END DESCRIPTION:
Bridge Culvert--1,0,-1,-1, 0
Deck Dist Width WeirC Skew NumUp NumDn MinLoCord MaxHiCord MaxSubmerge Is_Ogee
10,31,2.6,0, 60, 60, , , 0.95, 0, 1,1,,
  2069.3  2089.3  2109.3  2119.3  2149.3  2309.3  2339.3  2349.3  2569.3  2709.3
  2869.3    2991    3021    3031  3049.3  3089.3  3179.3  3250.7  3520.7  3550.7
  3590.7  3650.7  3670.7  3770.7  3856.3  3896.3  3950.7  3990.7  4007.9  4097.9
  4147.9  4177.9  4197.9  4237.9  4297.9  4377.9  4497.9  4597.9  4737.9  4757.9
  4807.9  4817.9  4837.9 4911.91    4912    5083 5087.89    5088  5096.3  5246.3
  5336.3  5504.7  5674.7  5754.7  5764.7  5804.7  5844.7  5904.7  5934.7  5973.3
   71.77    71.9   71.15   69.27   69.54   64.69   64.38   64.35   64.83    63.1
   64.15   62.81   63.23   62.27   62.66   63.93   63.03   64.17   63.78    65.1
   65.49   64.23   63.68    63.9   64.47    63.5   63.65   63.96   64.06   64.28
   64.26   64.42    64.6   64.95   65.23   65.21   65.17   65.85   66.85      67
   67.48   67.87    68.2   68.46   68.46   68.33   68.32   68.32   68.31   67.55
   67.43   67.48   67.46    67.7   67.68   67.57   67.44   67.37   68.35   69.35
   71.77    71.9   71.15   69.27   69.54   64.69   62.87   64.35   64.83   62.83
   64.15   62.81   62.46   62.27   61.92   63.93   63.03   64.17   63.78    65.1
   65.49   64.23   62.78   63.83   62.35   61.98   61.76   62.73   61.88    63.1
   61.87   61.97   63.08   62.04    63.5   59.55    61.9   57.98   57.32    58.3
   57.78   58.62      58   58.84   67.06   66.93   66.92   58.82   58.64   57.81
   59.05   57.57   59.67    58.4    58.9    57.5   59.27   66.47   68.35   69.35
  2069.3  2089.3  2109.3  2119.3  2149.3  2309.3  2339.3  2349.3  2569.3  2709.3
  2869.3    2991    3021    3031  3049.3  3089.3  3179.3  3250.7  3520.7  3540.7
  3550.7  3590.7  3650.7  3670.7  3770.7  3856.3  3896.3  3950.7  3990.7  4007.9
  4097.9  4147.9  4177.9  4197.9  4237.9  4297.9  4377.9  4497.9  4597.9  4737.9
  4757.9  4807.9  4817.9  4837.9 4911.91    4912    5083 5087.89    5088  5096.3
  5246.3  5336.3  5504.7  5674.7  5764.7  5804.7  5844.7  5904.7  5934.7  5973.3
   71.67    71.8   71.05   69.17   69.44    64.6   64.38   64.35   64.74    63.1
   64.06   62.75   63.23   62.18   62.66   63.84   62.94   64.08   63.77   63.99
   65.01    65.4   64.14   63.68    63.9   64.47    63.5   63.65   63.96   64.06
   64.28   64.26   64.42    64.6   64.95   65.23   65.21   65.17   65.85   66.85
      67   67.48   67.87    68.2   68.46   68.46   68.33   68.32   68.32   68.31
   67.55   67.43   67.48   67.46   67.68   67.57   67.44   67.37   68.25   69.25
   71.57    71.7   70.95   69.07   69.34   64.49   62.67   64.15   64.63   62.63
   63.95   62.61   62.26   62.07   61.72   63.73   62.83   63.97   63.58   63.88
    64.9   65.29   64.03   62.58   63.63   62.15   61.78   61.56   62.53   61.68
    62.9   61.67   61.77   62.88   61.84    63.3   59.35    61.7   57.78   57.12
    58.1   57.58   58.42    57.8   58.64   66.86   66.73   66.72   58.62   58.44
   57.61   58.85   57.37   59.47    58.7    57.3   59.07   66.27   68.15   69.15
Pier Skew, UpSta & Num, DnSta & Num=  ,4926.2, 2 ,4926.2, 2 , 0 , 0 , 0 ,,
       1       1
   58.08   68.04
       1       1
   57.88   67.84
Pier Skew, UpSta & Num, DnSta & Num=  ,4944.6, 2 ,4944.6, 2 , 0 , 0 , 0 ,,
       1       1
   58.61   68.03
       1       1
   58.41   67.83
Pier Skew, UpSta & Num, DnSta & Num=  ,4963.1, 2 ,4963.1, 2 , 0 , 0 , 0 ,,
       1       1
   55.56   68.02
       1       1
   55.36   67.82
Pier Skew, UpSta & Num, DnSta & Num=  ,4981.5, 2 ,4981.5, 2 , 0 , 0 , 0 ,,
       1       1
    52.4      68
       1       1
    52.2    67.8
Pier Skew, UpSta & Num, DnSta & Num=  ,5000, 2 ,5000, 2 , 0 , 0 , 0 ,,
       1       1
    52.4   67.99
       1       1
    52.2   67.79
Pier Skew, UpSta & Num, DnSta & Num=  ,5018.4, 2 ,5018.4, 2 , 0 , 0 , 0 ,,
       1       1
    52.4   67.98
       1       1
    52.2   67.78
Pier Skew, UpSta & Num, DnSta & Num=  ,5036.9, 2 ,5036.9, 2 , 0 , 0 , 0 ,,
       1       1
   56.02   67.96
       1       1
   55.82   67.76
Pier Skew, UpSta & Num, DnSta & Num=  ,5055.3, 2 ,5055.3, 2 , 0 , 0 , 0 ,,
       1       1
   58.12   67.95
       1       1
   57.92   67.75
Pier Skew, UpSta & Num, DnSta & Num=  ,5073.8, 2 ,5073.8, 2 , 0 , 0 , 0 ,,
       1       1
   58.12   67.94
       1       1
   57.92   67.74
Abutment Skew #Up #Dn= , 2 , 2
  4911.8    4917
   67.06   58.85
  4911.8    4917
   66.86   58.65
Abutment Skew #Up #Dn= , 2 , 2
    5083 5088.09
   58.93   66.92
    5083 5088.09
   58.73   66.72
BR Coef= 1 , 1 , 0 ,1.25, 0 ,,,0.8,0,2,0,
WSPro=,,,, 1 ,,,, 0 ,,,, 0 ,,,,-1 ,-1 ,-1 , 0 , 0 , 0 , 0 , 0
BR U #Sta/Elev= 164
  2069.3   71.77  2089.3    71.9  2109.3   71.15  2119.3   69.27  2149.3   69.54
    2161   69.19  2309.3   64.69  2339.3   62.87  2349.3   64.35  2569.3   64.83
  2709.3   62.83    2721   62.93    2771   63.34    2801   63.59  2869.3   64.15
    2871   64.13    2901   63.78  2939.3   63.33    2951   63.05  2969.3   62.62
    2991   62.81  2999.3   62.88    3001   62.85    3021   62.46    3031   62.27
  3049.3   61.92    3051   62.07  3059.3   62.78  3089.3   63.93    3131   63.51
    3161   63.21  3179.3   63.03  3209.3   63.83  3210.7   63.63    3211   63.63
  3250.7   64.17    3251   64.15  3260.7   63.66    3261   63.66    3281   63.69
  3326.3   63.75  3450.7   63.93  3520.7   63.78  3540.7   64.08  3550.7    65.1
  3560.7   64.96  3570.7   65.31  3580.7   65.05  3590.7   65.49  3599.9   65.25
  3620.7   64.71  3630.7   64.78  3640.7   64.17  3650.7   64.23  3670.7   62.78
  3686.3   62.84  3720.7   62.98  3770.7   63.83  3796.3   63.39  3806.3   63.22
  3830.7   62.81  3856.3   62.35  3870.7   62.09  3896.3   61.98  3900.7   61.96
  3910.7   62.37  3926.3   62.13  3950.7   61.76  3979.9   62.47  3990.7   62.73
  3997.9   62.41  4007.9   61.88  4037.9   62.22  4049.9   62.18  4057.9   62.15
  4097.9    63.1  4127.9   62.92  4147.9   61.87  4159.9   61.91  4177.9   61.97
  4197.9   63.08  4227.9   62.75  4237.9   62.04  4269.9   62.82  4297.9    63.5
  4367.9   60.47  4377.9   59.55  4397.9   59.66  4427.9   61.11  4497.9    61.9
  4499.9   61.81  4529.9   60.43  4539.9   59.97  4567.9   58.68  4587.9   58.56
  4597.9   57.98  4619.9   57.95  4629.9   57.94  4637.9   57.93  4667.9   57.65
  4679.9    57.9  4687.9   58.06  4689.9   58.03  4737.9   57.32  4749.9   57.91
  4757.9    58.3  4787.9   58.42  4807.9   57.78  4809.9   57.95  4817.9   58.62
  4819.9   58.56  4837.9      58  4857.9   58.77  4859.9   58.77 4911.91   58.84
    4912   58.84    4917   58.85  4917.9   58.85  4947.9   59.72  4958.5    58.9
  4970.5    53.4  5028.5    53.4  5040.5    58.9  5066.3    59.3    5083   58.93
 5087.89   58.83    5088   58.82  5096.3   58.64  5115.1   58.64  5136.3   58.63
  5155.1   58.54  5185.1   58.39  5226.3   58.19  5246.3   57.81  5336.3   59.05
  5386.3   58.36  5405.1   58.32  5486.3   58.13  5496.3   57.64  5504.7   57.57
  5554.7   57.87  5574.7   58.81  5644.7   58.94  5655.1   59.19  5669.7   59.55
  5674.7   59.67  5719.7   58.96  5754.7    58.4  5764.7    58.9  5804.7    57.5
  5809.7   57.67  5814.7   57.84  5834.7   59.16  5844.7   59.27  5874.7   62.98
  5884.7   64.62  5894.7   65.02  5899.7   65.74  5904.7   66.47  5909.7   66.78
  5934.7   68.35  5954.7   68.83  5964.7   69.41  5973.3   69.35
BR U #Mann= 4
  2069.3      10  3599.9     .12  4958.5    .042  5040.5     .12
BR U Banks=4958.5,5040.5
BR D #Sta/Elev= 164
  2069.3   71.57  2089.3    71.7  2109.3   70.95  2119.3   69.07  2149.3   69.34
    2161   68.99  2309.3   64.49  2339.3   62.67  2349.3   64.15  2569.3   64.63
  2709.3   62.63    2721   62.73    2771   63.14    2801   63.39  2869.3   63.95
    2871   63.93    2901   63.58  2939.3   63.13    2951   62.85  2969.3   62.42
    2991   62.61  2999.3   62.68    3001   62.65    3021   62.26    3031   62.07
  3049.3   61.72    3051   61.87  3059.3   62.58  3089.3   63.73    3131   63.31
    3161   63.01  3179.3   62.83  3209.3   63.63  3210.7   63.43    3211   63.43
  3250.7   63.97    3251   63.95  3260.7   63.46    3261   63.46    3281   63.49
  3326.3   63.55  3450.7   63.73  3520.7   63.58  3540.7   63.88  3550.7    64.9
  3560.7   64.76  3570.7   65.11  3580.7   64.85  3590.7   65.29  3599.9   65.05
  3620.7   64.51  3630.7   64.58  3640.7   63.97  3650.7   64.03  3670.7   62.58
  3686.3   62.64  3720.7   62.78  3770.7   63.63  3796.3   63.19  3806.3   63.02
  3830.7   62.61  3856.3   62.15  3870.7   61.89  3896.3   61.78  3900.7   61.76
  3910.7   62.17  3926.3   61.93  3950.7   61.56  3979.9   62.27  3990.7   62.53
  3997.9   62.21  4007.9   61.68  4037.9   62.02  4049.9   61.98  4057.9   61.95
  4097.9    62.9  4127.9   62.72  4147.9   61.67  4159.9   61.71  4177.9   61.77
  4197.9   62.88  4227.9   62.55  4237.9   61.84  4269.9   62.62  4297.9    63.3
  4367.9   60.27  4377.9   59.35  4397.9   59.46  4427.9   60.91  4497.9    61.7
  4499.9   61.61  4529.9   60.23  4539.9   59.77  4567.9   58.48  4587.9   58.36
  4597.9   57.78  4619.9   57.75  4629.9   57.74  4637.9   57.73  4667.9   57.45
  4679.9    57.7  4687.9   57.86  4689.9   57.83  4737.9   57.12  4749.9   57.71
  4757.9    58.1  4787.9   58.22  4807.9   57.58  4809.9   57.75  4817.9   58.42
  4819.9   58.36  4837.9    57.8  4857.9   58.57  4859.9   58.57 4911.91   58.64
    4912   58.64    4917   58.65  4917.9   58.65  4947.9   59.52  4958.5    58.7
  4970.5    53.2  5028.5    53.2  5040.5    58.7  5066.3    59.1    5083   58.73
 5087.89   58.63    5088   58.62  5096.3   58.44  5115.1   58.44  5136.3   58.43
  5155.1   58.34  5185.1   58.19  5226.3   57.99  5246.3   57.61  5336.3   58.85
  5386.3   58.16  5405.1   58.12  5486.3   57.93  5496.3   57.44  5504.7   57.37
  5554.7   57.67  5574.7   58.61  5644.7   58.74  5655.1   58.99  5669.7   59.35
  5674.7   59.47  5719.7   58.76  5754.7    58.2  5764.7    58.7  5804.7    57.3
  5809.7   57.47  5814.7   57.64  5834.7   58.96  5844.7   59.07  5874.7   62.78
  5884.7   64.42  5894.7   64.82  5899.7   65.54  5904.7   66.27  5909.7   66.58
  5934.7   68.15  5954.7   68.63  5964.7   69.21  5973.3   69.15
BR D #Mann= 4
  2069.3      10  3599.9     .12  4958.5    .042  5040.5     .12
BR D Banks=4958.5,5040.5
BC Design=,, 0 ,, 0 ,,,,,,
BC HTab HWMax=71.9
BC Use User HTab Curves=0
BC User HTab FreeFlow(D)= 0

Type RM Length L Ch R = 1 ,14432.7 ,559.6,559.6,559.6
BEGIN DESCRIPTION:
Downstream Section of Bridge/Culvert/Weir
END DESCRIPTION:
#Sta/Elev= 30
  2069.3   71.57  2339.3   62.67  2349.3   64.15  2569.3   64.63  2709.3   62.63
  2869.3   63.95  3049.3   61.72  3089.3   63.73  3520.7   63.58  3599.9   65.05
  3670.7   62.58  3770.7   63.63  3950.7   61.56  4097.9    62.9  4237.9   61.84
  4297.9    63.3  4377.9   59.35  4497.9    61.7  4597.9   57.78  4737.9   57.12
  4958.5    58.7  4970.5    53.2  5028.5    53.2  5040.5    58.7  5504.7   57.37
  5674.7   59.47  5804.7    57.3  5844.7   59.07  5904.7   66.27  5973.3   69.15
#Mann= 4 , 1 , 0
  2069.3      10       0  3599.9     .12       0  4958.5    .042       0
  5040.5     .12       0
#XS Ineff= 2 , 0
       0    4902    63.5    5098       0    67.3
Permanent Ineff=
       F       F
Bank Sta=4958.5,5040.5
XS Rating Curve= 0 ,0
Exp/Cntr=0.5,0.3

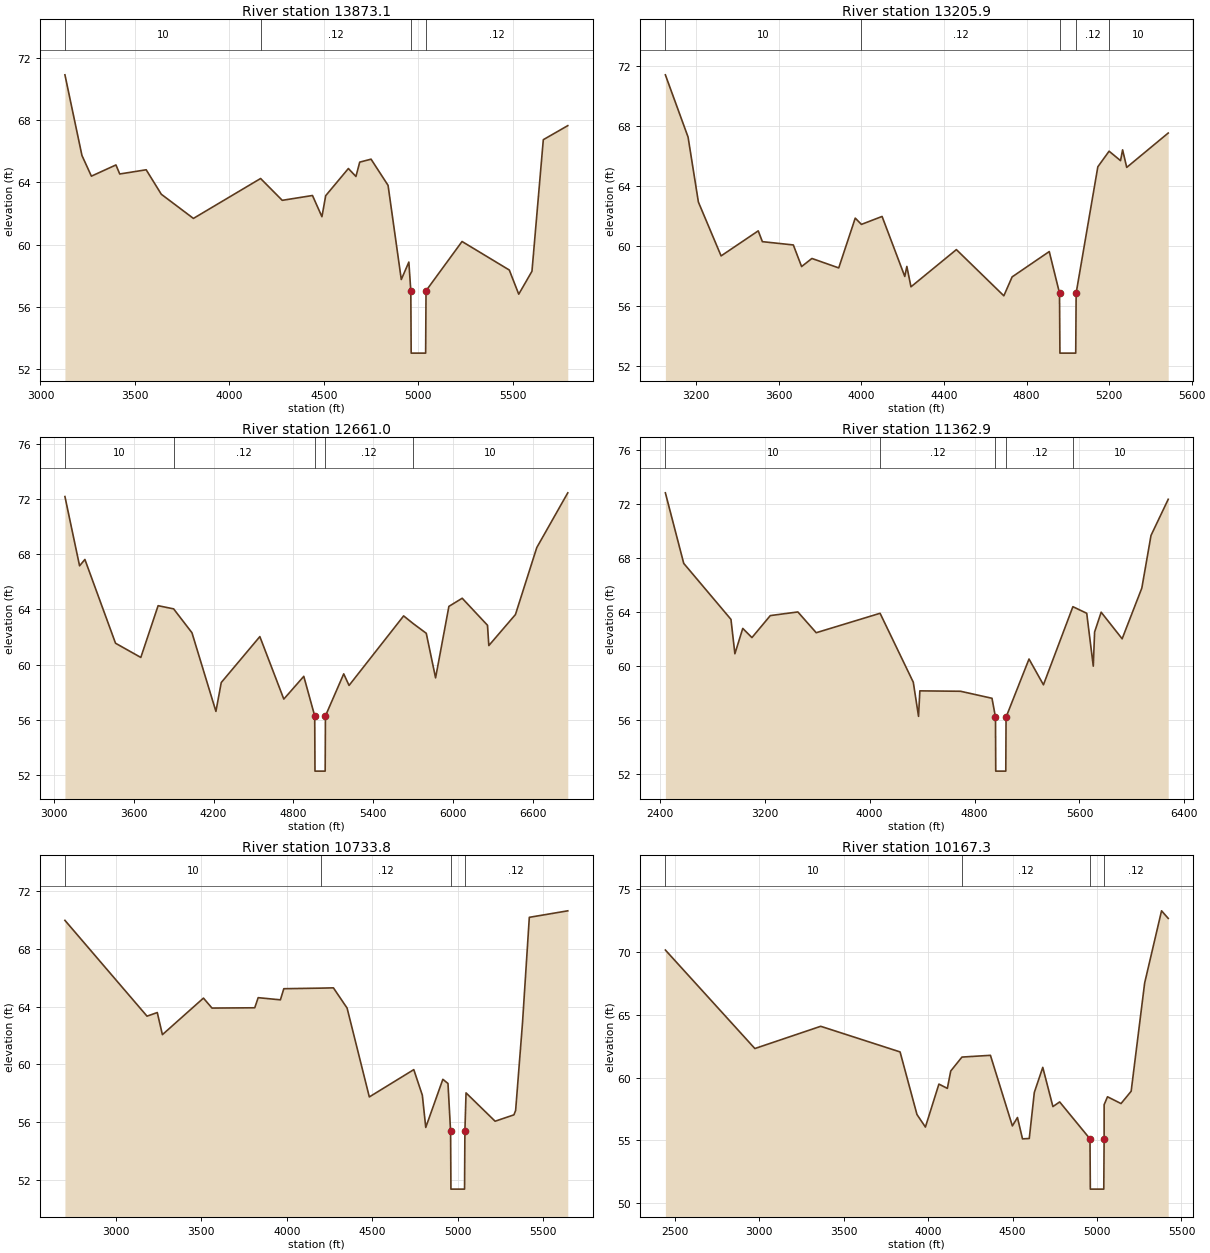
Type RM Length L Ch R = 1 ,13873.1 ,667.2,667.2,667.2
BEGIN DESCRIPTION:
Toisnot Swamp DS 10.0
END DESCRIPTION:
#Sta/Elev= 30
  3129.4   70.89  3219.4   65.72  3269.4   64.39  3399.4   65.11  3419.4   64.53
  3559.4    64.8  3639.4   63.23  3809.4   61.68  4164.9   64.24  4279.4   62.84
  4439.4   63.15  4489.4   61.79  4509.4   63.14  4629.4   64.88  4669.4   64.37
  4689.4   65.29  4749.4   65.48  4839.4    63.8  4909.4   57.76  4949.4   58.88
  4959.7   57.04  4961.7   53.04  5038.3   53.04  5040.3   57.04  5230.9    60.2
  5480.9   58.37  5530.9   56.82  5600.9   58.29  5660.9   66.73  5790.4   67.63
#Mann= 4 , 1 , 0
  3129.4      10       0  4164.9     .12       0  4959.7    .045       0
  5040.3     .12       0
Bank Sta=4959.7,5040.3
XS Rating Curve= 0 ,0
Exp/Cntr=0.3,0.1

Type RM Length L Ch R = 1 ,13205.9 ,544.9,544.9,544.9
BEGIN DESCRIPTION:
Toisnot Swamp DS 9.0
END DESCRIPTION:
#Sta/Elev= 30
    3050   71.39    3160   67.24    3210   62.91    3320   59.32    3500   60.99
    3520   60.27    3670   60.05    3710   58.61    3760   59.15    3890   58.52
    3970   61.84  3999.9   61.42    4100   61.95    4210   57.95    4220   58.62
    4240   57.26    4460   59.74    4690   56.66    4730   57.92    4910   59.61
  4959.7   56.84  4961.7   52.84  5038.3   52.84  5040.3   56.84  5145.4   65.26
  5199.9    66.3  5255.4   65.67  5265.4   66.39  5285.4   65.22  5486.4   67.51
#Mann= 5 , 1 , 0
    3050      10       0  3999.9     .12       0  4959.7    .045       0
  5040.3     .12       0  5199.9      10       0
Bank Sta=4959.7,5040.3
XS Rating Curve= 0 ,0
Exp/Cntr=0.3,0.1

Type RM Length L Ch R = 1 ,12661.0 ,1298.1,1298.1,1298.1
BEGIN DESCRIPTION:
Toisnot Swamp DS 8.0
END DESCRIPTION:
#Sta/Elev= 30
  3083.4   72.18  3193.4   67.16  3233.4   67.62  3463.4   61.55  3653.4   60.52
  3783.4   64.27  3899.9   64.04  4037.6   62.31  4217.6   56.61  4257.6    58.7
  4547.6   62.03  4727.6    57.5  4877.6   59.15  4959.7   56.28  4961.7   52.28
  5038.3   52.28  5040.3   56.28  5177.7   59.33  5217.7   58.49  5627.7   63.53
  5699.9   62.97  5797.7   62.27  5867.7   59.04  5967.7   64.22  6067.7   64.81
  6257.7   62.85  6267.7   61.38  6467.7   63.63  6627.7   68.48  6860.7   72.45
#Mann= 5 , 1 , 0
  3083.4      10       0  3899.9     .12       0  4959.7    .045       0
  5040.3     .12       0  5699.9      10       0
Bank Sta=4959.7,5040.3
XS Rating Curve= 0 ,0
Exp/Cntr=0.3,0.1

Type RM Length L Ch R = 1 ,11362.9 ,629.1,629.1,629.1
BEGIN DESCRIPTION:
Toisnot Swamp DS 7.0
END DESCRIPTION:
#Sta/Elev= 30
  2443.1   72.82  2583.1   67.59  2943.1   63.44  2973.1   60.89  3033.1   62.77
  3103.1   62.09  3243.1   63.72  3453.1   63.99  3593.1   62.45  4079.9   63.89
  4333.1   58.78  4373.1   56.25  4383.1   58.14  4693.1   58.11  4933.1   57.59
  4959.7   56.19  4961.7   52.19  5038.3   52.19  5040.3   56.19  5215.3    60.5
  5325.3   58.59  5549.9   64.38  5655.3   63.89  5705.3   59.97  5715.3    62.5
  5765.3   63.97  5925.3      62  6075.3   65.76  6145.3   69.66  6276.5   72.34
#Mann= 5 , 1 , 0
  2443.1      10       0  4079.9     .12       0  4959.7    .045       0
  5040.3     .12       0  5549.9      10       0
Bank Sta=4959.7,5040.3
XS Rating Curve= 0 ,0
Exp/Cntr=0.3,0.1

Type RM Length L Ch R = 1 ,10733.8 ,566.5,566.5,566.5
BEGIN DESCRIPTION:
Toisnot Swamp DS 6.0
END DESCRIPTION:
#Sta/Elev= 30
    2703   69.97    3183   63.34    3243   63.59    3273   62.06    3513   64.59
    3563    63.9    3813   63.92    3833   64.62    3963   64.47    3983   65.24
  4199.9   65.28    4273    65.3    4353    63.9    4483   57.75    4743   59.64
    4793   57.87    4813   55.64    4913   58.97    4943   58.68  4958.2   55.37
  4960.2   51.37  5039.9   51.37  5041.9   55.37  5048.6   58.03  5218.6   56.07
  5328.6   56.51  5338.6   56.82  5378.6   62.85  5418.6   70.18  5643.5   70.63
#Mann= 4 , 1 , 0
    2703      10       0  4199.9     .12       0  4958.2    .045       0
  5041.9     .12       0
Bank Sta=4958.2,5041.9
XS Rating Curve= 0 ,0
Exp/Cntr=0.3,0.1

Type RM Length L Ch R = 1 ,10167.3 ,653.1,653.1,653.1
BEGIN DESCRIPTION:
Toisnot Swamp DS 5.0
END DESCRIPTION:
#Sta/Elev= 30
  2443.5   70.15  2973.5   62.31  3363.5   64.08  3833.5   62.04  3933.5   57.06
  3983.5   56.06  4063.5   59.48  4113.5   59.14  4133.5   60.52  4199.9   61.63
  4368.6   61.77  4498.6   56.15  4528.6   56.82  4558.6   55.12  4598.6   55.15
  4628.6   58.82  4678.6   60.81  4738.6   57.69  4778.6   58.06  4958.2   55.12
  4960.2   51.12  5039.9   51.12  5041.9   55.12    5042   57.84    5062   58.47
    5142   57.93    5202   58.91    5282   67.53    5382   73.27  5421.5   72.67
#Mann= 4 , 1 , 0
  2443.5      10       0  4199.9     .12       0  4958.2    .045       0
  5041.9     .12       0
Bank Sta=4958.2,5041.9
XS Rating Curve= 0 ,0
Exp/Cntr=0.3,0.1

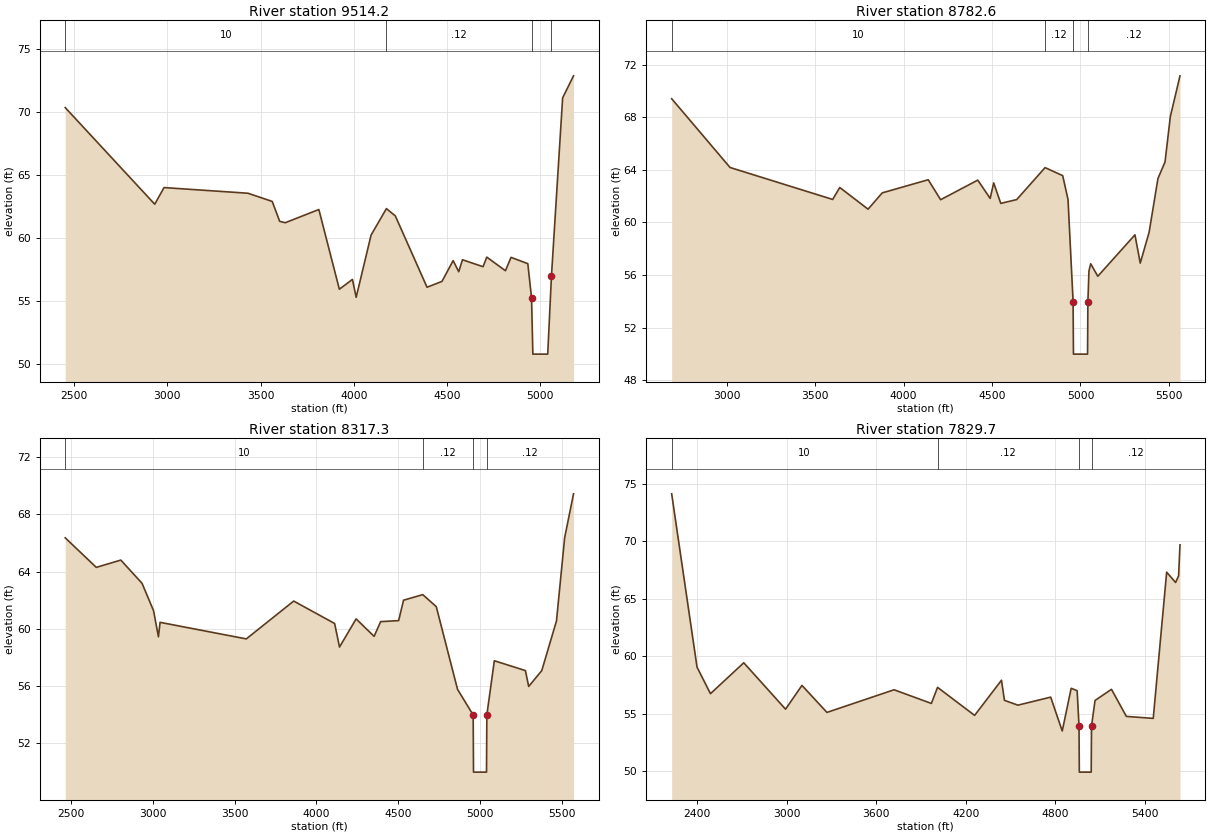
Type RM Length L Ch R = 1 ,9514.2  ,731.6,731.6,731.6
BEGIN DESCRIPTION:
Toisnot Swamp DS 4.0
END DESCRIPTION:
#Sta/Elev= 30
  2452.6   70.39  2932.6   62.72  2982.6   64.04  3432.6   63.59  3562.6   62.94
  3602.6   61.36  3632.6   61.25  3812.6    62.3  3922.6   55.97  3992.7   56.75
  4012.7   55.33  4092.7   60.27  4174.9   62.37  4222.7   61.79  4392.7   56.13
  4472.7   56.59  4532.7   58.24  4562.7   57.36  4582.7   58.31  4693.1   57.76
  4713.1   58.52  4813.1   57.44  4843.1    58.5  4933.1      58  4953.1   55.28
  4960.1   50.82  5039.8   50.82  5059.8   57.01  5119.8   71.16  5178.2   72.91
#Mann= 4 , 1 , 0
  2452.6      10       0  4174.9     .12       0  4953.1    .045       0
  5059.8     .12       0
Bank Sta=4953.1,5059.8
XS Rating Curve= 0 ,0
Exp/Cntr=0.3,0.1

Type RM Length L Ch R = 1 ,8782.6  ,465.3,465.3,465.3
BEGIN DESCRIPTION:
Toisnot Swamp DS 3.0
END DESCRIPTION:
#Sta/Elev= 30
  2689.5   69.41  3019.5   64.18  3599.5   61.75  3639.5   62.66  3799.5   61.01
  3879.5   62.25  4139.5   63.25  4209.5   61.73  4419.5   63.22  4489.5   61.83
  4509.5   63.01  4549.5   61.45  4639.5   61.74  4799.9   64.17  4899.5   63.56
  4929.5   61.75  4958.2   53.99  4960.2   49.99  5039.9   49.99  5041.9   53.99
  5047.8   56.31  5057.8   56.86  5097.8   55.91  5307.8   59.06  5337.8   56.91
  5387.8   59.25  5437.8   63.34  5477.8    64.6  5507.8   68.05  5562.4   71.15
#Mann= 4 , 1 , 0
  2689.5      10       0  4799.9     .12       0  4958.2    .045       0
  5041.9     .12       0
Bank Sta=4958.2,5041.9
XS Rating Curve= 0 ,0
Exp/Cntr=0.3,0.1

Type RM Length L Ch R = 1 ,8317.3  ,487.6,487.6,487.6
BEGIN DESCRIPTION:
Toisnot Swamp DS 2.0
END DESCRIPTION:
#Sta/Elev= 30
  2463.8   66.36  2653.8   64.29  2803.8    64.8  2933.8   63.17  3003.8   61.26
  3033.8   59.43  3043.8   60.44    3571   59.28    3861   61.93    4111   60.36
    4141   58.71  4242.5   60.68  4352.5   59.46  4392.5   60.49  4502.5   60.56
  4532.5   61.99  4649.9   62.38  4732.5   61.54  4862.5   55.75  4958.2   53.95
  4960.2   49.95  5039.8   49.95  5041.8   53.95  5087.6   57.75  5277.6   57.06
  5297.6   55.95  5377.6   57.06  5467.6   60.54  5517.6   66.37  5571.8   69.44
#Mann= 4 , 1 , 0
  2463.8      10       0  4649.9     .12       0  4958.2    .045       0
  5041.8     .12       0
Bank Sta=4958.2,5041.8
XS Rating Curve= 0 ,0
Exp/Cntr=0.3,0.1

Type RM Length L Ch R = 1 ,7829.7  ,461.4,461.4,461.4
BEGIN DESCRIPTION:
Toisnot Swamp DS 1.0
END DESCRIPTION:
#Sta/Elev= 30
  2227.6   74.15  2397.6   59.06  2487.6   56.75  2710.9   59.44  2990.9    55.4
  3100.9   57.47  3268.4   55.12  3718.4   57.09  3968.4    55.9  4009.9    57.3
  4258.3   54.86  4438.3   57.92  4458.3   56.17  4548.3   55.75  4768.3   56.45
  4845.6    53.5  4905.6   57.22  4945.6   57.01  4958.1   53.92  4960.1   49.92
  5039.8   49.92  5041.8   53.92  5065.6   56.16  5175.6   57.13  5275.6   54.77
  5455.6    54.6  5545.6   67.33  5605.6   66.43  5625.6   67.01    5635   69.71
#Mann= 4 , 1 , 0
  2227.6      10       0  4009.9     .12       0  4958.1    .045       0
  5041.8     .12       0
Bank Sta=4958.1,5041.8
XS Rating Curve= 0 ,0
Exp/Cntr=0.3,0.1

Chan Stop Cuts=-1
Use User Specified Reach Order=0