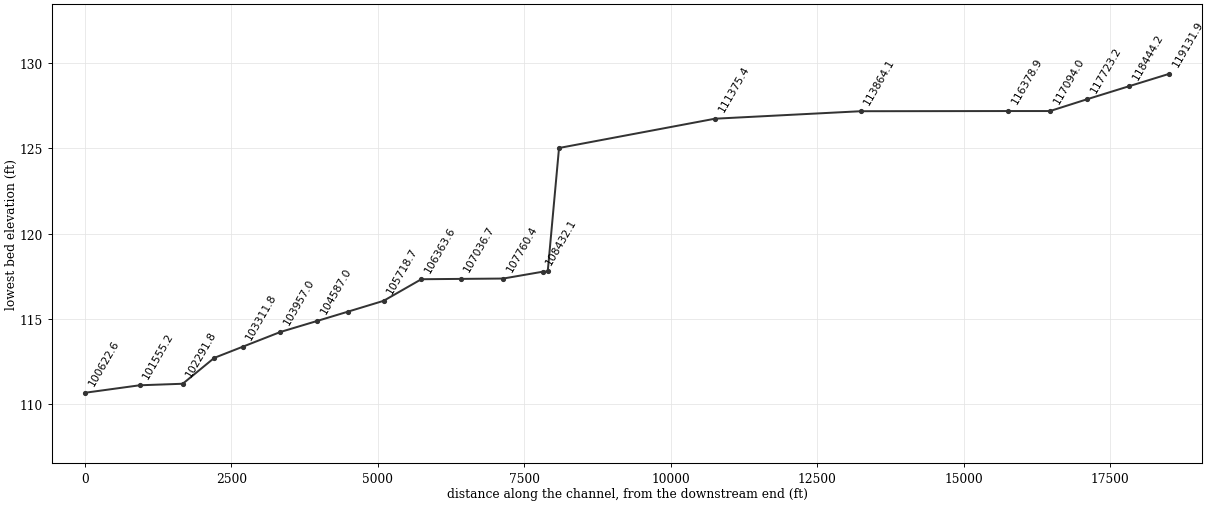
--- Toisnot_Swamp_US_021220.prj (project) ---

Proj Title=Toisnot Swamp US
Current Plan=p02
Default Exp/Contr=0.3,0.1
English Units
Geom File=g01
Flow File=f02
Flow File=f01
Plan File=p01
Plan File=p02
Y Axis Title=Elevation
X Axis Title(PF)=Main Channel Distance
X Axis Title(XS)=Station
BEGIN DESCRIPTION:
 Cross Sections 96519.5 and 96326 were removed from the LDS model and downstream boundary condition revised to ensure tie in with new DTL study
NEUSE RIVER BASIN
Little Contentnea Creek Sub-basin
TOISNOT SWAMP US
(Flood Hazard, Floodway) Model
Prepared by: Andrew J. Bonner   Date: 11/26/2002
Watershed Concepts
3333 Regency Pkwy
Cary, North Carolina 27511
END DESCRIPTION:
DSS Export Rating Curves= 0
DSS Export Rating Curve Sorted= 0
DSS Export Volume Flow Curves= 0
DXF OffsetX= 0
DXF OffsetY= 0
DXF ScaleX= 1
DXF ScaleY= 10

--- Toisnot_Swamp_US_021220.p02 (plan) ---

Plan Title=Multi Profile
Program Version=4.00
Short Identifier=Plan01
Geom File=g01
Flow File=f02
Subcritical Flow
K Sum by GR= 0
Std Step Tol= 0.01
Critical Tol= 0.01
Num of Std Step Trials= 20
Max Error Tol= 0.3
Flow Tol Ratio= 0.001
Split Flow NTrial= 30
Split Flow Tol= 0.02
Split Flow Ratio= 0.02
Log Output Level= 0
Friction Slope Method= 1
Unsteady Friction Slope Method= 2
Unsteady Bridges Friction Slope Method= 1
Parabolic Critical Depth
Global Vel Dist= 0 , 0 , 0
Global Log Level= 0
CheckData=True
Encroach Param=-1 ,10,10, 2
Computation Interval=1HOUR
Output Interval=1HOUR
Run HTab= 0
Run UNet= 0
Run PostProcess= 0
Run WQNet= 0
UNET Theta= 1
UNET Theta Warmup= 1
UNET ZTol= 0.02
UNET ZSATol= 0.1
UNET MxIter= 20
UNET MaxInSteps= 20
UNET DtIC= 0
UNET DtMin= 0
UNET MaxCRTS= 20
UNET WFStab= 2
UNET SFStab= 1
UNET WFX= 1
UNET SFX= 1
UNET DSS MLevel= 4
UNET DZMax Abort= 100
UNET Convert EG Bridges=-1
UNET Use Existing IB Tables=-1
UNET Froude Reduction=False
UNET Froude Limit= 1
UNET Froude Power= 10
UNET Time Slicing=0,0, 5
Instantaneous Interval=1HOUR
Write IC File= 0
Echo Input=False
Echo Output=False
Write Detailed= 0
Detailed Automatic Start=False, 10
WQ ULTIMATE=-1
WQ Max Comp Step=1HOUR
WQ Output Interval=15MIN
WQ Output Selected Increments= 0
WQ Output face flow=0
WQ Output face velocity=0
WQ Output face area=0
WQ Output face dispersion=0
WQ Output cell volume=0
WQ Output cell surface area=0
WQ Output cell continuity=0
WQ Output face conc=0
WQ Output face dconc_dx=0
WQ Output face courant=0
WQ Output face peclet=0
WQ Output face adv mass=0
WQ Output face disp mass=0
WQ Output cell mass=0
WQ Output cell source sink temp=0
WQ Output cell source sink nsm=0
WQ Output MaxMinRange=-1
WQ Daily Max Min Mean=-1
WQ Daily Range=0
WQ Daily Time=0
WQ Create Restart=0
WQ Fixed Restart=0
WQ System Summary=False
Sorting and Armoring Iterations= 10
XS Update Threshold= 0.02
Hydraulics Update Threshold= 0.02
Energy Slope Method= 1
Volume Change Method= 0
XS Weighting Method= 0
Number of US Weighted Cross Sections= 1
Number of DS Weighted Cross Sections= 1
Upstream XS Weight=0.25
Main XS Weight=0.5
Downstream XS Weight=0.25
Number of DS XS's Weighted with US Boundary= 1
Upstream Boundary Weight= 1
Weight of XSs Associated with US Boundary= 0
Number of US XS's Weighted with DS Boundary= 1
Downstream Boundary Weight= 0.5
Weight of XSs Associated with DS Boundary= 0.5
Sediment Output Level= 4
Mass or Volume Output= 0
Output Increment Type= 1
Profile and TS Output Increment= 10
XS Output Flag= 0
XS Output Increment= 10
Disregard all LS=0
Disregard all Conn=0
Disregard all Breaches=0
Disregard all Pumps=0

--- Toisnot_Swamp_US_021220.p01 (plan) ---

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Plan Title=100 Year Single
Geom File=g01
Flow File=f01
Encroach River=Toisnot Swamp US
Encroach Reach=Reach - 1
Encroach Node=119131.9
       4      .7
Encroach Node=118444.2
       4      .7
Encroach Node=117723.2
       4      .7
Encroach Node=117094.0
       4      .7
Encroach Node=116378.9
       4      .7
Encroach Node=113864.1
       4      .7
Encroach Node=111375.4
       1    4225    5540
Encroach Node=108713.8
       1    4670    5083
Encroach Node=108521.1
       1    4905    5083
Encroach Node=108432.1
       1    4905    5083
Encroach Node=107760.4
       4      .7
Encroach Node=107036.7
       4      .7
Encroach Node=106363.6
       4      .7
Encroach Node=105718.7
       4      .7
Encroach Node=105106.0
       4      .7
Encroach Node=104587.0
       4      .7
Encroach Node=103957.0
       4      .7
Encroach Node=103311.8
       4      .7
Encroach Node=102829.9
       4      .7
Encroach Node=102291.8
       4      .7
Encroach Node=101555.2
       4      .7
Encroach Node=100622.6
       1 4973.56 5522.95

--- Toisnot_Swamp_US_021220.f02 (steady flow) ---

Flow Title=Multi-Profile
Program Version=4.00
Number of Profiles= 7
Profile Names=10-yr,25-yr,50-yr,500-yr,100-yr 10%,100-yr 20%,100-yr 35%
River Rch & RM=Toisnot Swamp US,Reach - 1       ,119131.9
    3398    4563    5572    9665    6813    8732   10670
River Rch & RM=Toisnot Swamp US,Reach - 1       ,116378.9
    3438    4615    5635    9769    6885    8824   10782
River Rch & RM=Toisnot Swamp US,Reach - 1       ,108713.8
    3567    4784    5838   10104    7116    9121   11144
River Rch & RM=Toisnot Swamp US,Reach - 1       ,105718.7
    3633    4870    5940   10273    7233    9271   11327
River Rch & RM=Toisnot Swamp US,Reach - 1       ,100622.6
    3655    4898    5975   10331    7273    9321   11389
Boundary for River Rch & Prof#=Toisnot Swamp US,Reach - 1       , 1
Up Type= 0
Dn Type= 1
Dn Known WS=118.92
Boundary for River Rch & Prof#=Toisnot Swamp US,Reach - 1       , 2
Up Type= 0
Dn Type= 1
Dn Known WS=119.52
Boundary for River Rch & Prof#=Toisnot Swamp US,Reach - 1       , 3
Up Type= 0
Dn Type= 1
Dn Known WS=120.01
Boundary for River Rch & Prof#=Toisnot Swamp US,Reach - 1       , 4
Up Type= 0
Dn Type= 1
Dn Known WS=121.76
Boundary for River Rch & Prof#=Toisnot Swamp US,Reach - 1       , 5
Up Type= 0
Dn Type= 1
Dn Known WS=120.57
Boundary for River Rch & Prof#=Toisnot Swamp US,Reach - 1       , 6
Up Type= 0
Dn Type= 1
Dn Known WS=121.37
Boundary for River Rch & Prof#=Toisnot Swamp US,Reach - 1       , 7
Up Type= 0
Dn Type= 1
Dn Known WS=122.1
DSS Import GetInterval= 0
DSS Import GetPeak= 0
DSS Import FillOption= 0

--- Toisnot_Swamp_US_021220.f01 (steady flow) ---

Flow Title= 100 Year Single
Program Version=4.00
Number of Profiles= 2
Profile Names=100-Year,AFW
River Rch & RM=Toisnot Swamp US,Reach - 1       ,119131.9
    6658    6658
River Rch & RM=Toisnot Swamp US,Reach - 1       ,116378.9
    6732    6732
River Rch & RM=Toisnot Swamp US,Reach - 1       ,108713.8
    6971    6971
River Rch & RM=Toisnot Swamp US,Reach - 1       ,105718.7
    7091    7091
River Rch & RM=Toisnot Swamp US,Reach - 1       ,100622.6
    7132    7132
Boundary for River Rch & Prof#=Toisnot Swamp US,Reach - 1       , 1
Up Type= 0
Dn Type= 1
Dn Known WS=120.52
Boundary for River Rch & Prof#=Toisnot Swamp US,Reach - 1       , 2
Up Type= 0
Dn Type= 1
Dn Known WS=121.3
DSS Import GetInterval= 0
DSS Import GetPeak= 0
DSS Import FillOption= 0

--- Toisnot_Swamp_US_021220.g01 (geometry) ---

Geom Title=Geom 01 by CodeH2 for Windows
Program Version=4.00

River Reach=Toisnot Swamp US,Reach - 1
Reach XY= 30
        0.053593       0.4525716        0.153517       0.4263259
       0.1698878       0.4424368        0.205748       0.4517916
       0.2293955       0.4447757       0.2600584       0.4177506
          0.2572       0.4044976        0.269673       0.3821497
       0.2587594        0.367078       0.2940999       0.3343361
       0.4272883        0.329438       0.4693176       0.3029072
       0.4861292       0.3008059       0.5129229       0.3128894
       0.5638833       0.3023819       0.6539829       0.3126265
       0.6734216       0.2979163       0.6676425       0.2829437
       0.6860305       0.2824184       0.6962752       0.2732244
       0.7093207       0.2365583       0.7245308       0.2239603
       0.7409695       0.2313346        0.741123       0.2187371
       0.7711527       0.2161021       0.7752978       0.1981394
       0.7923395       0.1815581       0.8605896       0.1423743
       0.8932973       0.1142094       0.9230589       0.0587868

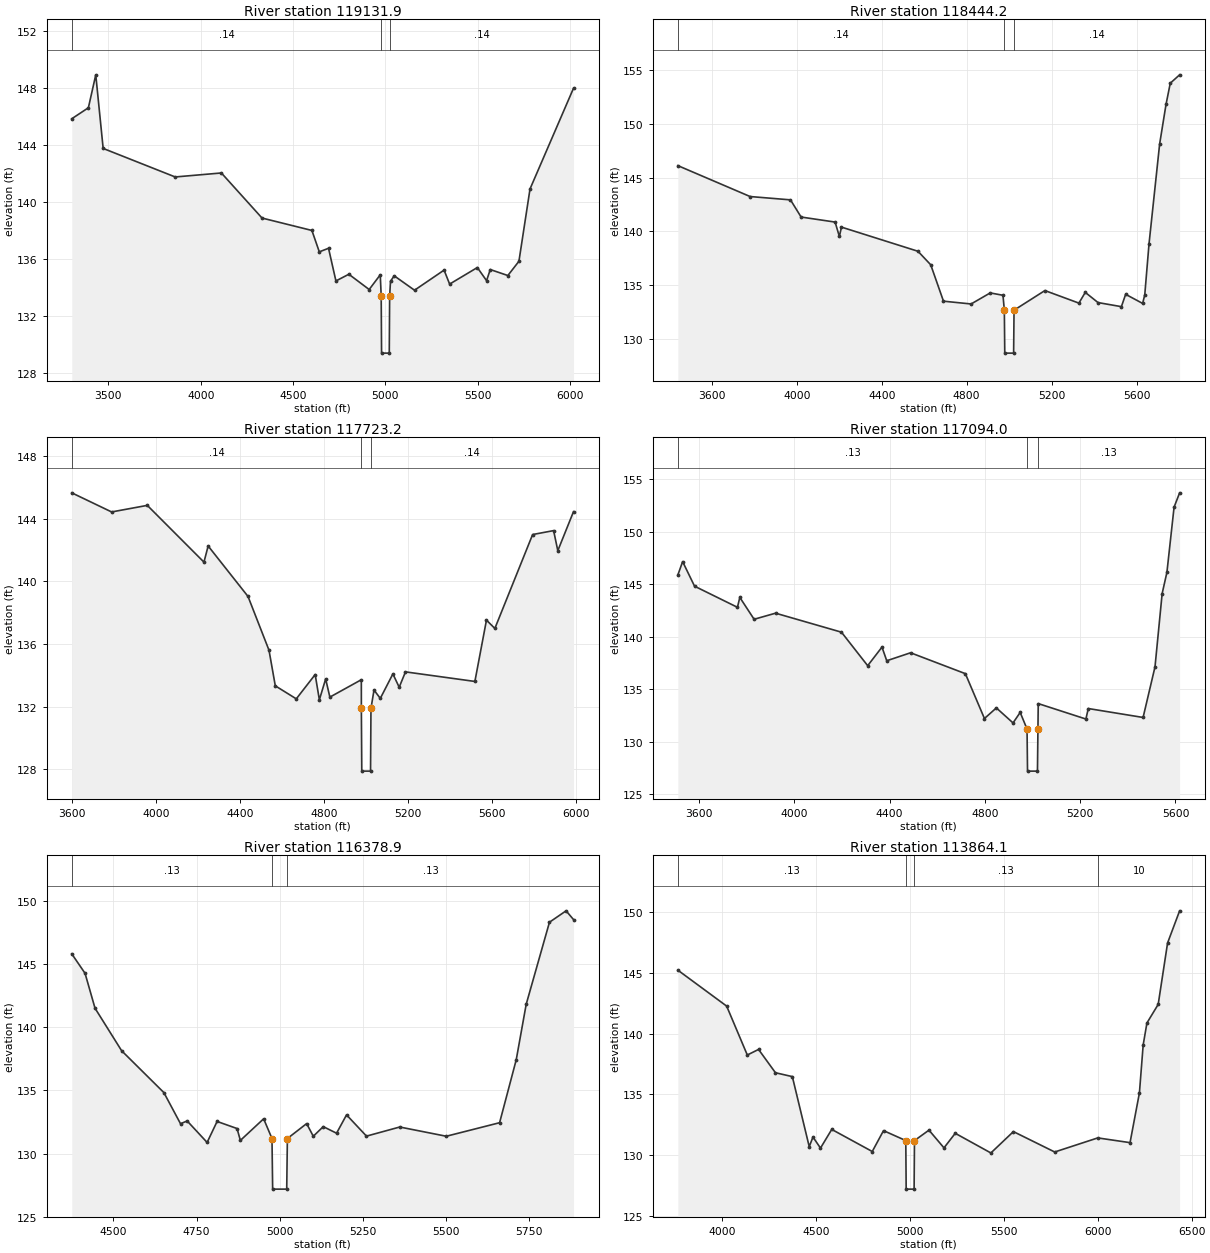
Type RM Length L Ch R = 1 ,119131.9,687.7,687.7,687.7
BEGIN DESCRIPTION:
Toisnot Swamp US 70.0
END DESCRIPTION:
#Sta/Elev= 30
    3302  145.82    3392  146.59    3432   148.9    3472  143.74    3862  141.74
    4112  142.02    4332  138.86    4602  137.99    4642  136.49    4692  136.74
    4732  134.45    4802  134.92    4912  133.85    4972  134.88  4977.1  133.39
  4979.1  129.39  5020.8  129.39  5022.8  133.39  5027.5  134.43  5047.5  134.81
  5157.5   133.8  5317.5  135.21  5347.5  134.23  5497.5  135.39  5547.5  134.47
  5567.5  135.25  5662.7  134.83  5722.7  135.83  5782.7   140.9  6018.1  147.96
#Mann= 3 , 1 , 0
    3302     .14       0  4977.1    .048       0  5022.8     .14       0
Bank Sta=4977.1,5022.8
XS Rating Curve= 0 ,0
Exp/Cntr=0.3,0.1

Type RM Length L Ch R = 1 ,118444.2,721,721,721
BEGIN DESCRIPTION:
Toisnot Swamp US 69.0
END DESCRIPTION:
#Sta/Elev= 30
  3440.8  146.13  3780.8  143.25  3970.8  142.94  4020.8  141.34  4180.8  140.87
  4200.8  139.53  4210.8   140.4  4570.8  138.15  4630.8  136.89  4690.8   133.5
  4820.8  133.24  4910.8  134.27  4970.8  134.05  4977.2  132.66  4979.2  128.66
  5020.9  128.66  5022.9  132.66  5168.1  134.49  5328.1  133.32  5358.1  134.32
  5418.1  133.37  5528.1  132.99  5548.1  134.14  5628.1  133.29  5638.1   134.1
  5658.1  138.84  5708.1  148.15  5738.1  151.83  5758.1  153.81  5802.1  154.59
#Mann= 3 , 1 , 0
  3440.8     .14       0  4977.2    .048       0  5022.9     .14       0
Bank Sta=4977.2,5022.9
XS Rating Curve= 0 ,0
Exp/Cntr=0.3,0.1

Type RM Length L Ch R = 1 ,117723.2,629.2,629.2,629.2
BEGIN DESCRIPTION:
Toisnot Swamp US 68.0
END DESCRIPTION:
#Sta/Elev= 30
    3597  145.64    3787  144.42    3957  144.84    4227  141.22    4247  142.25
    4437  139.03    4537   135.6    4567  133.33    4667   132.5    4757  134.05
    4777  132.44    4807  133.77    4827  132.61    4977  133.72  4977.1  131.89
  4979.1  127.89  5020.9  127.89  5022.9  131.89  5037.4  133.06  5067.4  132.53
  5127.4  134.09  5157.4  133.24  5187.4  134.22  5518.1  133.61  5573.3  137.52
  5613.3  136.99  5793.3  142.98  5893.3  143.23  5913.3  141.95  5988.1  144.44
#Mann= 3 , 1 , 0
    3597     .14       0  4977.1    .048       0  5022.9     .14       0
Bank Sta=4977.1,5022.9
XS Rating Curve= 0 ,0
Exp/Cntr=0.3,0.1

Type RM Length L Ch R = 1 ,117094.0,715.1,715.1,715.1
BEGIN DESCRIPTION:
Toisnot Swamp US 67.0
END DESCRIPTION:
#Sta/Elev= 30
  3511.7  145.88  3531.7  147.15  3581.7  144.81  3761.7   142.8  3771.7  143.74
  3831.7  141.66  3921.7  142.24  4198.3  140.43  4308.3  137.24  4368.3  139.01
  4388.3  137.71  4488.3  138.47  4718.3  136.48  4798.3  132.21  4848.3  133.22
  4918.3  131.79  4948.3  132.79  4977.1   131.2  4979.1   127.2  5020.8   127.2
  5022.8   131.2  5024.1  133.63  5224.1  132.16  5234.1  133.16  5464.1  132.31
  5514.1  137.13  5544.1  144.11  5564.1  146.13  5594.1  152.33  5617.4   153.7
#Mann= 3 , 1 , 0
  3511.7     .13       0  4977.1    .048       0  5022.8     .13       0
Bank Sta=4977.1,5022.8
XS Rating Curve= 0 ,0
Exp/Cntr=0.3,0.1

Type RM Length L Ch R = 1 ,116378.9,2514.8,2514.8,2514.8
BEGIN DESCRIPTION:
Toisnot Swamp US 66.0
END DESCRIPTION:
#Sta/Elev= 30
  4374.6   145.8  4414.6  144.26  4444.6   141.5  4524.6  138.14  4651.7  134.83
  4701.7  132.37  4721.7  132.59  4781.7  130.89  4811.7  132.55  4871.7  131.99
  4881.7  131.05  4951.7  132.76  4976.8   131.2  4978.8   127.2  5021.1   127.2
  5023.1   131.2    5081  132.38    5101  131.38    5131  132.14    5171  131.62
    5201  133.07    5261  131.39    5361  132.11    5501  131.38  5661.3  132.45
  5711.3  137.42  5741.3  141.81  5811.3   148.3  5861.3   149.2  5883.6  148.51
#Mann= 3 , 1 , 0
  4374.6     .13       0  4976.8    .048       0  5023.1     .13       0
Bank Sta=4976.8,5023.1
XS Rating Curve= 0 ,0
Exp/Cntr=0.3,0.1

Type RM Length L Ch R = 1 ,113864.1,2488.7,2488.7,2488.7
BEGIN DESCRIPTION:
Toisnot Swamp US 65.0
END DESCRIPTION:
#Sta/Elev= 30
  3762.2  145.23  4022.2  142.27  4132.2  138.24  4192.2   138.7  4282.2  136.78
  4372.2  136.46  4462.2  130.69  4482.2  131.48  4522.2  130.57  4582.2  132.11
  4798.1  130.29  4858.1  132.01  4976.8  131.19  4978.8  127.19  5021.1  127.19
  5023.1  131.19  5100.3  132.05  5180.3  130.59  5240.3  131.79  5430.3  130.17
  5550.3  131.93  5770.3  130.25  5999.9  131.41  6171.8  131.02  6221.8  135.12
  6241.8  139.07  6261.8  140.88  6321.8  142.41  6371.8  147.47    6436  150.12
#Mann= 4 , 1 , 0
  3762.2     .13       0  4976.8    .048       0  5023.1     .13       0
  5999.9      10       0
Bank Sta=4976.8,5023.1
XS Rating Curve= 0 ,0
Exp/Cntr=0.3,0.1

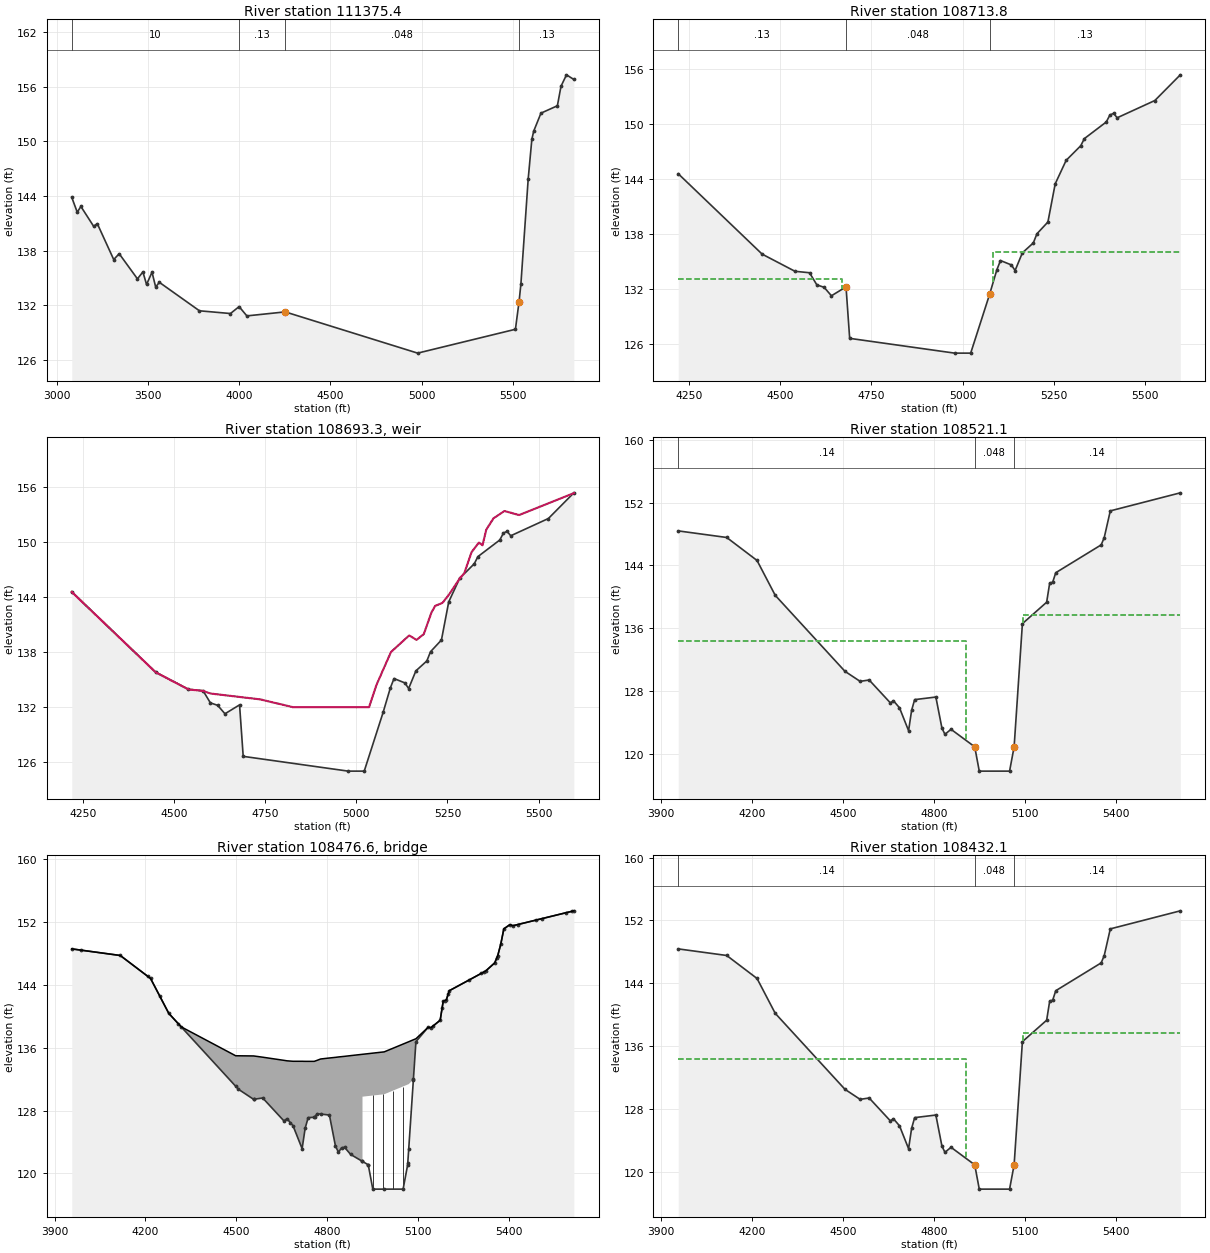
Type RM Length L Ch R = 1 ,111375.4,2661.6,2661.6,2661.6
BEGIN DESCRIPTION:
Silver Lake
END DESCRIPTION:
#Sta/Elev= 30
  3082.5  143.86  3112.5  142.23  3132.5  142.86  3202.5  140.68  3222.5  140.97
  3312.5  137.03  3342.5  137.67  3442.5  134.91  3472.5  135.67  3492.5  134.29
  3522.5  135.64  3542.5  134.01  3562.5  134.53  3782.5   131.4  3952.5   131.1
  3999.9  131.86  4042.5  130.84  4252.5  131.28  4978.8  126.75  5514.9  129.37
  5534.9  132.41  5544.9  134.33  5584.9  145.88  5604.9  150.22  5614.9  151.12
  5654.9  153.11  5744.9  153.92  5764.9  156.07  5794.9  157.32  5835.2  156.81
#Mann= 4 , 1 , 0
  3082.5      10       0  3999.9     .13       0  4252.5    .048       0
  5534.9     .13       0
Bank Sta=4252.5,5534.9
XS Rating Curve= 0 ,0
Exp/Cntr=0.5,0.3

Type RM Length L Ch R = 1 ,108713.8,192.7,192.7,192.7
BEGIN DESCRIPTION:
Upstream Section of Bridge/Culvert/Weir
END DESCRIPTION:
#Sta/Elev= 30
  4220.2  144.58  4450.2  135.82  4540.2  133.95  4580.2  133.79  4600.2  132.47
  4620.2   132.2  4640.2  131.28  4680.2  132.25  4690.2  126.64    4978  125.03
    5022  125.03  5073.7  131.42  5093.7  134.11  5103.7  135.12  5133.7  134.64
  5143.7  134.03  5163.7  135.96  5193.7  137.04  5203.7  138.04  5233.7  139.32
  5253.7  143.48  5283.7  146.04  5323.7  147.63  5333.7  148.41  5393.7  150.22
  5403.7  150.98  5413.7  151.16  5423.7  150.68  5526.9  152.56  5596.7  155.36
#Mann= 3 , 1 , 0
  4220.2     .13       0  4680.2    .048       0  5073.7     .13       0
#XS Ineff= 2 , 0
       0  4670.2  133.14  5083.7       0  136.06
Permanent Ineff=
       F       F
Bank Sta=4680.2,5073.7
XS Rating Curve= 0 ,0
Exp/Cntr=0.5,0.3

Type RM Length L Ch R = 5 ,108693.3,,,
BEGIN DESCRIPTION:
Silver Lake Dam-TOR
Structure ID: Silver Lake Dam
Approximate Survey Structure
END DESCRIPTION:
IW Pilot Flow=0
#Inline Weir SE= 27
  4220.2  144.55  4450.2   135.8  4540.2  133.93  4580.2  133.77  4600.2  133.49
  4736.6  132.85  4826.6     132  5035.3     132  5055.3   134.4  5095.3  138.01
  5145.3  139.82  5165.3  139.33  5185.3  139.96  5206.4  142.33  5216.4  143.03
  5236.4  143.36  5253.7  144.23  5283.7  146.02  5296.4  146.61  5316.4  148.91
  5336.4  149.94  5346.4  149.64  5356.4  151.33  5376.4  152.58  5406.4  153.38
  5446.4  152.94  5596.7  155.33
IW Dist,WD,Coef,Skew,MaxSub,Min_El,Is_Ogee,SpillHt,DesHd
10,21,3,0,0.95,, 0 ,,,2,2,

Type RM Length L Ch R = 1 ,108521.1,89,89,89
BEGIN DESCRIPTION:
Upstream Section of Bridge/Culvert/Weir
END DESCRIPTION:
#Sta/Elev= 30
  3956.8  148.39  4116.8  147.55  4216.8  144.62  4276.8  140.18  4506.8   130.5
  4556.8  129.22  4586.8  129.39  4656.8  126.47  4666.8  126.75  4686.8  125.85
  4716.8  122.93  4726.8  125.53  4736.8  126.89  4806.8  127.22  4826.8  123.26
  4836.8  122.47  4856.8  123.11    4935  120.88    4950  117.78    5050  117.78
    5065  120.88  5092.3  136.57  5172.3   139.3  5182.3  141.73  5192.3  141.86
  5202.3  143.06  5352.3  146.61  5362.3  147.54  5382.3  150.94  5613.3  153.24
#Mann= 3 , 1 , 0
  3956.8     .14       0    4935    .048       0    5065     .14       0
#XS Ineff= 2 , 0
       0    4905   134.3    5095       0   137.7
Permanent Ineff=
       F       F
Bank Sta=4935,5065
XS Rating Curve= 0 ,0
Exp/Cntr=0.5,0.3

Type RM Length L Ch R = 3 ,108476.6,,,
BEGIN DESCRIPTION:
NC 58-TOR
Structure ID: TS - NC 58
Approximate Survey Structure
END DESCRIPTION:
Bridge Culvert--1,0,-1,-1, 0
Deck Dist Width WeirC Skew NumUp NumDn MinLoCord MaxHiCord MaxSubmerge Is_Ogee
10,69,2.6,0, 44, 44, , , 0.95, 0, 1,1,,
  3956.8  4116.8  4216.8  4276.8  4317.7  4497.7  4506.8  4556.8  4586.8  4656.8
  4666.8  4686.8  4716.8  4726.8  4736.8  4756.8  4766.8  4777.7  4806.8  4826.8
  4836.8  4846.8  4856.8  4876.8 4915.91    4916  4987.7  5068.5 5083.89  5092.3
  5132.3  5142.3  5172.3  5182.3  5192.3  5202.3  5322.3  5352.3  5362.3  5372.3
  5382.3  5402.3  5412.1  5613.3
  148.61  147.77  144.84   140.4  138.68  134.99  134.99  134.97  134.81  134.41
  134.35  134.29  134.29  134.28  134.28  134.28  134.42  134.58  134.71  134.79
  134.84  134.88  134.92  135.01  135.18  135.18  135.49  136.78  137.03  137.16
  138.61  138.58  139.52  141.95  142.08  143.28  145.79  146.83  147.76  149.23
  151.16   151.7  151.56  153.46
  148.61  147.77  144.84   140.4  138.68   131.1  130.72  129.44  129.61  126.69
  126.97  126.07  123.15  125.75  127.11  127.15  127.61  127.56  127.44  123.48
  122.69  123.26  123.33  122.42  121.53  129.78  130.09  131.38  131.96  136.79
  138.61  138.58  139.52  141.95  142.08  143.28  145.79  146.83  147.76  149.23
  151.16   151.7  151.56  153.46
  3956.8  4116.8  4216.8  4276.8  4317.7  4497.7  4506.8  4556.8  4586.8  4656.8
  4666.8  4686.8  4716.8  4726.8  4736.8  4756.8  4766.8  4777.7  4806.8  4826.8
  4836.8  4846.8  4856.8  4876.8 4915.91    4916  4987.7  5068.5 5083.89  5092.3
  5132.3  5142.3  5172.3  5182.3  5192.3  5202.3  5322.3  5352.3  5362.3  5372.3
  5382.3  5402.3  5412.1  5613.3
  148.51  147.68  144.75  140.31  138.59  134.99  134.99  134.97  134.81  134.41
  134.35  134.29  134.29  134.28  134.28  134.28  134.42  134.58  134.71  134.79
  134.84  134.88  134.92  135.01  135.18  135.18  135.49  136.78  137.03  137.16
  138.52  138.49  139.43  141.86  141.99  143.19   145.7  146.74  147.67  149.14
  151.07  151.61  151.47  153.36
  148.41  147.57  144.64   140.2  138.48   130.9  130.52  129.24  129.41  126.49
  126.77  125.87  122.95  125.55  126.91  126.95  127.41  127.36  127.24  123.28
  122.49  123.06  123.13  122.22  121.33  129.58  129.89  131.18  131.76  136.59
  138.41  138.38  139.32  141.75  141.88  143.08  145.59  146.63  147.56  149.03
  150.96   151.5  151.36  153.26
Pier Skew, UpSta & Num, DnSta & Num=  ,4950.9, 2 ,4950.9, 2 , 0 , 0 , 0 ,,
       1       1
     117  130.94
       1       1
   116.8  130.74
Pier Skew, UpSta & Num, DnSta & Num=  ,4983.6, 2 ,4983.6, 2 , 0 , 0 , 0 ,,
       1       1
     117  131.07
       1       1
   116.8  130.87
Pier Skew, UpSta & Num, DnSta & Num=  ,5016.4, 2 ,5016.4, 2 , 0 , 0 , 0 ,,
       1       1
     117  131.55
       1       1
   116.8  131.35
Pier Skew, UpSta & Num, DnSta & Num=  ,5049.1, 2 ,5049.1, 2 , 0 , 0 , 0 ,,
       1       1
     117  132.07
       1       1
   116.8  131.87
Abutment Skew #Up #Dn= , 2 , 2
  4915.8  4934.5
  129.78  121.11
  4915.8  4934.5
  129.58  120.91
Abutment Skew #Up #Dn= , 2 , 2
  5065.5 5084.09
  121.39  131.96
  5065.5 5084.09
  121.19  131.76
BR Coef= 1 , 1 , 0 ,1.25, 0 ,,,0.8,0,2,0,
WSPro=,,,, 1 ,,,, 0 ,,,, 0 ,,,,-1 ,-1 ,-1 , 0 , 0 , 0 , 0 , 0
BR U #Sta/Elev= 71
  3956.8  148.61  3987.7  148.45  4116.8  147.77  4207.7  145.11  4216.8  144.84
  4247.7  142.55  4276.8   140.4  4307.7   139.1  4317.7  138.68  4497.7   131.1
  4506.8  130.72  4556.8  129.44  4557.7  129.45  4586.8  129.61  4656.8  126.69
  4666.8  126.97  4677.7  126.48  4686.8  126.07  4716.8  123.15  4726.8  125.75
  4736.8  127.11  4756.8  127.15  4757.7  127.19  4766.8  127.61  4777.7  127.56
  4806.8  127.44  4826.8  123.48  4836.8  122.69  4846.8  123.26  4856.8  123.33
  4876.8  122.42 4915.91  121.53    4916  121.53  4934.5  121.11    4935   121.1
    4950     118  4987.7     118    5050     118    5065   121.1  5065.5  121.39
  5068.5  123.11 5083.89  131.96    5084  132.02  5092.3  136.79  5132.3  138.61
  5142.3  138.58  5148.5  138.77  5172.3  139.52  5178.5  141.03  5182.3  141.95
  5188.5  142.03  5192.3  142.08  5198.5  142.82  5202.3  143.28  5268.5  144.66
  5308.5   145.5  5318.5  145.71  5322.3  145.79  5352.3  146.83  5358.5  147.41
  5362.3  147.76  5372.3  149.23  5382.3  151.16  5402.3   151.7  5412.1  151.56
  5428.5  151.71  5488.5  152.28  5508.5  152.47  5588.5  153.23  5608.5  153.41
  5613.3  153.46
BR U #Mann= 3
  3956.8     .14    4935    .048    5065     .14
BR U Banks=4935,5065
BR D #Sta/Elev= 71
  3956.8  148.41  3987.7  148.25  4116.8  147.57  4207.7  144.91  4216.8  144.64
  4247.7  142.35  4276.8   140.2  4307.7   138.9  4317.7  138.48  4497.7   130.9
  4506.8  130.52  4556.8  129.24  4557.7  129.25  4586.8  129.41  4656.8  126.49
  4666.8  126.77  4677.7  126.28  4686.8  125.87  4716.8  122.95  4726.8  125.55
  4736.8  126.91  4756.8  126.95  4757.7  126.99  4766.8  127.41  4777.7  127.36
  4806.8  127.24  4826.8  123.28  4836.8  122.49  4846.8  123.06  4856.8  123.13
  4876.8  122.22 4915.91  121.33    4916  121.33  4934.5  120.91    4935   120.9
    4950   117.8  4987.7   117.8    5050   117.8    5065   120.9  5065.5  121.19
  5068.5  122.91 5083.89  131.76    5084  131.82  5092.3  136.59  5132.3  138.41
  5142.3  138.38  5148.5  138.57  5172.3  139.32  5178.5  140.83  5182.3  141.75
  5188.5  141.83  5192.3  141.88  5198.5  142.62  5202.3  143.08  5268.5  144.46
  5308.5   145.3  5318.5  145.51  5322.3  145.59  5352.3  146.63  5358.5  147.21
  5362.3  147.56  5372.3  149.03  5382.3  150.96  5402.3   151.5  5412.1  151.36
  5428.5  151.51  5488.5  152.08  5508.5  152.27  5588.5  153.03  5608.5  153.21
  5613.3  153.26
BR D #Mann= 3
  3956.8     .14    4935    .048    5065     .14
BR D Banks=4935,5065
BC Design=,, 0 ,, 0 ,,,,,,
BC HTab HWMax=153.24
BC Use User HTab Curves=0
BC User HTab FreeFlow(D)= 0

Type RM Length L Ch R = 1 ,108432.1,671.7,671.7,671.7
BEGIN DESCRIPTION:
Downstream Section of Bridge/Culvert/Weir
END DESCRIPTION:
#Sta/Elev= 30
  3956.8  148.37  4116.8  147.53  4216.8   144.6  4276.8  140.16  4506.8  130.48
  4556.8   129.2  4586.8  129.37  4656.8  126.45  4666.8  126.73  4686.8  125.83
  4716.8  122.91  4726.8  125.51  4736.8  126.87  4806.8   127.2  4826.8  123.24
  4836.8  122.45  4856.8  123.09    4935  120.86    4950  117.76    5050  117.76
    5065  120.86  5092.3  136.55  5172.3  139.28  5182.3  141.71  5192.3  141.84
  5202.3  143.04  5352.3  146.59  5362.3  147.52  5382.3  150.92  5613.3  153.22
#Mann= 3 , 1 , 0
  3956.8     .14       0    4935    .048       0    5065     .14       0
#XS Ineff= 2 , 0
       0    4905   134.3    5095       0   137.7
Permanent Ineff=
       F       F
Bank Sta=4935,5065
XS Rating Curve= 0 ,0
Exp/Cntr=0.5,0.3

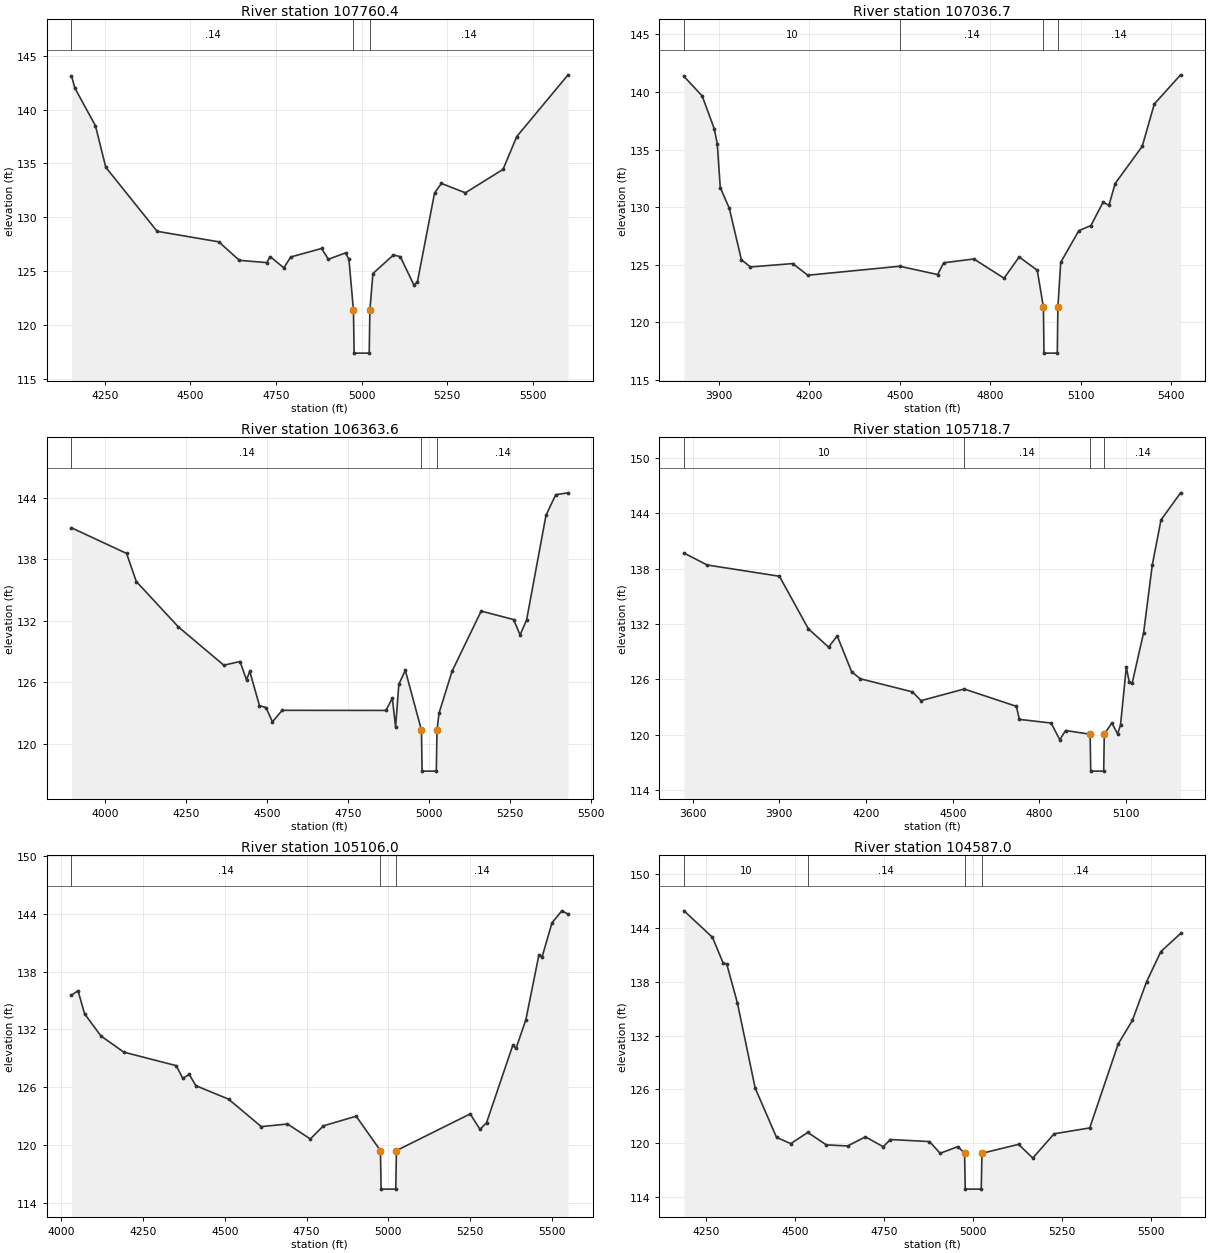
Type RM Length L Ch R = 1 ,107760.4,723.7,723.7,723.7
BEGIN DESCRIPTION:
Toisnot Swamp US 64.0
END DESCRIPTION:
#Sta/Elev= 30
  4152.8  143.14  4162.8     142  4222.8   138.5  4252.8  134.65  4402.8  128.69
  4582.8  127.71  4642.8  125.99  4722.8  125.78  4732.8  126.34  4772.8  125.29
  4792.8   126.3  4882.8  127.09  4902.8  126.09  4952.8  126.68  4962.8  126.08
    4976  121.36    4978  117.36    5022  117.36    5024  121.36  5032.8  124.76
  5092.8  126.49  5112.8  126.33  5152.8  123.67  5162.8     124  5212.8  132.25
  5232.8  133.14  5302.8  132.27  5412.8  134.45  5452.8   137.5  5602.5  143.24
#Mann= 3 , 1 , 0
  4152.8     .14       0    4976    .048       0    5024     .14       0
Bank Sta=4976,5024
XS Rating Curve= 0 ,0
Exp/Cntr=0.3,0.1

Type RM Length L Ch R = 1 ,107036.7,673.1,673.1,673.1
BEGIN DESCRIPTION:
Toisnot Swamp US 63.0
END DESCRIPTION:
#Sta/Elev= 30
  3785.7  141.35  3845.7  139.66  3885.7  136.82  3895.7  135.52  3905.7  131.71
  3935.7   129.9  3975.7  125.44  4005.7  124.82  4145.7  125.11  4195.7   124.1
  4499.9  124.88  4625.7  124.16  4645.7  125.18  4745.7  125.51  4845.7  123.84
  4895.7  125.69  4955.7  124.53    4976  121.34    4978  117.34    5022  117.34
    5024  121.34  5033.4  125.22  5093.4  127.97  5133.4  128.41  5173.4  130.42
  5193.4  130.18  5213.4  132.05  5303.4  135.29  5343.4  138.96  5430.4  141.49
#Mann= 4 , 1 , 0
  3785.7      10       0  4499.9     .14       0    4976    .048       0
    5024     .14       0
Bank Sta=4976,5024
XS Rating Curve= 0 ,0
Exp/Cntr=0.3,0.1

Type RM Length L Ch R = 1 ,106363.6,644.9,644.9,644.9
BEGIN DESCRIPTION:
Toisnot Swamp US 62.0
END DESCRIPTION:
#Sta/Elev= 30
  3896.2  141.05  4066.2  138.55  4096.2  135.81  4226.2  131.38  4366.2  127.65
  4416.2  128.01  4436.2  126.22  4446.2  127.06  4476.2  123.71  4496.2  123.52
  4516.2  122.13  4546.2  123.25  4866.2  123.24  4886.2  124.42  4896.2  121.63
  4906.2  125.79  4926.2  127.15    4976  121.32    4978  117.32  5021.9  117.32
  5023.9  121.32  5030.3  122.98  5070.3  127.05  5160.3  132.93  5260.3   132.1
  5280.3  130.61  5300.3  132.04  5360.3  142.27  5390.3  144.28  5428.3  144.46
#Mann= 3 , 1 , 0
  3896.2     .14       0    4976    .048       0  5023.9     .14       0
Bank Sta=4976,5023.9
XS Rating Curve= 0 ,0
Exp/Cntr=0.3,0.1

Type RM Length L Ch R = 1 ,105718.7,612.7,612.7,612.7
BEGIN DESCRIPTION:
Toisnot Swamp US 61.0
END DESCRIPTION:
#Sta/Elev= 30
  3570.5  139.68  3650.5  138.39  3900.5  137.17  4000.5  131.48  4070.5  129.49
  4100.5   130.7  4150.5  126.81  4180.5  126.06  4360.5  124.64  4390.5  123.69
  4539.9  124.95  4720.5  123.07  4730.5  121.66  4840.5  121.26  4870.5  119.45
  4890.5  120.45  4975.5  120.05  4977.5  116.05  5022.4  116.05  5024.4  120.05
  5050.6  121.27  5070.6  120.08  5080.6  121.07  5100.6  127.32  5110.6  125.75
  5120.6  125.55  5160.6  131.07  5190.6  138.42  5220.6  143.27  5288.4  146.21
#Mann= 4 , 1 , 0
  3570.5      10       0  4539.9     .14       0  4975.5    .048       0
  5024.4     .14       0
Bank Sta=4975.5,5024.4
XS Rating Curve= 0 ,0
Exp/Cntr=0.3,0.1

Type RM Length L Ch R = 1 ,105106.0,519,519,519
BEGIN DESCRIPTION:
Toisnot Swamp US 60.0
END DESCRIPTION:
#Sta/Elev= 30
  4031.4  135.56  4051.4     136  4071.4  133.61  4121.4  131.31  4191.4  129.63
  4351.4  128.23  4371.4  126.92  4391.4  127.31  4411.4  126.15  4511.4  124.75
  4611.4   121.9  4691.4  122.17  4761.4  120.62  4801.4  121.98  4901.4  122.98
  4975.6  119.41  4977.6  115.41  5022.4  115.41  5024.4  119.41  5249.9  123.22
  5279.9  121.61  5299.9  122.31  5379.9  130.33  5389.9  130.02  5419.9  132.98
  5459.9  139.73  5469.9  139.55  5499.9  143.06  5529.9   144.3  5548.9  143.96
#Mann= 3 , 1 , 0
  4031.4     .14       0  4975.6    .048       0  5024.4     .14       0
Bank Sta=4975.6,5024.4
XS Rating Curve= 0 ,0
Exp/Cntr=0.3,0.1

Type RM Length L Ch R = 1 ,104587.0,630,630,630
BEGIN DESCRIPTION:
Toisnot Swamp US 59.0
END DESCRIPTION:
#Sta/Elev= 30
    4187  145.94    4267  142.98    4297   140.1    4307  140.01    4337  135.66
    4387  126.15    4447  120.65    4487  119.95  4534.9   121.2    4587  119.81
    4647  119.69    4697  120.71    4747   119.6    4767  120.41    4877  120.18
    4907  118.87    4957  119.62  4975.6  118.87  4977.6  114.87  5022.5  114.87
  5024.5  118.87  5127.4  119.87  5167.4  118.34  5227.4  121.05  5327.4   121.7
  5407.4  131.07  5447.4  133.71  5487.4  138.03  5527.4  141.39  5582.9  143.41
#Mann= 4 , 1 , 0
    4187      10       0  4534.9     .14       0  4975.6    .048       0
  5024.5     .14       0
Bank Sta=4975.6,5024.5
XS Rating Curve= 0 ,0
Exp/Cntr=0.3,0.1

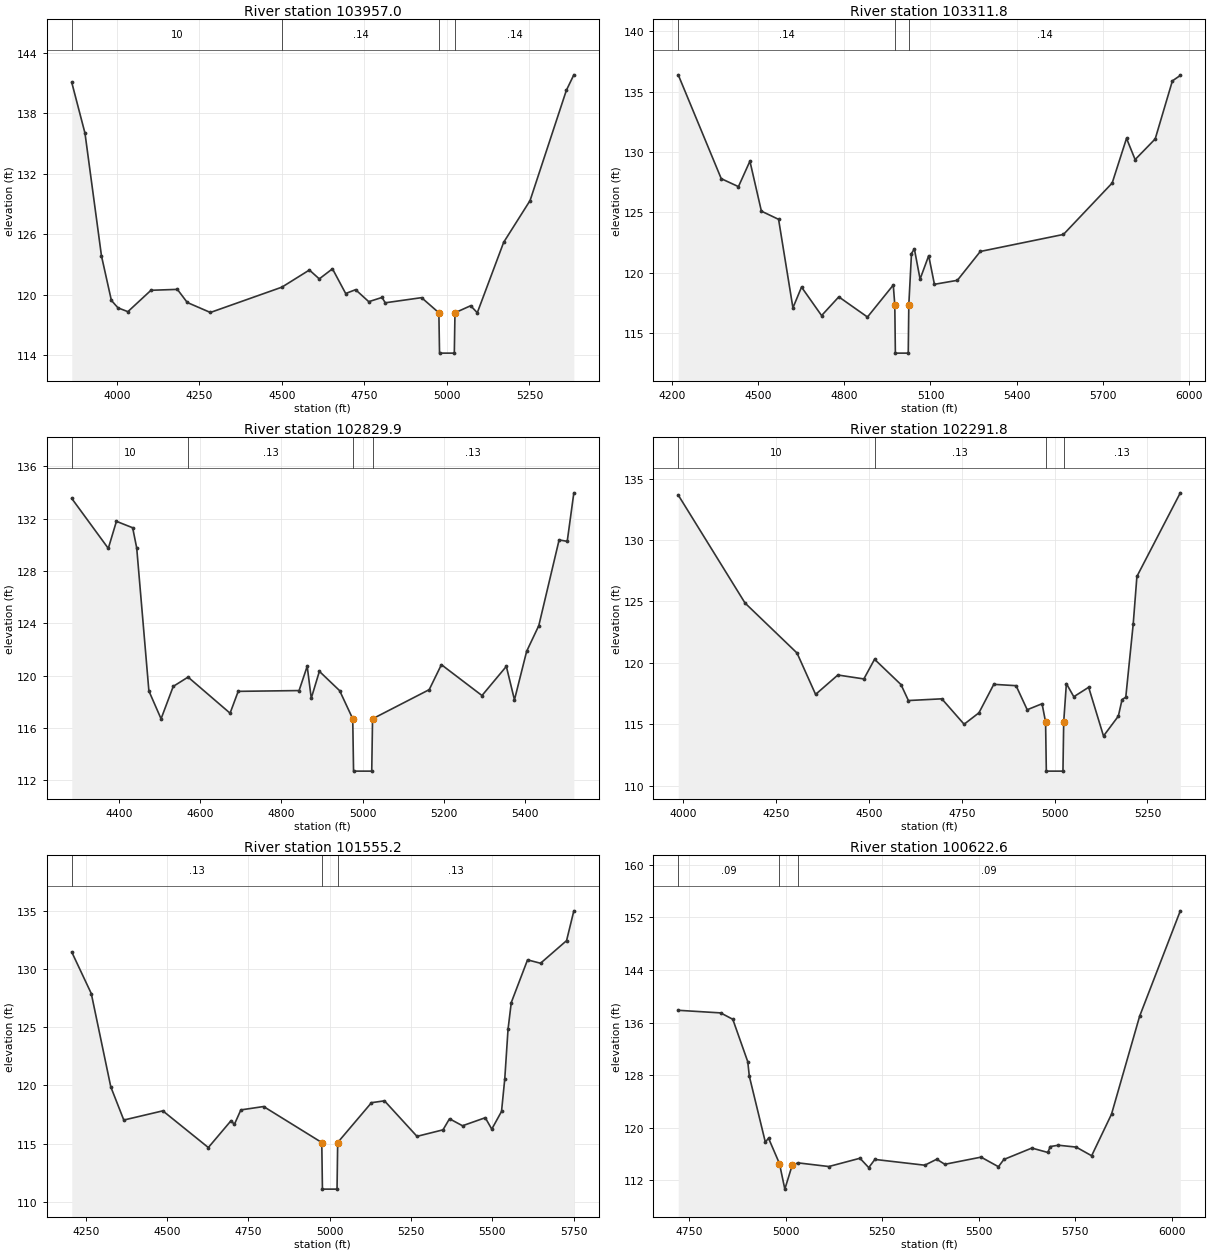
Type RM Length L Ch R = 1 ,103957.0,645.2,645.2,645.2
BEGIN DESCRIPTION:
Toisnot Swamp US 58.0
END DESCRIPTION:
#Sta/Elev= 30
  3863.2  141.05  3903.2  136.03  3953.2  123.86  3983.2  119.45  4003.2  118.71
  4033.2  118.33  4103.2  120.45  4183.2  120.54  4213.2  119.24  4283.2  118.25
  4499.9  120.76  4583.2  122.46  4613.2  121.58  4653.2  122.58  4693.2  120.13
  4723.2  120.51  4763.2  119.32  4803.2  119.74  4813.2  119.21  4923.2  119.72
  4975.6  118.22  4977.6  114.22  5022.4  114.22  5024.4  118.22    5072  118.92
    5092  118.22    5172  125.21    5252  129.35    5362  140.28  5384.6  141.81
#Mann= 4 , 1 , 0
  3863.2      10       0  4499.9     .14       0  4975.6    .048       0
  5024.4     .14       0
Bank Sta=4975.6,5024.4
XS Rating Curve= 0 ,0
Exp/Cntr=0.3,0.1

Type RM Length L Ch R = 1 ,103311.8,481.9,481.9,481.9
BEGIN DESCRIPTION:
Toisnot Swamp US 57.0
END DESCRIPTION:
#Sta/Elev= 30
  4220.2   136.4  4370.2   127.8  4430.2  127.14  4470.2  129.25  4510.2  125.11
  4570.2  124.43  4620.2   117.1  4650.2  118.82  4720.2  116.46  4780.2  118.01
  4880.2  116.34  4970.2  118.99  4975.5  117.35  4977.5  113.35  5022.4  113.35
  5024.4  117.35  5033.7   121.6  5043.7  121.99  5063.7  119.48  5093.7  121.42
  5113.7  119.05  5193.7  119.38  5273.7  121.77  5563.7  123.18  5733.7  127.44
  5783.7  131.14  5813.7  129.38  5883.7  131.09  5943.7   135.9  5971.3  136.35
#Mann= 3 , 1 , 0
  4220.2     .14       0  4975.5    .048       0  5024.4     .14       0
Bank Sta=4975.5,5024.4
XS Rating Curve= 0 ,0
Exp/Cntr=0.3,0.1

Type RM Length L Ch R = 1 ,102829.9,538.1,538.1,538.1
BEGIN DESCRIPTION:
Toisnot Swamp US 56.0
END DESCRIPTION:
#Sta/Elev= 30
  4283.4  133.55  4373.4  129.73  4393.4   131.8  4433.4  131.31  4443.4  129.76
  4473.4  118.83  4503.4   116.7  4533.4  119.18  4569.9  119.89  4673.4  117.13
  4693.4   118.8  4843.4  118.86  4863.4  120.72  4873.4  118.27  4893.4  120.33
  4943.4  118.85  4975.6   116.7  4977.6   112.7  5022.4   112.7  5024.4   116.7
    5164  118.93    5194  120.84    5294  118.48    5354  120.71    5374  118.15
    5404  121.86    5434  123.83    5484  130.38    5504  130.27  5520.3  133.98
#Mann= 4 , 1 , 0
  4283.4      10       0  4569.9     .13       0  4975.6    .048       0
  5024.4     .13       0
Bank Sta=4975.6,5024.4
XS Rating Curve= 0 ,0
Exp/Cntr=0.3,0.1

Type RM Length L Ch R = 1 ,102291.8,736.6,736.6,736.6
BEGIN DESCRIPTION:
Toisnot Swamp US 55.0
END DESCRIPTION:
#Sta/Elev= 30
  3986.1  133.67  4166.1  124.87  4306.1   120.8  4356.1  117.43  4416.1  119.01
  4486.1  118.69  4514.9  120.29  4586.1  118.23  4606.1  116.93  4696.1  117.07
  4756.1     115  4796.1  115.93  4836.1  118.25  4896.1  118.14  4926.1  116.18
  4966.1  116.67  4975.6  115.18  4977.6  111.18  5022.4  111.18  5024.4  115.18
  5031.6  118.31  5051.6  117.24  5091.6  118.01  5131.6  114.04  5171.6  115.66
  5181.6  117.01  5191.6   117.2  5211.6  123.15  5221.6  127.04  5338.5  133.85
#Mann= 4 , 1 , 0
  3986.1      10       0  4514.9     .13       0  4975.6    .048       0
  5024.4     .13       0
Bank Sta=4975.6,5024.4
XS Rating Curve= 0 ,0
Exp/Cntr=0.3,0.1

Type RM Length L Ch R = 1 ,101555.2,932.6,932.6,932.6
BEGIN DESCRIPTION:
Toisnot Swamp US 54.0
END DESCRIPTION:
#Sta/Elev= 30
  4206.7  131.44  4266.7  127.88  4326.7  119.87  4366.7  117.02  4486.7  117.81
  4626.7  114.66  4696.7  116.97  4706.7  116.64  4726.7  117.89  4796.7  118.18
  4975.6  115.09  4977.6  111.09  5022.5  111.09  5024.5  115.09  5128.4  118.51
  5168.4  118.67  5268.4  115.62  5348.4  116.18  5368.4  117.13  5408.4  116.53
  5478.4  117.22  5498.4  116.24  5528.4  117.76  5538.4  120.57  5548.4  124.81
  5558.4  127.11  5608.4  130.77  5648.4  130.48  5728.4  132.42  5750.8  134.98
#Mann= 3 , 1 , 0
  4206.7     .13       0  4975.6    .048       0  5024.5     .13       0
Bank Sta=4975.6,5024.5
XS Rating Curve= 0 ,0
Exp/Cntr=0.3,0.1

Type RM Length L Ch R = 1 ,100622.6,2270.5,2270.5,2270.5
BEGIN DESCRIPTION:
Toisnot Swamp US 53.5
END DESCRIPTION:
#Sta/Elev= 30
  4721.4 137.866 4831.29  137.47  4862.7   136.5 4901.52  130.04 4905.53  127.84
 4947.01  117.81  4955.3   118.4 4983.56  114.55 4997.55  110.65 5016.44  114.26
 5031.27  114.65 5111.51  114.09 5192.22  115.35 5214.92  113.92 5230.75  115.17
 5360.03  114.29 5391.03   115.2 5411.97  114.43 5505.85  115.52 5550.89  114.06
 5564.81  115.16 5637.38   116.9 5678.81  116.23 5685.03  117.13 5706.16  117.33
 5752.06  117.05 5792.31  115.73 5843.79  122.06 5916.54  136.95    6022 153.004
#Mann= 3 ,-1 , 0
  4721.4     .09       0 4983.56     .05       0 5031.27     .09       0
Bank Sta=4983.56,5016.44
XS Rating Curve= 0 ,0
Exp/Cntr=0.3,0.1

Chan Stop Cuts=-1
Use User Specified Reach Order=0