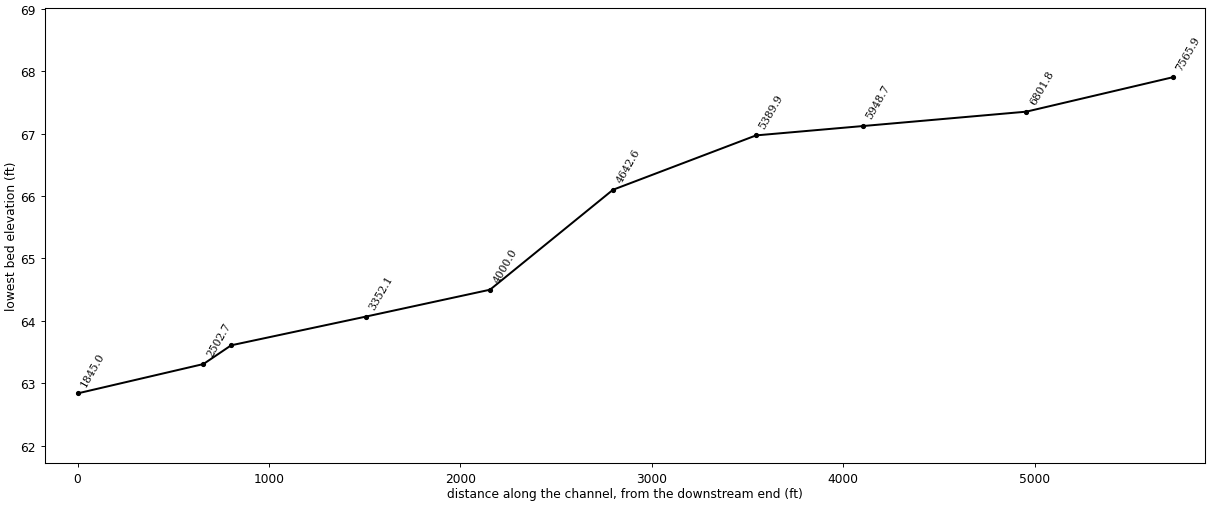
--- White_Oak_Swamp_DS_030314.prj (project) ---

Proj Title=White Oak Swamp DS - Wilson County
Current Plan=p01
Default Exp/Contr=0.3,0.1
English Units
Geom File=g01
Flow File=f01
Flow File=f02
Plan File=p01
Plan File=p02
Y Axis Title=Elevation
X Axis Title(PF)=Main Channel Distance
X Axis Title(XS)=Station
BEGIN DESCRIPTION:
NEUSE RIVER BASIN
Little Contentnea Creek Sub-basin
WHITE OAK SWAMP
(Flood Hazard, Floodway) Model
Prepared by: Andrew J. Bonner   Date: 11/7/2002
Watershed Concepts
3333 Regency Pkwy
Cary, North Carolina 27511
END DESCRIPTION:
DSS Export Rating Curves= 0
DSS Export Rating Curve Sorted= 0
DSS Export Volume Flow Curves= 0
DXF OffsetX= 0
DXF OffsetY= 0
DXF ScaleX= 1
DXF ScaleY= 10

--- White_Oak_Swamp_DS_030314.p01 (plan) ---

Plan Title=100 Year Single
Version=Version 3.0.1  Mar 2001
Short Identifier=Plan01
Geom File=g01
Flow File=f01
Subcritical Flow
K Sum by GR= 0
Std Step Tol= 0.01
Critical Tol= 0.01
Num of Std Step Trials= 20
Max Error Tol= 0.3
Flow Tol Ratio= 0.001
Split Flow NTrial= 30
Split Flow Tol= 0.02
Split Flow Ratio= 0.02
Log Output Level= 0
Friction Slope Method= 1
Unsteady Friction Slope Method= 2
Parabolic Critical Depth
Global Vel Dist= 0 , 0 , 0
Global Log Level= 0
CheckData=True
Encroach Param=-1 ,0,0, 2
Encroach River=White Oak DS
Encroach Reach=Reach - 1
Encroach Node=7565.9
       1    4770    5590
Encroach Node=6801.8
       4      .7
Encroach Node=5948.7
       4      .7
Encroach Node=5389.9
       4      .7
Encroach Node=4642.6
       4      .7
Encroach Node=4000.0
       4      .7
Encroach Node=3352.1
       4      .7
Encroach Node=2647.7
       1    4950    5225
Encroach Node=2575.2
       1    4950    5225
Encroach Node=2502.7
       1    4950    5225
Encroach Node=1845.0
       4      .7
Computation Interval=1HOUR
Output Interval=1HOUR
Run HTab= 0
Run UNet= 0
Run PostProcess= 0
UNET Theta= 1
UNET ZTol= 0.02
UNET ZSATol= 0.1
UNET MxIter= 20
UNET MaxInSteps= 20
UNET DtIC= 0
UNET DtMin= 0
UNET MaxCRTS= 20
UNET WFStab= 2
UNET SFStab= 1
UNET WFX= 1
UNET SFX= 1
UNET Convert EG Bridges=-1
UNET Use Existing IB Tables=-1
Instantaneous Interval=1HOUR
Write IC File= 0
Write Velocity= 0
Write Detailed= 0

--- White_Oak_Swamp_DS_030314.p02 (plan) ---

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Plan Title=Multi_Profile
Program Version=4.00
Short Identifier=Multi_Profile
Geom File=g01
Flow File=f02
Unsteady Bridges Friction Slope Method= 1
Encroach Param=-1 ,0,0, 0
Run WQNet= 0
UNET Theta Warmup= 1
UNET ZSATol= 0.05
UNET MaxInSteps= 0
UNET DSS MLevel= 4
UNET DZMax Abort= 100
UNET Convert EG Bridges= 0
UNET Froude Reduction=False
UNET Froude Limit= 1
UNET Froude Power= 10
UNET Time Slicing=0,0, 5
Echo Input=False
Echo Output=False
Detailed Automatic Start=False, 10
WQ ULTIMATE=-1
WQ Max Comp Step=1HOUR
WQ Output Interval=15MIN
WQ Output Selected Increments= 0
WQ Output face flow=0
WQ Output face velocity=0
WQ Output face area=0
WQ Output face dispersion=0
WQ Output cell volume=0
WQ Output cell surface area=0
WQ Output cell continuity=0
WQ Output face conc=0
WQ Output face dconc_dx=0
WQ Output face courant=0
WQ Output face peclet=0
WQ Output face adv mass=0
WQ Output face disp mass=0
WQ Output cell mass=0
WQ Output cell source sink temp=0
WQ Output cell source sink nsm=0
WQ Output MaxMinRange=-1
WQ Daily Max Min Mean=-1
WQ Daily Range=0
WQ Daily Time=0
WQ Create Restart=0
WQ Fixed Restart=0
WQ System Summary=False
Sorting and Armoring Iterations= 10
XS Update Threshold= 0.02
Hydraulics Update Threshold= 0.02
Energy Slope Method= 1
Volume Change Method= 0
XS Weighting Method= 0
Number of US Weighted Cross Sections= 1
Number of DS Weighted Cross Sections= 1
Upstream XS Weight=0.25
Main XS Weight=0.5
Downstream XS Weight=0.25
Number of DS XS's Weighted with US Boundary= 1
Upstream Boundary Weight= 1
Weight of XSs Associated with US Boundary= 0
Number of US XS's Weighted with DS Boundary= 1
Downstream Boundary Weight= 0.5
Weight of XSs Associated with DS Boundary= 0.5
Sediment Output Level= 4
Mass or Volume Output= 0
Output Increment Type= 1
Profile and TS Output Increment= 10
XS Output Flag= 0
XS Output Increment= 10
Disregard all LS=0
Disregard all Conn=0
Disregard all Breaches=0
Disregard all Pumps=0

--- White_Oak_Swamp_DS_030314.f01 (steady flow) ---

Flow Title= 100 Year Single
Version=Version 3.0.1  Mar 2001
Number of Profiles= 2
Profile Names=100-Year,AFW
River Rch & RM=White Oak DS,Reach - 1       ,7565.9
    6296    6296
River Rch & RM=White Oak DS,Reach - 1       ,4000.0
    6427    6427
Boundary for River Rch & Prof#=White Oak DS,Reach - 1       , 1
Up Type= 0
Dn Type= 3
Dn Slope=.00072
DSS Import GetInterval= 0
DSS Import GetPeak= 0
DSS Import FillOption= 0

--- White_Oak_Swamp_DS_030314.f02 (steady flow) ---

Flow Title=Multi_Profile
Program Version=4.00
Number of Profiles= 7
Profile Names=10yr,25yr,50yr,500yr,100yr-10%,100yr-20%,100yr-35%
River Rch & RM=White Oak DS,Reach - 1       ,7565.9
    3056    4114    5032    8771    6195    7940    9701
River Rch & RM=White Oak DS,Reach - 1       ,4000.0
    3274    4400    5376    9341    6589    8445   10318
Boundary for River Rch & Prof#=White Oak DS,Reach - 1       , 1
Up Type= 0
Dn Type= 3
Dn Slope=0.00072
Boundary for River Rch & Prof#=White Oak DS,Reach - 1       , 2
Up Type= 0
Dn Type= 3
Dn Slope=0.00072
Boundary for River Rch & Prof#=White Oak DS,Reach - 1       , 3
Up Type= 0
Dn Type= 3
Dn Slope=0.00072
Boundary for River Rch & Prof#=White Oak DS,Reach - 1       , 4
Up Type= 0
Dn Type= 3
Dn Slope=0.00072
Boundary for River Rch & Prof#=White Oak DS,Reach - 1       , 5
Up Type= 0
Dn Type= 3
Dn Slope=0.00072
Boundary for River Rch & Prof#=White Oak DS,Reach - 1       , 6
Up Type= 0
Dn Type= 3
Dn Slope=0.00072
Boundary for River Rch & Prof#=White Oak DS,Reach - 1       , 7
Up Type= 0
Dn Type= 3
Dn Slope=0.00072
DSS Import GetInterval= 0
DSS Import GetPeak= 0
DSS Import FillOption= 0

--- White_Oak_Swamp_DS_030314.g01 (geometry) ---

Geom Title=Geom 01 by CodeH2 for Windows

River Reach=White Oak DS,Reach - 1
Reach XY= 30
   .589838934695   .936143170405   .571041103787   .899720917635
   .584882214844   .868492687022   .582398340622   .855007474360
   .553298085835   .846844054901   .546554552685   .829455081708
   .528811534734   .814549982737   .496517462569   .796806964786
   .474158887294   .791837362704   .470255126763   .784739784795
   .470611025159   .755641383646   .483742193062   .736122580989
   .477708603067   .696730930917   .485870168888   .663726915598
   .477708603067   .638174522946   .500065324705   .557617291734
   .471320968314   .537744444318   .442930656681   .489835330029
   .415604332961   .477414105280   .413120458739   .455411428401
   .377632569198   .383015763010   .388278009242   .351787532397
   .384374248710   .256323348576   .370534991290   .242484091156
   .330787442822   .227933036943   .271522945334   .187123354199
   .264779412184   .165830620475   .266909241648   .148085748886
   .279330466397   .124663185697   .275327876551   .104141695018

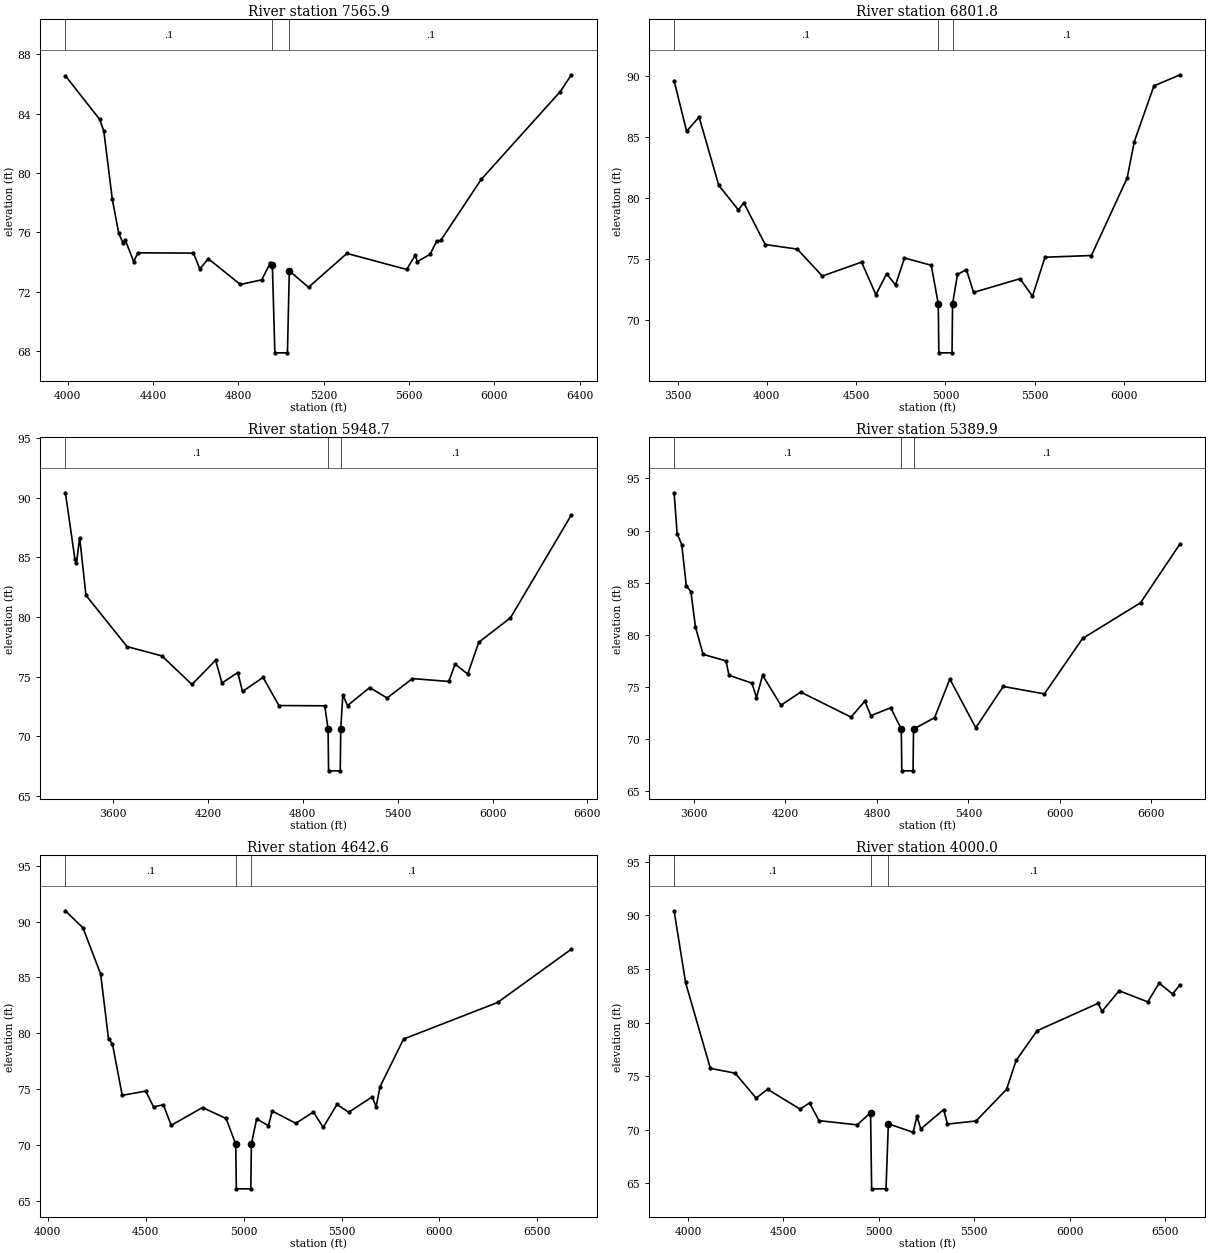
Type RM Length L Ch R = 1 ,7565.9,764.1,764.1,764.1
BEGIN DESCRIPTION:
White Oak Swamp DS 7.5 (Tie-in to Effective Study)
END DESCRIPTION:
#Sta/Elev= 30
  3988.8   86.54  4148.8   83.62  4168.8   82.83  4208.8   78.22  4238.8   75.94
  4258.8   75.29  4268.8   75.52  4308.8   74.04  4328.8   74.63  4588.8   74.61
  4618.8   73.55  4658.8   74.23  4808.8    72.5  4908.8   72.81  4948.8   73.94
  4958.8   73.83  4970.6    67.9 5029.55    67.9  5038.3   73.42  5128.3   72.31
  5308.3   74.59  5588.3   73.51  5628.3   74.46  5638.3   74.04  5698.3   74.53
  5728.3    75.4  5748.3   75.47  5938.3   79.58  6308.3   85.48  6360.5   86.61
#Mann= 3 , 1 , 0
 3988.80     0.1       0  4958.8    0.04       0  5038.3     0.1       0
Bank Sta=4958.80,5038.30
Exp/Cntr=0.3,0.1

Type RM Length L Ch R = 1 ,6801.8,853.1,853.1,853.1
BEGIN DESCRIPTION:
White Oak Swamp DS 7.0
END DESCRIPTION:
#Sta/Elev= 30
  3480.7    89.6  3550.7   85.47  3620.7   86.63  3730.7   81.05  3840.7   79.03
  3870.7   79.62  3990.7   76.21  4170.7   75.83  4310.7   73.63  4530.7   74.77
  4610.7    72.1  4670.7   73.82  4720.7    72.9  4770.7   75.11  4920.7   74.51
  4960.1   71.35  4963.1   67.35 5037.05   67.35 5040.05   71.35  5067.6   73.76
  5117.6   74.16  5157.6   72.29  5417.6   73.41  5487.6   71.98  5557.6   75.17
  5817.6   75.31  6017.6   81.64  6057.6   84.62  6167.6   89.18  6314.3   90.09
#Mann= 3 , 1 , 0
 3480.70     0.1       0  4960.1    0.04       0 5040.05     0.1       0
Bank Sta=4960.10,5040.05
Exp/Cntr=0.3,0.1

Type RM Length L Ch R = 1 ,5948.7,558.8,558.8,558.8
BEGIN DESCRIPTION:
White Oak Swamp DS 6.0
END DESCRIPTION:
#Sta/Elev= 30
    3299   90.42    3359   84.87    3369    84.5    3389   86.67    3429   81.83
    3689   77.53    3909   76.75    4099   74.36    4249   76.39    4289   74.48
    4389   75.36    4419   73.77    4549   74.95    4649   72.59    4939   72.57
  4960.1   70.62  4963.1   67.12 5037.05   67.12 5040.05   70.62  5053.3   73.48
  5083.3   72.59  5223.3    74.1  5333.3   73.22  5493.3   74.85  5723.3   74.61
  5763.3   76.06  5843.3   75.23  5913.3    77.9  6113.3   79.94  6498.7   88.57
#Mann= 3 , 1 , 0
 3299.00     0.1       0  4960.1    0.04       0 5040.05     0.1       0
Bank Sta=4960.10,5040.05
Exp/Cntr=0.3,0.1

Type RM Length L Ch R = 1 ,5389.9,747.3,747.3,747.3
BEGIN DESCRIPTION:
White Oak Swamp DS 5.0
END DESCRIPTION:
#Sta/Elev= 30
  3470.5   93.63  3490.5    89.7  3520.5   88.67  3550.5    84.7  3580.5   84.16
  3610.5   80.76  3660.5   78.14  3810.5   77.51  3830.5   76.13  3980.5   75.38
  4010.5      74  4050.5   76.13  4170.5   73.26  4300.5   74.52  4630.5   72.12
  4720.5   73.65  4760.5   72.26  4890.5   73.02  4960.1   70.97  4963.1   66.97
 5037.05   66.97 5040.05   70.97  5178.2   72.07  5278.2   75.77  5448.2    71.1
  5628.2   75.06  5898.2   74.35  6148.2   79.66  6528.2   83.08  6787.9   88.74
#Mann= 3 , 1 , 0
 3470.50     0.1       0  4960.1    0.04       0 5040.05     0.1       0
Bank Sta=4960.10,5040.05
Exp/Cntr=0.3,0.1

Type RM Length L Ch R = 1 ,4642.6,642.6,642.6,642.6
BEGIN DESCRIPTION:
White Oak Swamp DS 4.0
END DESCRIPTION:
#Sta/Elev= 30
  4090.6   90.96  4180.6   89.42  4270.6    85.3  4310.6   79.51  4330.6   79.07
  4380.6   74.46  4500.6   74.84  4540.6   73.42  4590.6   73.62  4630.6   71.78
  4790.6   73.37  4910.6   72.39  4960.1    70.1  4963.1    66.1 5037.05    66.1
 5040.05    70.1  5066.7   72.35  5126.7   71.75  5146.7   73.05  5266.7   71.96
  5356.7   72.97  5406.7   71.59  5476.7   73.65  5536.7   72.95  5656.7   74.32
  5676.7   73.43  5696.7   75.23  5816.7   79.49  6296.7   82.76  6673.6   87.53
#Mann= 3 , 1 , 0
 4090.60     0.1       0  4960.1    0.04       0 5040.05     0.1       0
Bank Sta=4960.10,5040.05
Exp/Cntr=0.3,0.1

Type RM Length L Ch R = 1 ,4000.0,647.9,647.9,647.9
BEGIN DESCRIPTION:
White Oak Swamp DS 3.0
END DESCRIPTION:
#Sta/Elev= 30
  3926.7   90.44  3986.7   83.75  4116.7   75.74  4246.7   75.29  4356.7   72.96
  4416.7   73.79  4586.7   71.94  4636.7   72.51  4686.7   70.86  4886.7   70.47
  4956.7   71.61 4962.35    64.5 5037.65    64.5    5050   70.57    5180   69.77
    5200   71.26    5220   70.09    5340   71.89    5360   70.54    5510   70.83
    5670   73.79    5720   76.48    5830   79.25    6150   81.81    6170   81.05
    6260   82.98    6410   81.94    6470   83.69    6540   82.68  6579.7   83.54
#Mann= 3 , 1 , 0
 3926.70     0.1       0  4956.7    0.04       0    5050     0.1       0
Bank Sta=4956.70,5050.00
Exp/Cntr=0.3,0.1

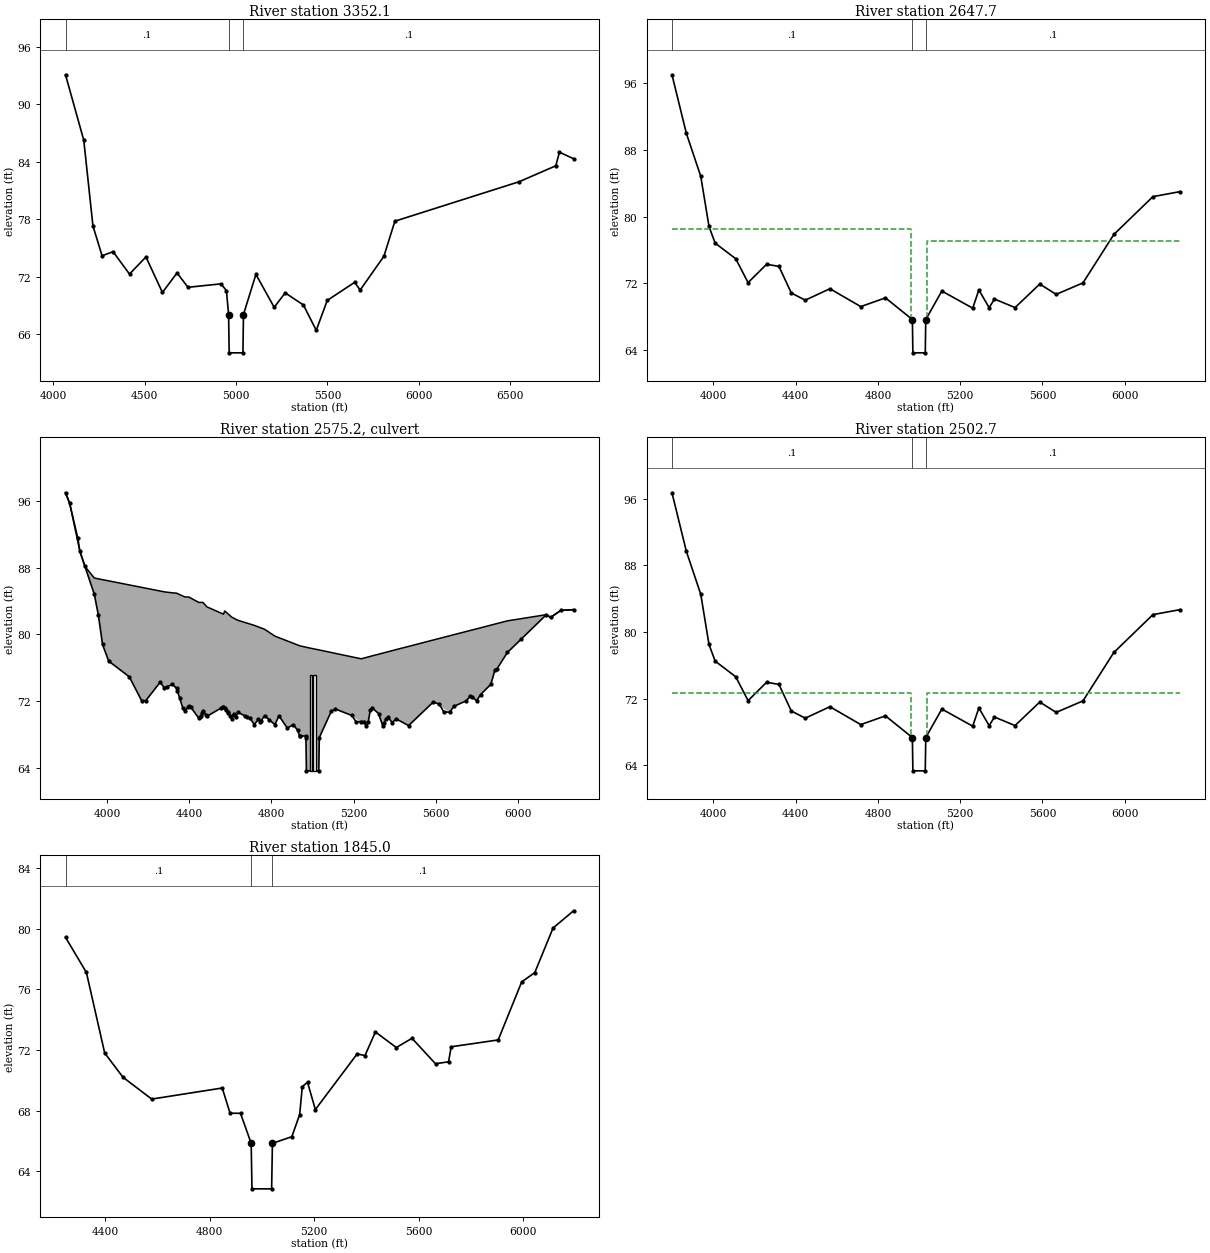
Type RM Length L Ch R = 1 ,3352.1,704.4,704.4,704.4
BEGIN DESCRIPTION:
White Oak Swamp DS 2.0
END DESCRIPTION:
#Sta/Elev= 30
  4067.3   93.09  4167.3   86.25  4217.3   77.32  4267.3    74.2  4327.3   74.63
  4417.3   72.29  4507.3   74.08  4597.3   70.37  4677.3   72.41  4737.3   70.91
  4917.3   71.27  4947.3   70.57 4959.35   68.07 4962.35   64.07 5037.65   64.07
 5040.65   68.07  5108.7   72.26  5208.7   68.82  5268.7   70.33  5368.7   69.06
  5438.7   66.42  5498.7   69.54  5648.7   71.43  5678.7   70.62  5808.7   74.15
  5868.7   77.81  6548.7   81.93  6748.7   83.59  6768.7   85.01  6845.9   84.33
#Mann= 3 , 1 , 0
 4067.30     0.1       0 4959.35    0.04       0 5040.65     0.1       0
Bank Sta=4959.35,5040.65
Exp/Cntr=0.5,0.3

Type RM Length L Ch R = 1 ,2647.7,145,145,145
BEGIN DESCRIPTION:
Upstream Section of Bridge/Culvert/Weir
END DESCRIPTION:
#Sta/Elev= 30
  3798.8   97.04  3868.8   89.99  3938.8   84.83  3978.8    78.8  4008.8    76.8
  4108.8   74.92  4168.8   72.05  4258.8   74.26  4318.8      74  4378.8   70.81
  4446.6   69.94  4566.6   71.32  4716.6   69.17  4836.6   70.22 4967.48   67.61
 4969.88   63.61 5030.12   63.61 5032.52   67.61  5110.7   71.04  5260.7   68.98
  5290.7   71.17  5340.7   69.04  5366.6   70.08  5466.6   69.05  5586.6   71.88
  5666.6   70.64  5796.8   72.02  5946.8   77.84  6136.8   82.39  6268.5   82.99
#Mann= 3 , 1 , 0
 3798.80     0.1       0 4967.48    0.04       0 5032.52     0.1       0
#XS Ineff= 2 , 0
       0    4962    78.5    5038       0    77.1
Bank Sta=4967.48,5032.52
Exp/Cntr=0.5,0.3

Type RM Length L Ch R = 2 ,2575.2,,,
BEGIN DESCRIPTION:
US Hwy 264-TOR
Structure ID: WOS - US 264
Approximate Survey Structure
END DESCRIPTION:
Bridge Culvert--1,0,-1,-1, 0
Deck Dist Width WeirC Skew NumUp NumDn MinLoCord MaxHiCord MaxSubmerge Is_Ogee
10,125,3.21,, 60, 60,,,0.95,0,1,1,,
  3798.8  3818.8  3868.8  3893.1  3938.8  3958.8  3978.8  4008.8  4108.8  4168.8
  4188.8  4258.8  4278.8  4318.8  4338.8  4378.8  4398.8  4446.6  4466.6  4486.6
  4566.6  4573.1  4606.6  4636.6  4716.6  4766.6  4816.6  4836.6  4876.6  4906.6
  4936.6  4966.6 4967.48 4969.88 5030.12 5032.52  5090.7  5110.7  5236.3  5260.7
  5270.7  5280.7  5290.7  5320.7  5340.7  5366.6  5386.6  5406.6  5466.6  5586.6
  5666.6  5766.6  5796.8  5866.8  5886.8  5946.8  6136.8  6156.8  6206.8  6268.5
   97.03   95.78   89.98   88.19   86.78   86.68   86.58   86.44   85.95   85.66
   85.56   85.22   85.12      85   84.96   84.51   84.49   83.85   83.85   83.31
   82.44   82.82   82.08    81.7   81.09   80.62    79.8    79.6   79.22   78.93
   78.64   78.47   78.46   78.45   78.14   78.13   77.83   77.72   77.07   77.23
    77.3   77.36   77.43   77.62   77.75   77.92   78.05   78.18   78.56   79.33
   79.84   80.48   80.67   81.12   81.25   81.63   82.38   82.04   82.89   82.98
   97.03   95.78   89.98   88.19   84.82   82.29   78.79   76.79   74.91   72.04
   72.03   74.25   73.59   73.99   73.51    70.8   71.43   69.93   70.85   70.16
   71.31   71.11   69.84   70.63   69.16   70.23   69.15   70.21   68.75   69.15
   67.82   67.77    67.6    63.6    63.6    67.6   70.75   71.03   69.52   68.97
    69.5   70.97   71.16   70.48   69.03   70.07    69.4   69.84   69.04   71.87
   70.63   72.57   72.01   74.01   75.77   77.83   82.38   82.04   82.89   82.98
  3798.8  3818.8  3868.8  3893.1  3938.8  3958.8  3978.8  4008.8  4108.8  4168.8
  4188.8  4258.8  4278.8  4318.8  4338.8  4378.8  4398.8  4446.6  4466.6  4486.6
  4566.6  4573.1  4606.6  4636.6  4716.6  4766.6  4816.6  4836.6  4876.6  4906.6
  4936.6  4966.6 4967.48 4969.88 5030.12 5032.52  5090.7  5110.7  5236.3  5260.7
  5270.7  5280.7  5290.7  5320.7  5340.7  5366.6  5386.6  5406.6  5466.6  5586.6
  5666.6  5766.6  5796.8  5866.8  5886.8  5946.8  6136.8  6156.8  6206.8  6268.5
   96.88   95.63   89.83   88.05   86.78   86.68   86.58   86.44   85.95   85.66
   85.56   85.22   85.12      85   84.96   84.51   84.49   83.85   83.85   83.31
   82.44   82.82   82.08    81.7   81.09   80.62    79.8    79.6   79.22   78.93
   78.64   78.47   78.46   78.45   78.14   78.13   77.83   77.72   77.07   77.23
    77.3   77.36   77.43   77.62   77.75   77.92   78.05   78.18   78.56   79.33
   79.84   80.48   80.67   81.12   81.25   81.63   82.23   81.89   82.74   82.83
   96.73   95.48   89.68   87.89   84.52   81.99   78.49   76.49   74.61   71.74
   71.73   73.95   73.29   73.69   73.21    70.5   71.13   69.63   70.55   69.86
   71.01   70.81   69.54   70.33   68.86   69.93   68.85   69.91   68.45   68.85
   67.52   67.47    67.3    63.3    63.3    67.3   70.45   70.73   69.22   68.67
    69.2   70.67   70.86   70.18   68.73   69.77    69.1   69.54   68.74   71.57
   70.33   72.27   71.71   73.71   75.47   77.53   82.08   81.74   82.59   82.68
BR Coef= 1 , 0 , 0 ,1.25, 0 ,,,0.8,-1,2,0,
Wspro=,,,, 1 ,,,, 0 ,,,, 0 ,,,,-1 ,-1 ,-1 , 0 , 0 , 0 , 0 , 0
Culvert=2,11.5,13.5,125.0,0.012,0.4,1.0,8,1,63.60,4991.96,63.30,4991.96,Culvert #1  ,0,10
Culvert=2,11.5,13.5,125.0,0.012,0.4,1.0,8,1,63.60,5007.96,63.30,5007.96,Culvert #2  ,0,10
BC Design=,, 0 ,, 0 ,,,,,,
BR U #Sta/Elev= 102
  3798.8   97.03  3818.8   95.78  3858.8   91.54  3868.8   89.98  3893.1   88.19
  3938.8   84.82  3958.8   82.29  3978.8   78.79  4008.8   76.79  4108.8   74.91
  4168.8   72.04  4188.8   72.03  4258.8   74.25  4278.8   73.59  4293.1   73.73
  4318.8   73.99  4338.8   73.51  4343.1   73.18  4353.1    72.4  4368.8   71.18
  4378.8    70.8  4393.1   71.25  4398.8   71.43  4406.6   71.29  4446.6   69.93
  4453.1   70.07  4456.6   70.15  4463.1   70.61  4466.6   70.85  4483.1   70.28
  4486.6   70.16  4553.1   71.12  4563.1   71.26  4566.6   71.31  4573.1   71.11
  4579.4   70.92  4586.6    70.7  4589.4   70.58  4599.4   70.15  4606.6   69.84
  4616.6   70.48  4619.4   70.37  4626.6   70.07  4636.6   70.63  4669.4   70.23
  4679.4   70.11  4696.6    69.9  4716.6   69.16  4736.6   69.81  4746.6   69.52
  4749.4   69.62  4766.6   70.23  4789.4   69.74  4816.6   69.15  4836.6   70.21
  4876.6   68.75  4906.6   69.15  4926.6   68.48  4936.6   67.82  4939.4   67.82
  4966.6   67.77 4967.48    67.6 4969.88    63.6 5030.12    63.6 5032.52    67.6
  5090.7   70.75  5110.7   71.03  5190.7   70.26  5210.7    69.5  5236.3   69.52
  5250.7   69.53  5260.7   68.97  5270.7    69.5  5280.7   70.97  5290.7   71.16
  5320.7   70.48  5340.7   69.03  5346.3    69.3  5356.6   69.81  5366.6   70.07
  5386.6    69.4  5406.6   69.84  5466.6   69.04  5586.6   71.87  5616.6   71.61
  5636.6   70.72  5666.6   70.63  5686.6   71.35  5746.6   72.02  5766.6   72.57
  5776.8    72.5  5796.8   72.01  5816.8   72.77  5866.8   74.01  5886.8   75.77
  5896.8   75.89  5946.8   77.83  6012.4    79.4  6136.8   82.38  6156.8   82.04
  6206.8   82.89  6268.5   82.98
BR U #Mann= 3
 3798.80     0.1 4967.48    0.04 5032.52     0.1
BR U Banks=4967.48,5032.52
BR D #Sta/Elev= 102
  3798.8   96.73  3818.8   95.48  3858.8   91.24  3868.8   89.68  3893.1   87.89
  3938.8   84.52  3958.8   81.99  3978.8   78.49  4008.8   76.49  4108.8   74.61
  4168.8   71.74  4188.8   71.73  4258.8   73.95  4278.8   73.29  4293.1   73.43
  4318.8   73.69  4338.8   73.21  4343.1   72.88  4353.1    72.1  4368.8   70.88
  4378.8    70.5  4393.1   70.95  4398.8   71.13  4406.6   70.99  4446.6   69.63
  4453.1   69.77  4456.6   69.85  4463.1   70.31  4466.6   70.55  4483.1   69.98
  4486.6   69.86  4553.1   70.82  4563.1   70.96  4566.6   71.01  4573.1   70.81
  4579.4   70.62  4586.6    70.4  4589.4   70.28  4599.4   69.85  4606.6   69.54
  4616.6   70.18  4619.4   70.07  4626.6   69.77  4636.6   70.33  4669.4   69.93
  4679.4   69.81  4696.6    69.6  4716.6   68.86  4736.6   69.51  4746.6   69.22
  4749.4   69.32  4766.6   69.93  4789.4   69.44  4816.6   68.85  4836.6   69.91
  4876.6   68.45  4906.6   68.85  4926.6   68.18  4936.6   67.52  4939.4   67.52
  4966.6   67.47 4967.48    67.3 4969.88    63.3 5030.12    63.3 5032.52    67.3
  5090.7   70.45  5110.7   70.73  5190.7   69.96  5210.7    69.2  5236.3   69.22
  5250.7   69.23  5260.7   68.67  5270.7    69.2  5280.7   70.67  5290.7   70.86
  5320.7   70.18  5340.7   68.73  5346.3      69  5356.6   69.51  5366.6   69.77
  5386.6    69.1  5406.6   69.54  5466.6   68.74  5586.6   71.57  5616.6   71.31
  5636.6   70.42  5666.6   70.33  5686.6   71.05  5746.6   71.72  5766.6   72.27
  5776.8    72.2  5796.8   71.71  5816.8   72.47  5866.8   73.71  5886.8   75.47
  5896.8   75.59  5946.8   77.53  6012.4    79.1  6136.8   82.08  6156.8   81.74
  6206.8   82.59  6268.5   82.68
BR D #Mann= 3
 3798.80     0.1 4967.48    0.04 5032.52     0.1
BR D Banks=4967.48,5032.52

Type RM Length L Ch R = 1 ,2502.7,657.7,657.7,657.7
BEGIN DESCRIPTION:
Downstream Section of Bridge/Culvert/Weir
END DESCRIPTION:
#Sta/Elev= 30
  3798.8   96.74  3868.8   89.69  3938.8   84.53  3978.8    78.5  4008.8    76.5
  4108.8   74.62  4168.8   71.75  4258.8   73.96  4318.8    73.7  4378.8   70.51
  4446.6   69.64  4566.6   71.02  4716.6   68.87  4836.6   69.92 4967.48   67.31
 4969.88   63.31 5030.12   63.31 5032.52   67.31  5110.7   70.74  5260.7   68.68
  5290.7   70.87  5340.7   68.74  5366.6   69.78  5466.6   68.75  5586.6   71.58
  5666.6   70.34  5796.8   71.72  5946.8   77.54  6136.8   82.09  6268.5   82.69
#Mann= 3 , 1 , 0
 3798.80     0.1       0 4967.48    0.04       0 5032.52     0.1       0
#XS Ineff= 2 , 0
       0    4962    72.7    5038       0    72.7
Bank Sta=4967.48,5032.52
Exp/Cntr=0.5,0.3

Type RM Length L Ch R = 1 ,1845.0,0,0,0
BEGIN DESCRIPTION:
White Oak Swamp DS 1.0
END DESCRIPTION:
#Sta/Elev= 30
  4248.5   79.43  4328.5   77.11  4398.5    71.8  4468.5    70.2  4578.5   68.76
  4848.5   69.49  4878.5   67.83  4918.5   67.82 4959.35   65.84 4962.35   62.84
 5037.65   62.84 5040.65   65.84    5115   66.28    5145   67.74    5155   69.58
    5175   69.87    5205   68.07    5365   71.74    5395   71.63    5435   73.19
    5515   72.16    5575   72.77    5665   71.09    5715   71.22    5725   72.21
    5905   72.66    5995   76.49    6045    77.1    6115   80.04  6193.5   81.18
#Mann= 3 , 1 , 0
 4248.50     0.1       0 4959.35    0.04       0 5040.65     0.1       0
Bank Sta=4959.35,5040.65
Exp/Cntr=0.3,0.1

Chan Stop Cuts=-1