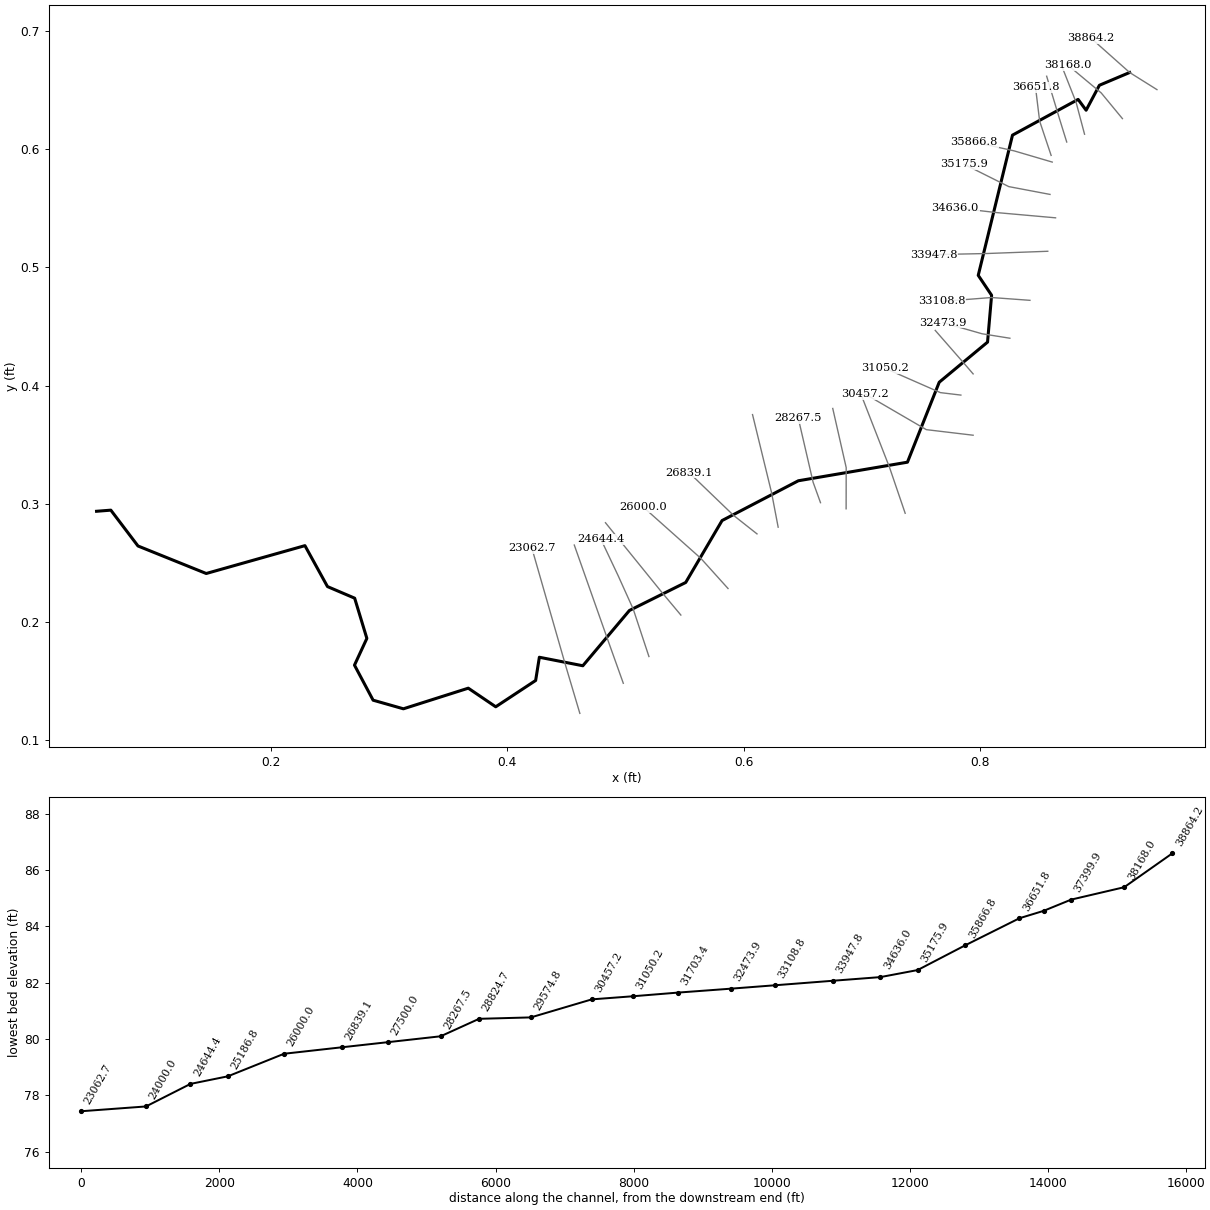
--- White_Oak_Swamp_US_021220.prj (project) ---

Proj Title=White Oak Swamp US - Wilson County
Current Plan=p01
Default Exp/Contr=0.3,0.1
English Units
Geom File=g01
Flow File=f02
Flow File=f01
Plan File=p02
Plan File=p01
Y Axis Title=Elevation
X Axis Title(PF)=Main Channel Distance
X Axis Title(XS)=Station
BEGIN DESCRIPTION:
NEUSE RIVER BASIN
Little Contentnea Creek Sub-basin
WHITE OAK SWAMP
(Flood Hazard, Floodway) Model
Prepared by: Andrew J. Bonner   Date: 11/26/2002
Watershed Concepts
3333 Regency Pkwy
Cary, North Carolina 27511
END DESCRIPTION:
DSS Export Rating Curves= 0
DSS Export Rating Curve Sorted= 0
DSS Export Volume Flow Curves= 0
DXF OffsetX= 0
DXF OffsetY= 0
DXF ScaleX= 1
DXF ScaleY= 10

--- White_Oak_Swamp_US_021220.p01 (plan) ---

Plan Title=100 Year Single
Program Version=4.00
Short Identifier=100 Year Sin
Geom File=g01
Flow File=f01
Subcritical Flow
K Sum by GR= 0
Std Step Tol= 0.01
Critical Tol= 0.01
Num of Std Step Trials= 20
Max Error Tol= 0.3
Flow Tol Ratio= 0.001
Split Flow NTrial= 30
Split Flow Tol= 0.02
Split Flow Ratio= 0.02
Log Output Level= 0
Friction Slope Method= 1
Unsteady Friction Slope Method= 2
Unsteady Bridges Friction Slope Method= 1
Parabolic Critical Depth
Global Vel Dist= 0 , 0 , 0
Global Log Level= 0
CheckData=True
Encroach Param=-1 ,10,10, 2
Encroach River=White Oak US
Encroach Reach=Reach - 1
Encroach Node=38864.2
       4      .7
Encroach Node=38168.0
       4      .7
Encroach Node=37399.9
       4      .7
Encroach Node=37000.0
       4      .7
Encroach Node=36651.8
       4      .7
Encroach Node=35866.8
       4      .7
Encroach Node=35175.9
       4      .7
Encroach Node=34636.0
       4      .7
Encroach Node=33947.8
       4      .7
Encroach Node=33108.8
       4      .7
Encroach Node=32473.9
       4      .7
Encroach Node=31703.4
       4      .7
Encroach Node=31050.2
       4      .7
Encroach Node=30457.2
       4      .7
Encroach Node=29574.8
       4      .7
Encroach Node=28824.7
       4      .7
Encroach Node=28267.5
       4      .7
Encroach Node=27500.0
       4      .7
Encroach Node=26839.1
       4      .7
Encroach Node=26000.0
       4      .7
Encroach Node=25186.8
       4      .7
Encroach Node=24644.4
       4      .7
Encroach Node=24000.0
       4      .7
Encroach Node=23062.7
       4      .7
Encroach Node=22519.0
       1    4800    5230
Encroach Node=22473.0
       1    4800    5230
Encroach Node=21946.4
       4      .7
Encroach Node=21147.0
       4      .7
Encroach Node=20620.0
       4      .7
Encroach Node=19597.5
       4      .7
Encroach Node=18689.8
       4      .7
Encroach Node=17727.1
       4      .7
Encroach Node=16772.2
       4      .7
Encroach Node=15459.6
       4      .7
Encroach Node=14863.3
       4      .7
Encroach Node=13990.9
       4      .7
Encroach Node=13307.4
       4      .7
Encroach Node=12380.5
       1 4705.38 5255.38
Computation Interval=1HOUR
Output Interval=1HOUR
Run HTab= 0
Run UNet= 0
Run PostProcess= 0
Run WQNet= 0
UNET Theta= 1
UNET Theta Warmup= 1
UNET ZTol= 0.02
UNET ZSATol= 0.1
UNET MxIter= 20
UNET MaxInSteps= 20
UNET DtIC= 0
UNET DtMin= 0
UNET MaxCRTS= 20
UNET WFStab= 2
UNET SFStab= 1
UNET WFX= 1
UNET SFX= 1
UNET DSS MLevel= 4
UNET DZMax Abort= 100
UNET Convert EG Bridges=-1
UNET Use Existing IB Tables=-1
UNET Froude Reduction=False
UNET Froude Limit= 1
UNET Froude Power= 10
UNET Time Slicing=0,0, 5
Instantaneous Interval=1HOUR
DSS File=dss
Write IC File= 0
Echo Input=False
Echo Output=False
Write Detailed= 0
Detailed Automatic Start=False, 10
WQ ULTIMATE=-1
WQ Max Comp Step=1HOUR
WQ Output Interval=15MIN
WQ Output Selected Increments= 0
WQ Output face flow=0
WQ Output face velocity=0
WQ Output face area=0
WQ Output face dispersion=0
WQ Output cell volume=0
WQ Output cell surface area=0
WQ Output cell continuity=0
WQ Output face conc=0
WQ Output face dconc_dx=0
WQ Output face courant=0
WQ Output face peclet=0
WQ Output face adv mass=0
WQ Output face disp mass=0
WQ Output cell mass=0
WQ Output cell source sink temp=0
WQ Output cell source sink nsm=0
WQ Output MaxMinRange=-1
WQ Daily Max Min Mean=-1
WQ Daily Range=0
WQ Daily Time=0
WQ Create Restart=0
WQ Fixed Restart=0
WQ System Summary=False
Sorting and Armoring Iterations= 10
XS Update Threshold= 0.02
Hydraulics Update Threshold= 0.02
Energy Slope Method= 1
Volume Change Method= 0
XS Weighting Method= 0
Number of US Weighted Cross Sections= 1
Number of DS Weighted Cross Sections= 1
Upstream XS Weight=0.25
Main XS Weight=0.5
Downstream XS Weight=0.25
Number of DS XS's Weighted with US Boundary= 1
Upstream Boundary Weight= 1
Weight of XSs Associated with US Boundary= 0
Number of US XS's Weighted with DS Boundary= 1
Downstream Boundary Weight= 0.5
Weight of XSs Associated with DS Boundary= 0.5
Sediment Output Level= 4
Mass or Volume Output= 0
Output Increment Type= 1
Profile and TS Output Increment= 10
XS Output Flag= 0
XS Output Increment= 10
Disregard all LS=0
Disregard all Conn=0
Disregard all Breaches=0
Disregard all Pumps=0

--- White_Oak_Swamp_US_021220.p02 (plan) ---

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Plan Title=Multi_Profile
Short Identifier=Multi_Profile
Geom File=g01
Flow File=f02
Encroach Param=-1 ,0,0, 0
UNET ZSATol= 0.05
UNET MaxInSteps= 0
UNET Convert EG Bridges= 0

--- White_Oak_Swamp_US_021220.f01 (steady flow) ---

Flow Title= 100 Year Single
Program Version=4.00
Number of Profiles= 2
Profile Names=100-Year,AFW
River Rch & RM=White Oak US,Reach - 1       ,38864.2
    2262    2262
River Rch & RM=White Oak US,Reach - 1       ,35866.8
    3073    3073
River Rch & RM=White Oak US,Reach - 1       ,28824.7
    4105    4105
River Rch & RM=White Oak US,Reach - 1       ,24000
    4574    4574
River Rch & RM=White Oak US,Reach - 1       ,18689.8
    4863    4863
River Rch & RM=White Oak US,Reach - 1       ,15459.6
    5550    5550
River Rch & RM=White Oak US,Reach - 1       ,12380.5
    5550    5550
Boundary for River Rch & Prof#=White Oak US,Reach - 1       , 1
Up Type= 0
Dn Type= 1
Dn Known WS=82.4
Boundary for River Rch & Prof#=White Oak US,Reach - 1       , 2
Up Type= 0
Dn Type= 1
Dn Known WS=83.12
DSS Import GetInterval= 0
DSS Import GetPeak= 0
DSS Import FillOption= 0

--- White_Oak_Swamp_US_021220.f02 (steady flow) ---

Flow Title=Multi_Profile
Program Version=4.00
Number of Profiles= 7
Profile Names=10yr,25yr,50yr,500yr,100yr-10%,100yr-20%,100yr-35%
River Rch & RM=White Oak US,Reach - 1       ,38864.2
    1083    1497    1860    3399    2446    3135    3831
River Rch & RM=White Oak US,Reach - 1       ,35866.8
    1498    2055    2540    4573    3272    4194    5124
River Rch & RM=White Oak US,Reach - 1       ,28824.7
    2036    2770    3409    6053    4307    5519    6744
River Rch & RM=White Oak US,Reach - 1       ,24000.0
    2283    3097    3805    6720    4772    6115    7472
River Rch & RM=White Oak US,Reach - 1       ,18689.8
    2436    3299    4049    7131    5057    6481    7919
River Rch & RM=White Oak US,Reach - 1       ,15459.6
    2802    3781    4631    8103    5732    7347    8977
Boundary for River Rch & Prof#=White Oak US,Reach - 1       , 1
Up Type= 0
Dn Type= 1
Dn Known WS=79.65
Boundary for River Rch & Prof#=White Oak US,Reach - 1       , 2
Up Type= 0
Dn Type= 1
Dn Known WS=80.75
Boundary for River Rch & Prof#=White Oak US,Reach - 1       , 3
Up Type= 0
Dn Type= 1
Dn Known WS=81.57
Boundary for River Rch & Prof#=White Oak US,Reach - 1       , 4
Up Type= 0
Dn Type= 1
Dn Known WS=83.51
Boundary for River Rch & Prof#=White Oak US,Reach - 1       , 5
Up Type= 0
Dn Type= 1
Dn Known WS=82.54
Boundary for River Rch & Prof#=White Oak US,Reach - 1       , 6
Up Type= 0
Dn Type= 1
Dn Known WS=83.43
Boundary for River Rch & Prof#=White Oak US,Reach - 1       , 7
Up Type= 0
Dn Type= 1
Dn Known WS=83.34
DSS Import GetInterval= 0
DSS Import GetPeak= 0
DSS Import FillOption= 0

--- White_Oak_Swamp_US_021220.g01 (geometry) ---

Geom Title=Geom 01 by CodeH2 for Windows
Program Version=4.00

River Reach=White Oak US    ,Reach - 1
Reach XY= 30
       0.9268516       0.6648419       0.9012524       0.6540357
       0.8900229       0.6329288       0.8832645       0.6420784
       0.8276949       0.6118495       0.7986913       0.4932364
       0.8100077       0.4763874       0.8065709       0.4367375
       0.7656641       0.4027882       0.7387562       0.3351414
       0.6463855        0.319429       0.5818137        0.285768
       0.5510338       0.2333767        0.503358       0.2096701
       0.4639336       0.1629111        0.427129       0.1701148
       0.4239859       0.1504681       0.3901934       0.1282017
       0.3669543       0.1439458       0.3120185       0.1264983
       0.2863764       0.1337836       0.2706076       0.1634351
       0.2810947       0.1860697       0.2707586       0.2200966
       0.2477468       0.2299047       0.2286581        0.264536
        0.145094       0.2409698       0.0873217         0.26425
       0.0643269       0.2945611       0.0522485       0.2936169

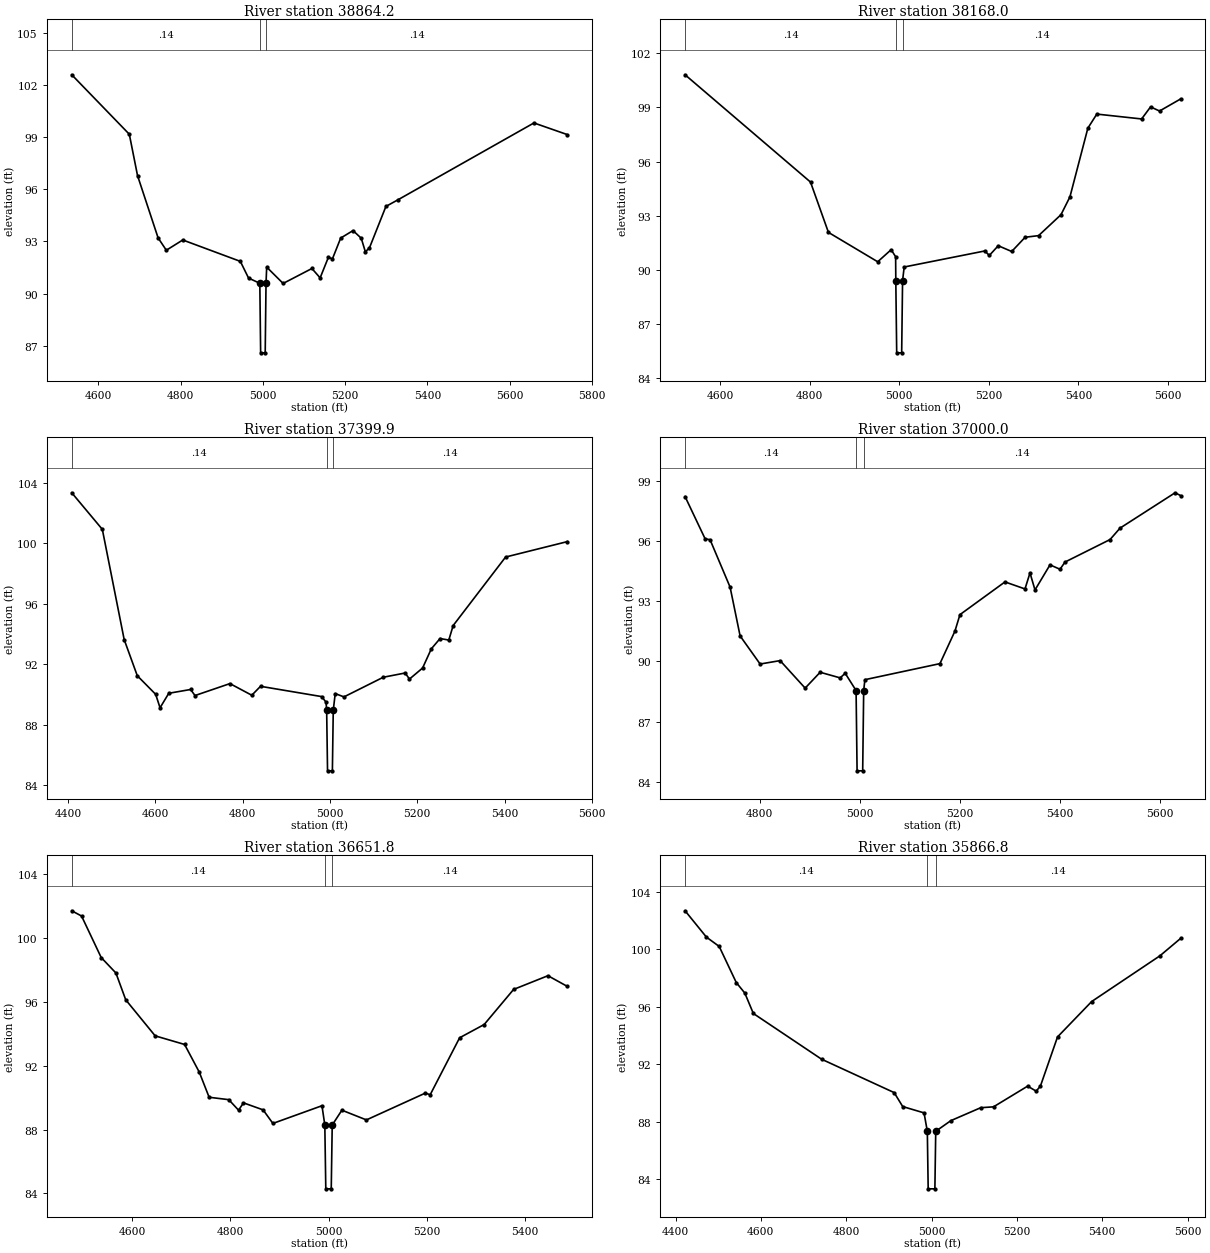
Type RM Length L Ch R = 1 ,38864.2 ,696.2,696.2,696.2
BEGIN DESCRIPTION:
White Oak Swamp US 42.0
END DESCRIPTION:
XS GIS Cut Line= 3
            0.95       0.6503613       0.9268956       0.6648294
       0.8943499       0.6937496
#Sta/Elev= 27
  4535.1  102.58  4675.1   99.16  4695.1   96.78  4745.1    93.2  4765.1   92.49
  4805.1   93.08  4945.1   91.85  4965.1   90.89  4992.5   90.59  4994.5   86.59
  5005.6   86.59  5007.6   90.59  5009.2   91.52  5049.2   90.58  5119.2   91.44
  5139.2    90.9  5159.2   92.08  5169.2      92  5189.2   93.19  5219.2   93.62
  5239.2   93.18  5249.2    92.4  5259.2   92.63  5299.2   95.01  5329.2    95.4
  5659.2   99.81  5740.4   99.14
#Mann= 3 , 1 , 0
  4535.1     .14       0  4992.5    .047       0  5007.6     .14       0
Bank Sta=4992.5,5007.6
XS Rating Curve= 0 ,0
Exp/Cntr=0.3,0.1

Type RM Length L Ch R = 1 ,38168.0 ,768.1,768.1,768.1
BEGIN DESCRIPTION:
White Oak Swamp US 41.0
END DESCRIPTION:
XS GIS Cut Line= 3
       0.9207601       0.6258375       0.9028389       0.6475317
       0.8745422       0.6711122
#Sta/Elev= 25
  4522.1  100.81  4802.1   94.86  4842.1   92.07  4952.1   90.44  4982.1   91.11
  4992.1   90.72  4992.5   89.39  4994.5   85.39  5005.6   85.39  5007.6   89.39
  5011.2   90.15  5191.2   91.04  5201.2   90.79  5221.2   91.33  5251.2   91.01
  5281.2    91.8  5311.2   91.89  5361.2   93.05  5381.2   94.04  5421.2   97.85
  5441.2   98.63  5541.2   98.36  5561.2   99.03  5581.2    98.8  5628.3   99.47
#Mann= 3 , 1 , 0
  4522.1     .14       0  4992.5    .047       0  5007.6     .14       0
Bank Sta=4992.5,5007.6
XS Rating Curve= 0 ,0
Exp/Cntr=0.3,0.1

Type RM Length L Ch R = 1 ,37399.9 ,399.9,399.9,399.9
BEGIN DESCRIPTION:
White Oak Swamp US 40.0
END DESCRIPTION:
XS GIS Cut Line= 3
       0.8886905       0.6126324       0.8815215        0.639661
       0.8698261       0.6692258
#Sta/Elev= 30
    4409  103.34    4479  100.92    4529   93.63    4559   91.24  4601.1   90.01
  4611.1   89.12  4631.1   90.08  4681.1   90.33  4691.1   89.93  4771.1   90.72
  4821.1   89.95  4841.1   90.54  4981.1   89.86  4991.1   89.49  4992.5   88.95
  4994.5   84.95  5005.6   84.95  5007.6   88.95  5012.1   90.06  5032.1   89.84
  5122.1   91.14  5172.1   91.42  5182.1   91.02  5212.1   91.75  5232.1   93.02
  5252.1    93.7  5272.1    93.6  5282.1   94.56  5402.1   99.09  5543.4  100.11
#Mann= 3 , 1 , 0
    4409     .14       0  4992.5    .047       0  5007.6     .14       0
Bank Sta=4992.5,5007.6
XS Rating Curve= 0 ,0
Exp/Cntr=0.3,0.1

Type RM Length L Ch R = 1 ,37000.0 ,348.2,348.2,348.2
BEGIN DESCRIPTION:
White Oak Swamp US 39.0
END DESCRIPTION:
XS GIS Cut Line= 3
        0.873599       0.6060298       0.8675043       0.6256264
       0.8566209         0.66168
#Sta/Elev= 30
  4650.6   98.21  4690.6   96.11  4700.6   96.06  4740.6    93.7  4760.6   91.27
  4800.6   89.87  4840.6   90.04  4890.6   88.67  4920.6   89.46  4960.6   89.18
  4970.6   89.41  4992.4   88.55  4994.4   84.55  5005.6   84.55  5007.6   88.55
    5010   89.09    5160   89.89    5190   91.51    5200   92.33    5290   93.96
    5330   93.61    5340   94.41    5350   93.56    5380   94.81    5400   94.59
    5410   94.95    5500   96.07    5520   96.64    5630    98.4  5641.1   98.26
#Mann= 3 , 1 , 0
  4650.6     .14       0  4992.4    .047       0  5007.6     .14       0
Bank Sta=4992.4,5007.6
XS Rating Curve= 0 ,0
Exp/Cntr=0.3,0.1

Type RM Length L Ch R = 1 ,36651.8 ,785,785,785
BEGIN DESCRIPTION:
White Oak Swamp US 38.0
END DESCRIPTION:
XS GIS Cut Line= 3
       0.8603938       0.5947112       0.8506814       0.6237091
       0.8471887       0.6522478
#Sta/Elev= 28
  4476.6  101.72  4496.6  101.39  4536.6   98.79  4566.6   97.82  4586.6   96.14
  4646.6   93.88  4706.6   93.34  4736.6    91.6  4756.6   90.03  4796.6   89.88
  4816.6   89.22  4826.6   89.68  4866.6   89.24  4886.6   88.39  4986.6    89.5
  4992.4   88.29  4994.4   84.29  5005.5   84.29  5007.5   88.29  5027.2   89.22
  5077.2   88.61  5197.2   90.29  5207.2   90.19  5267.2   93.76  5317.2   94.59
  5377.2   96.79  5447.2   97.65  5486.7   96.98
#Mann= 3 , 1 , 0
  4476.6     .14       0  4992.4    .047       0  5007.5     .14       0
Bank Sta=4992.4,5007.5
XS Rating Curve= 0 ,0
Exp/Cntr=0.3,0.1

Type RM Length L Ch R = 1 ,35866.8 ,690.9,690.9,690.9
BEGIN DESCRIPTION:
White Oak Swamp US 37.0
END DESCRIPTION:
XS GIS Cut Line= 3
       0.8613371       0.5890518       0.8290578       0.5985407
       0.7953115       0.6060298
#Sta/Elev= 24
  4422.4  102.66  4472.4  100.83  4502.4  100.18  4542.4   97.67  4562.4   96.94
  4582.4   95.52  4742.4   92.34  4912.4   90.02  4932.4   89.05  4982.4   88.61
  4990.1   87.33  4992.1   83.33  5007.8   83.33  5009.8   87.33  5045.2   88.07
  5115.2   88.97  5145.2   89.03  5225.2   90.47  5245.2   90.12  5255.2   90.48
  5295.2   93.89  5375.2   96.35  5535.2   99.53  5583.7  100.74
#Mann= 3 , 1 , 0
  4422.4     .14       0  4990.1    .047       0  5009.8     .14       0
Bank Sta=4990.1,5009.8
XS Rating Curve= 0 ,0
Exp/Cntr=0.3,0.1

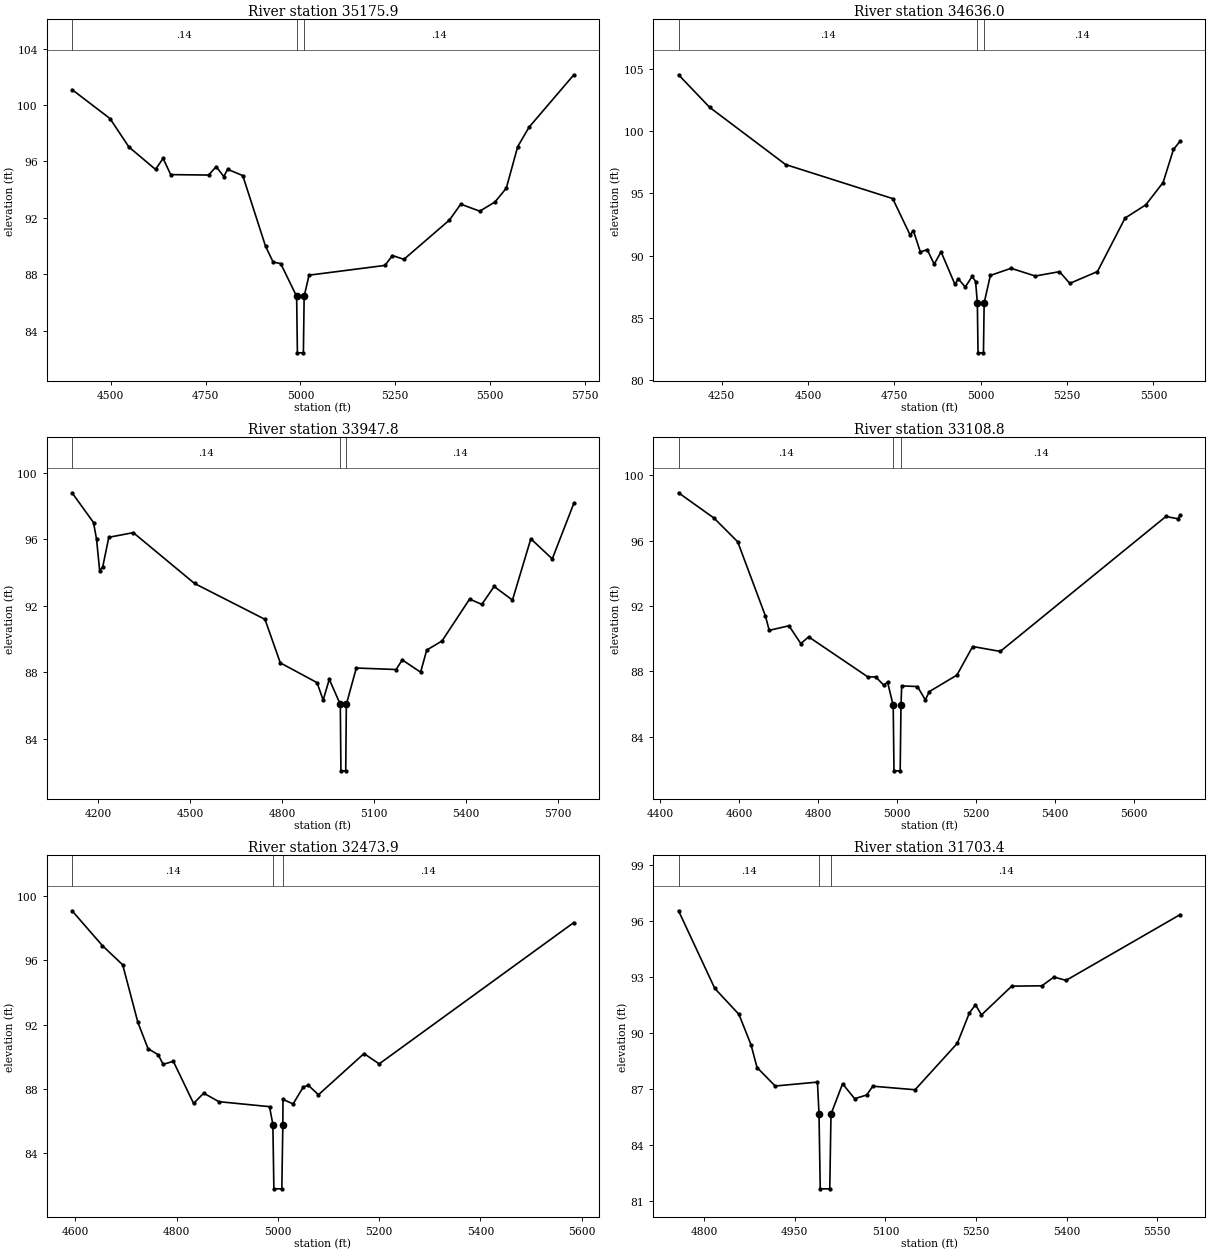
Type RM Length L Ch R = 1 ,35175.9 ,539.9,539.9,539.9
BEGIN DESCRIPTION:
White Oak Swamp US 36.0
END DESCRIPTION:
XS GIS Cut Line= 3
       0.8594506       0.5616984       0.8245514       0.5683009
       0.7868225       0.5871654
#Sta/Elev= 30
  4398.1  101.09  4498.1   99.04  4548.1   97.02  4618.1   95.44  4638.1   96.22
  4658.1   95.07  4758.1   95.04  4778.1   95.64  4798.1   94.93  4808.1   95.45
  4848.1      95  4908.1      90  4928.1   88.88  4948.1   88.77  4990.1   86.45
  4992.1   82.45  5007.9   82.45  5009.9   86.45  5022.8   87.95  5222.8   88.64
  5242.8   89.34  5272.8   89.07  5392.8   91.85  5422.8   92.98  5472.8   92.48
  5512.8   93.13  5542.8   94.11  5572.8   97.05  5602.8   98.43  5720.9  102.14
#Mann= 3 , 1 , 0
  4398.1     .14       0  4990.1    .047       0  5009.9     .14       0
Bank Sta=4990.1,5009.9
XS Rating Curve= 0 ,0
Exp/Cntr=0.3,0.1

Type RM Length L Ch R = 1 ,34636.0 ,688.2,688.2,688.2
BEGIN DESCRIPTION:
White Oak Swamp US 35.0
END DESCRIPTION:
XS GIS Cut Line= 3
       0.8641667       0.5418907        0.813106       0.5464314
       0.7792767       0.5503797
#Sta/Elev= 30
  4125.1   104.5  4215.1  101.89  4435.1    97.3  4745.1   94.57  4795.1   91.67
  4805.1   91.99  4825.1   90.29  4845.1   90.48  4865.1   89.31  4885.1    90.3
  4925.1    87.7  4935.1   88.13  4955.1   87.48  4975.1   88.33  4985.1   87.92
  4990.1    86.2  4992.1    82.2  5007.8    82.2  5009.8    86.2  5027.8   88.41
  5087.8   88.98  5157.8   88.36  5227.8   88.71  5257.8   87.77  5337.8   88.72
  5417.8   93.01  5477.8   94.07  5527.8   95.86  5557.8   98.51  5577.7    99.2
#Mann= 3 , 1 , 0
  4125.1     .14       0  4990.1    .047       0  5009.8     .14       0
Bank Sta=4990.1,5009.8
XS Rating Curve= 0 ,0
Exp/Cntr=0.3,0.1

Type RM Length L Ch R = 1 ,33947.8 ,839,839,839
BEGIN DESCRIPTION:
White Oak Swamp US 34.0
END DESCRIPTION:
XS GIS Cut Line= 3
       0.8575642        0.513594       0.8060163       0.5116919
       0.7613554       0.5107643
#Sta/Elev= 30
  4114.1   98.81  4184.1   97.02  4194.1   96.01  4204.1   94.13  4214.1   94.34
  4234.1   96.13  4314.1   96.41  4514.1   93.35  4744.1   91.19  4794.1   88.57
  4914.1   87.38  4934.1   86.33  4954.1   87.58  4990.1   86.07  4992.1   82.07
  5007.8   82.07  5009.8   86.07  5042.3   88.26  5172.3   88.17  5192.3   88.75
  5252.3   88.01  5272.3   89.34  5322.3   89.89  5412.3   92.41  5452.3   92.09
  5492.3   93.17  5552.3   92.35  5612.3   96.04  5682.3   94.83  5752.8   98.18
#Mann= 3 , 1 , 0
  4114.1     .14       0  4990.1    .047       0  5009.8     .14       0
Bank Sta=4990.1,5009.8
XS Rating Curve= 0 ,0
Exp/Cntr=0.3,0.1

Type RM Length L Ch R = 1 ,33108.8 ,634.9,634.9,634.9
BEGIN DESCRIPTION:
White Oak Swamp US 33.0
END DESCRIPTION:
XS GIS Cut Line= 3
       0.8424726       0.4720922       0.8099156        0.474471
        0.767958        0.471149
#Sta/Elev= 26
  4445.8   98.93  4535.8   97.38  4595.8   95.93  4665.8   91.41  4675.8   90.51
  4725.8   90.79  4755.8    89.7  4775.8   90.11  4925.8   87.66  4945.8   87.66
  4965.8   87.16  4975.8   87.34  4990.1   85.91  4992.1   81.91  5007.8   81.91
  5009.8   85.91  5011.6   87.11  5051.6   87.07  5071.6   86.25  5081.6   86.76
  5151.6   87.77  5191.6   89.52  5261.6   89.22  5681.6   97.48  5711.6   97.34
  5718.1   97.55
#Mann= 3 , 1 , 0
  4445.8     .14       0  4990.1    .047       0  5009.8     .14       0
Bank Sta=4990.1,5009.8
XS Rating Curve= 0 ,0
Exp/Cntr=0.3,0.1

Type RM Length L Ch R = 1 ,32473.9 ,770.5,770.5,770.5
BEGIN DESCRIPTION:
White Oak Swamp US 32.0
END DESCRIPTION:
XS GIS Cut Line= 3
       0.8254946       0.4400226        0.801914       0.4437955
       0.7689012       0.4532278
#Sta/Elev= 24
  4593.6   99.08  4653.6   96.91  4693.6   95.72  4723.6   92.14  4743.6   90.51
  4763.6   90.13  4773.6   89.53  4793.6   89.72  4833.6    87.1  4853.6   87.74
  4883.6   87.21  4983.6    86.9  4990.2   85.79  4992.2   81.79  5007.9   81.79
  5009.9   85.79  5010.2   87.35  5030.2   87.07  5050.2   88.12  5060.2   88.23
  5080.2   87.64  5170.2    90.2  5200.2   89.56  5584.7   98.35
#Mann= 3 , 1 , 0
  4593.6     .14       0  4990.2    .047       0  5009.9     .14       0
Bank Sta=4990.2,5009.9
XS Rating Curve= 0 ,0
Exp/Cntr=0.3,0.1

Type RM Length L Ch R = 1 ,31703.4 ,653.2,653.2,653.2
BEGIN DESCRIPTION:
White Oak Swamp US 31.0
END DESCRIPTION:
XS GIS Cut Line= 3
       0.7943682       0.4098395       0.7851017       0.4205893
       0.7622987       0.4466252
#Sta/Elev= 25
  4757.5   96.55  4817.5   92.39  4857.5      91  4877.5   89.37  4887.5   88.15
  4917.5   87.16  4987.5   87.37  4990.1   85.65  4992.1   81.65  5007.9   81.65
  5009.9   85.65  5029.1   87.28  5049.1   86.48  5069.1   86.68  5079.1   87.15
  5149.1   86.96  5219.1   89.45  5239.1   91.08  5249.1   91.51  5259.1   90.97
  5309.1   92.51  5359.1   92.53  5379.1      93  5399.1   92.82  5588.3   96.35
#Mann= 3 , 1 , 0
  4757.5     .14       0  4990.1    .047       0  5009.9     .14       0
Bank Sta=4990.1,5009.9
XS Rating Curve= 0 ,0
Exp/Cntr=0.3,0.1

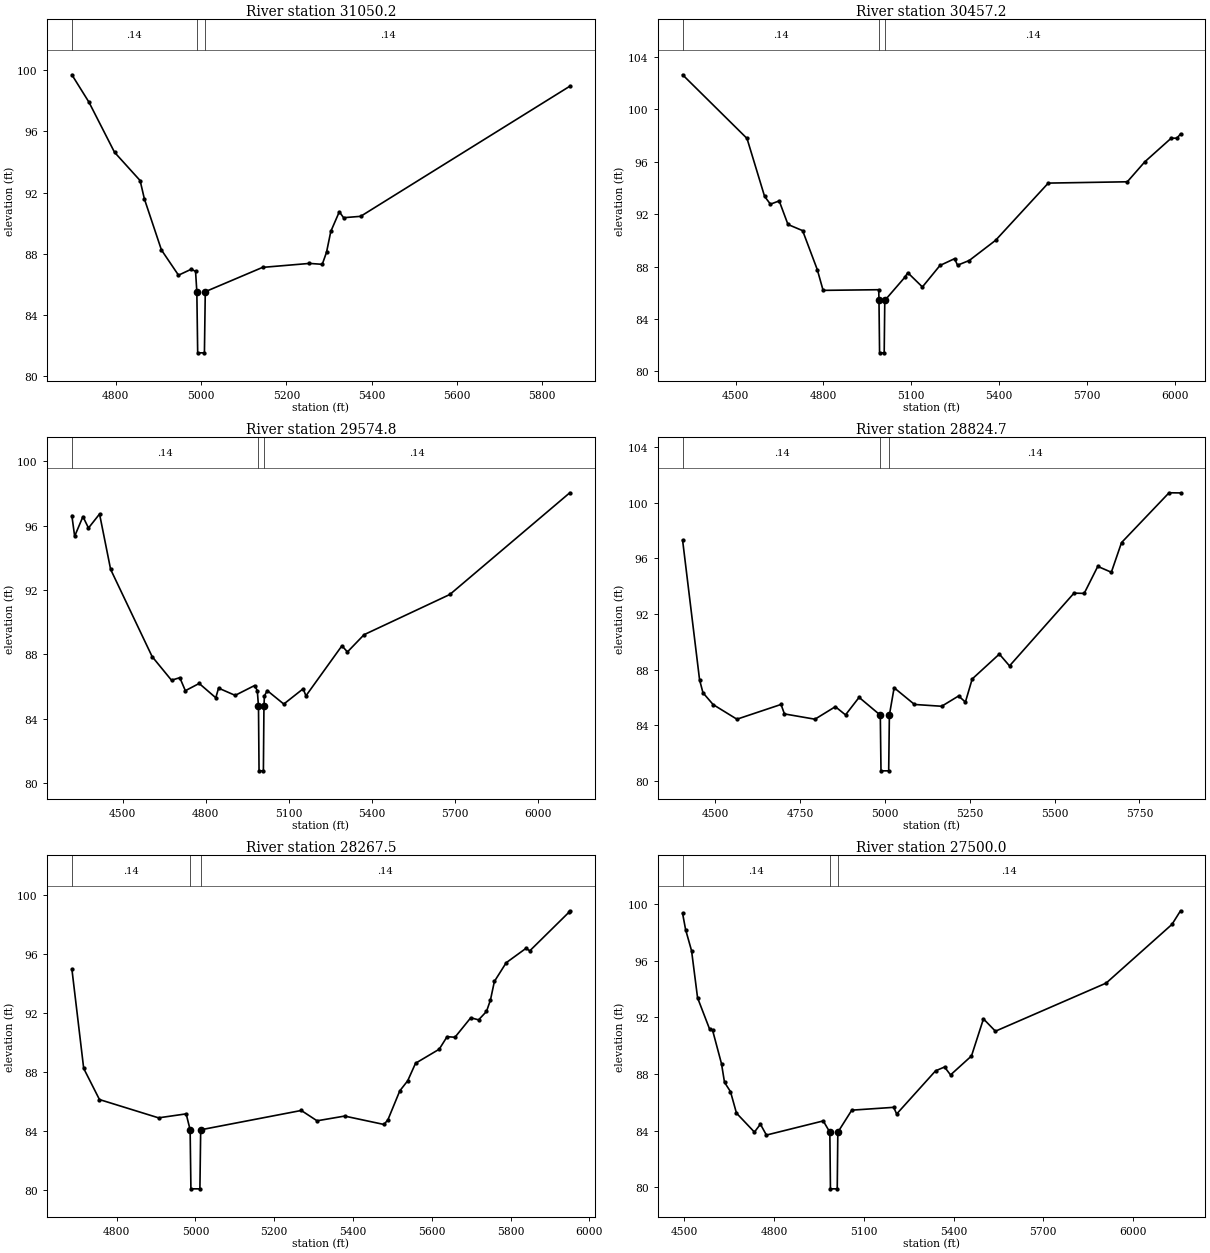
Type RM Length L Ch R = 1 ,31050.2 ,593,593,593
BEGIN DESCRIPTION:
White Oak Swamp US 30.0
END DESCRIPTION:
XS GIS Cut Line= 3
       0.7839928       0.3919183       0.7666685        0.394003
       0.7198536       0.4145556
#Sta/Elev= 22
  4697.1   99.71  4737.1   97.92  4797.1   94.64  4857.1   92.79  4867.1   91.59
  4907.1   88.25  4947.1    86.6  4977.1   86.99  4987.1   86.85  4990.1   85.52
  4992.1   81.52  5007.9   81.52  5009.9   85.52  5144.2   87.11  5254.2   87.37
  5284.2   87.31  5294.2    88.1  5304.2   89.46  5324.2   90.75  5334.2   90.36
  5374.2   90.45  5864.6   98.96
#Mann= 3 , 1 , 0
  4697.1     .14       0  4990.1    .047       0  5009.9     .14       0
Bank Sta=4990.1,5009.9
XS Rating Curve= 0 ,0
Exp/Cntr=0.3,0.1

Type RM Length L Ch R = 1 ,30457.2 ,882.4,882.4,882.4
BEGIN DESCRIPTION:
White Oak Swamp US 29.0
END DESCRIPTION:
XS GIS Cut Line= 3
       0.7943682       0.3579622       0.7547529       0.3626784
       0.7028756       0.3928615
#Sta/Elev= 28
  4319.2  102.64  4539.2   97.78  4599.2   93.36  4619.2   92.76  4649.2   93.01
  4679.2   91.21  4729.2   90.74  4779.2   87.77  4799.2   86.18  4989.2   86.23
  4990.1   85.41  4992.1   81.41  5007.9   81.41  5009.9   85.41  5078.4   87.18
  5088.4   87.53  5138.4   86.44  5198.4   88.08  5248.4    88.6  5258.4    88.1
  5298.4   88.46  5388.4      90  5568.4   94.37  5838.4   94.47  5898.4      96
  5988.4    97.8  6008.4    97.8  6020.2   98.13
#Mann= 3 , 1 , 0
  4319.2     .14       0  4990.1    .047       0  5009.9     .14       0
Bank Sta=4990.1,5009.9
XS Rating Curve= 0 ,0
Exp/Cntr=0.3,0.1

Type RM Length L Ch R = 1 ,29574.8 ,750.1,750.1,750.1
BEGIN DESCRIPTION:
White Oak Swamp US 28.0
END DESCRIPTION:
XS GIS Cut Line= 3
       0.7368316       0.2919367       0.7236265       0.3306088
        0.700046        0.390975
#Sta/Elev= 30
  4315.9   96.63  4325.9   95.35  4355.9   96.57  4375.9   95.86  4415.9   96.73
  4455.9   93.29  4605.9   87.87  4675.9    86.4  4705.9   86.56  4725.9   85.75
  4775.9    86.2  4835.9   85.31  4845.9   85.91  4905.9   85.46  4975.9   86.07
  4985.9   85.76  4990.2   84.77  4992.2   80.77  5007.9   80.77  5009.9   84.77
  5011.6   85.42  5021.6   85.76  5081.6   84.92  5151.6   85.87  5161.6   85.43
  5291.6   88.54  5311.6   88.16  5371.6   89.23  5681.6   91.73    6115   98.05
#Mann= 3 , 1 , 0
  4315.9     .14       0  4990.2    .047       0  5009.9     .14       0
Bank Sta=4990.2,5009.9
XS Rating Curve= 0 ,0
Exp/Cntr=0.3,0.1

Type RM Length L Ch R = 1 ,28824.7 ,557.2,557.2,557.2
BEGIN DESCRIPTION:
White Oak Swamp US 27.0
END DESCRIPTION:
XS GIS Cut Line= 3
       0.6868408       0.2957095       0.6869094       0.3305502
       0.6755222       0.3805996
#Sta/Elev= 30
  4404.2   97.29  4454.2   87.26  4464.2   86.33  4494.2   85.48  4564.2   84.43
  4694.2   85.49  4704.2   84.81  4794.2   84.43  4854.2   85.33  4884.2   84.74
  4924.2      86  4986.7   84.72  4988.7   80.72  5011.4   80.72  5013.4   84.72
  5027.4   86.69  5087.4   85.49  5167.4   85.36  5217.4    86.1  5237.4   85.66
  5257.4   87.32  5337.4   89.11  5367.4   88.26  5557.4   93.49  5587.4   93.47
  5627.4   95.41  5667.4   94.99  5697.4   97.12  5837.4   100.7  5871.2  100.69
#Mann= 3 , 1 , 0
  4404.2     .14       0  4986.7    .047       0  5013.4     .14       0
Bank Sta=4986.7,5013.4
XS Rating Curve= 0 ,0
Exp/Cntr=0.3,0.1

Type RM Length L Ch R = 1 ,28267.5 ,767.5,767.5,767.5
BEGIN DESCRIPTION:
White Oak Swamp US 26.0
END DESCRIPTION:
XS GIS Cut Line= 3
       0.6651467       0.3008973       0.6589051       0.3181432
       0.6462823       0.3725822
#Sta/Elev= 30
  4686.5      95  4716.5   88.26  4756.5   86.15  4906.5   84.91  4976.5   85.18
  4986.6    84.1  4988.6    80.1  5011.4    80.1  5013.4    84.1  5268.7   85.41
  5308.7   84.71  5378.7   85.03  5478.7   84.46  5488.7   84.79  5518.7   86.74
  5538.7   87.42  5558.7   88.61  5618.7   89.56  5638.7   90.41  5658.7   90.37
  5698.7   91.69  5718.7   91.55  5738.7   92.12  5748.7   92.89  5758.7   94.15
  5788.7   95.42  5838.7   96.39  5848.7   96.23  5948.7   98.86  5950.1   98.94
#Mann= 3 , 1 , 0
  4686.5     .14       0  4986.6    .047       0  5013.4     .14       0
Bank Sta=4986.6,5013.4
XS Rating Curve= 0 ,0
Exp/Cntr=0.3,0.1

Type RM Length L Ch R = 1 ,27500.0 ,660.9,660.9,660.9
BEGIN DESCRIPTION:
White Oak Swamp US 25.0
END DESCRIPTION:
XS GIS Cut Line= 3
       0.6293042       0.2801464         0.62373       0.3093014
       0.6076101       0.3754119
#Sta/Elev= 30
  4494.7   99.35  4504.7   98.21  4524.7   96.71  4544.7   93.39  4584.7   91.19
  4594.7   91.11  4624.7   88.73  4634.7   87.42  4654.7   86.76  4674.7   85.24
  4734.7    83.9  4754.7   84.46  4774.7   83.69  4964.7   84.69  4986.7   83.89
  4988.7   79.89  5011.4   79.89  5013.4   83.89    5060   85.45    5200   85.65
    5210   85.18    5340   88.23    5370    88.5    5390   87.94    5460   89.28
    5500    91.9    5540   91.03    5910   94.43    6130   98.58  6158.5   99.54
#Mann= 3 , 1 , 0
  4494.7     .14       0  4986.7    .047       0  5013.4     .14       0
Bank Sta=4986.7,5013.4
XS Rating Curve= 0 ,0
Exp/Cntr=0.3,0.1

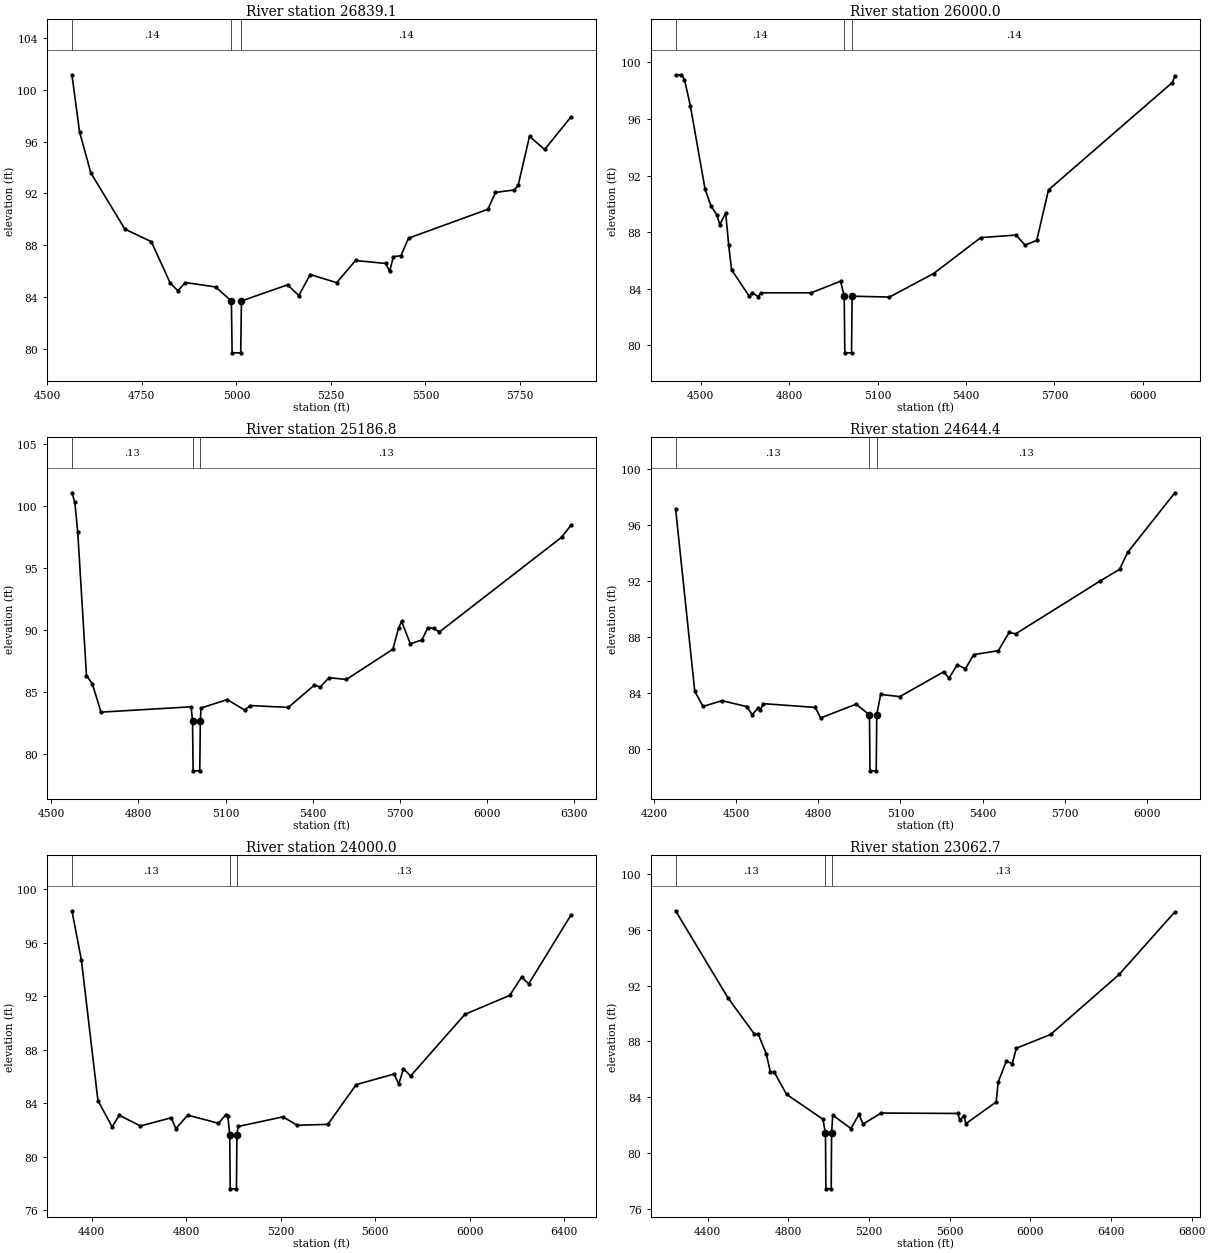
Type RM Length L Ch R = 1 ,26839.1 ,839.1,839.1,839.1
BEGIN DESCRIPTION:
White Oak Swamp US 24.0
END DESCRIPTION:
XS GIS Cut Line= 3
        0.611383        0.274487       0.5915529       0.2901389
       0.5538464       0.3263643
#Sta/Elev= 30
  4565.1  101.15  4585.1   96.77  4615.1   93.58  4705.1   89.25  4775.1   88.28
  4825.1   85.08  4845.1    84.5  4865.1   85.13  4945.1   84.79  4986.7   83.71
  4988.7   79.71  5011.4   79.71  5013.4   83.71  5135.2   84.95  5165.2   84.13
  5195.2   85.75  5265.2   85.12  5315.2   86.83  5395.2    86.6  5405.2   85.99
  5415.2   87.12  5435.2    87.2  5455.2   88.55  5665.2   90.78  5685.2   92.08
  5735.2   92.27  5745.2   92.63  5775.2    96.4  5815.2   95.39  5885.4   97.92
#Mann= 3 , 1 , 0
  4565.1     .14       0  4986.7    .047       0  5013.4     .14       0
Bank Sta=4986.7,5013.4
XS Rating Curve= 0 ,0
Exp/Cntr=0.3,0.1

Type RM Length L Ch R = 1 ,26000.0 ,813.2,813.2,813.2
BEGIN DESCRIPTION:
White Oak Swamp US 23.0
END DESCRIPTION:
XS GIS Cut Line= 3
       0.5868592       0.2282691       0.5638185       0.2538171
       0.5151743       0.2971244
#Sta/Elev= 30
  4414.3    99.1  4434.3   99.12  4444.3   98.78  4464.3   96.94  4514.3   91.04
  4534.3   89.86  4554.3   89.23  4564.3   88.53  4584.3   89.36  4594.3   87.11
  4604.3   85.35  4664.3   83.47  4674.3   83.74  4694.3   83.45  4704.3   83.72
  4874.3   83.72  4974.3   84.54  4986.6   83.48  4988.6   79.48  5011.4   79.48
  5013.4   83.48    5140   83.42    5290   85.08    5450   87.62    5570    87.8
    5600   87.09    5640   87.42    5680   90.99    6100   98.57  6108.8   99.01
#Mann= 3 , 1 , 0
  4414.3     .14       0  4986.6    .047       0  5013.4     .14       0
Bank Sta=4986.6,5013.4
XS Rating Curve= 0 ,0
Exp/Cntr=0.3,0.1

Type RM Length L Ch R = 1 ,25186.8 ,542.4,542.4,542.4
BEGIN DESCRIPTION:
White Oak Swamp US 22.0
END DESCRIPTION:
XS GIS Cut Line= 3
       0.5469228       0.2058142        0.530936       0.2249137
       0.4831047       0.2839193
#Sta/Elev= 30
  4571.8  101.04  4581.8  100.26  4591.8   97.86  4621.8   86.34  4641.8   85.68
  4671.8    83.4  4981.8   83.83  4986.6   82.68  4988.6   78.68  5011.4   78.68
  5013.4   82.68  5015.8   83.73  5105.8   84.41  5165.8   83.57  5185.8   83.93
  5315.8   83.78  5405.8   85.58  5425.8   85.42  5455.8   86.17  5515.8   86.03
  5675.8   88.46  5695.8    90.2  5705.8   90.69  5735.8   88.89  5775.8   89.21
  5795.8   90.19  5815.8   90.13  5835.8   89.85  6255.8   97.46    6289   98.45
#Mann= 3 , 1 , 0
  4571.8     .13       0  4986.6    .047       0  5013.4     .13       0
Bank Sta=4986.6,5013.4
XS Rating Curve= 0 ,0
Exp/Cntr=0.3,0.1

Type RM Length L Ch R = 1 ,24644.4 ,644.4,644.4,644.4
BEGIN DESCRIPTION:
White Oak Swamp US 21.0
END DESCRIPTION:
XS GIS Cut Line= 4
       0.5198904       0.1707325       0.5065988       0.2108547
       0.4939523       0.2388578       0.4793318       0.2697709
#Sta/Elev= 30
  4278.1   97.12  4348.1    84.1  4378.1   83.01  4448.1   83.42  4538.1      83
  4558.1   82.42  4578.1   82.87  4588.1   82.75  4598.1   83.21  4788.1   82.94
  4808.1   82.19  4938.1   83.17  4986.7   82.41  4988.7   78.41  5011.4   78.41
  5013.4   82.41  5027.7   83.87  5097.7   83.71  5257.7   85.48  5277.7   85.03
  5307.7   85.99  5337.7    85.7  5367.7   86.71  5457.7   86.99  5497.7   88.31
  5520.8   88.19  5830.8   91.98  5900.8    92.8  5930.8   94.02    6103   98.27
#Mann= 3 , 1 , 0
  4278.1     .13       0  4986.7    .047       0  5013.4     .13       0
Bank Sta=4986.7,5013.4
XS Rating Curve= 0 ,0
Exp/Cntr=0.3,0.1

Type RM Length L Ch R = 1 ,24000.0 ,937.3,937.3,937.3
BEGIN DESCRIPTION:
White Oak Swamp US 20.0
END DESCRIPTION:
XS GIS Cut Line= 3
       0.4981963       0.1480952       0.4846896        0.185876
       0.4566945       0.2650548
#Sta/Elev= 30
  4316.9   98.39  4356.9   94.71  4426.9   84.21  4486.9   82.24  4516.9   83.11
  4606.9   82.31  4736.9   82.92  4756.9   82.11  4806.9   83.12  4936.9   82.51
  4966.9   83.12  4976.9   83.02  4984.8   81.61  4986.8   77.61  5013.1   77.61
  5015.1   81.61    5020   82.27    5210   82.99    5270   82.36    5400   82.43
    5520    85.4    5680   86.19    5700   85.44    5720   86.59    5750   86.04
    5980   90.65    6170   92.07    6220   93.44    6250   92.93  6429.8    98.1
#Mann= 3 , 1 , 0
  4316.9     .13       0  4984.8    .047       0  5015.1     .13       0
Bank Sta=4984.8,5015.1
XS Rating Curve= 0 ,0
Exp/Cntr=0.3,0.1

Type RM Length L Ch R = 1 ,23062.7 ,543.7,543.7,543.7
BEGIN DESCRIPTION:
White Oak Swamp US 19.0
END DESCRIPTION:
XS GIS Cut Line= 3
       0.4614106       0.1226282       0.4486955       0.1653602
        0.420852       0.2622251
#Sta/Elev= 30
  4241.8   97.36  4501.8   91.11  4631.8   88.54  4651.8   88.51  4691.8   87.09
  4711.8    85.8  4731.8   85.78  4791.8   84.21  4971.8   82.43  4984.8   81.44
  4986.8   77.44  5013.1   77.44  5015.1   81.44  5020.8   82.72  5110.8   81.76
  5150.8   82.77  5170.8   82.08  5260.8   82.87  5640.8   82.84  5650.8   82.36
  5670.8   82.68  5680.8   82.11  5830.8   83.66  5840.8   85.07  5880.8   86.58
  5910.8   86.41  5930.8   87.51  6100.8    88.5  6440.8    92.8  6716.7   97.28
#Mann= 3 , 1 , 0
  4241.8     .13       0  4984.8    .047       0  5015.1     .13       0
Bank Sta=4984.8,5015.1
XS Rating Curve= 0 ,0
Exp/Cntr=0.5,0.3