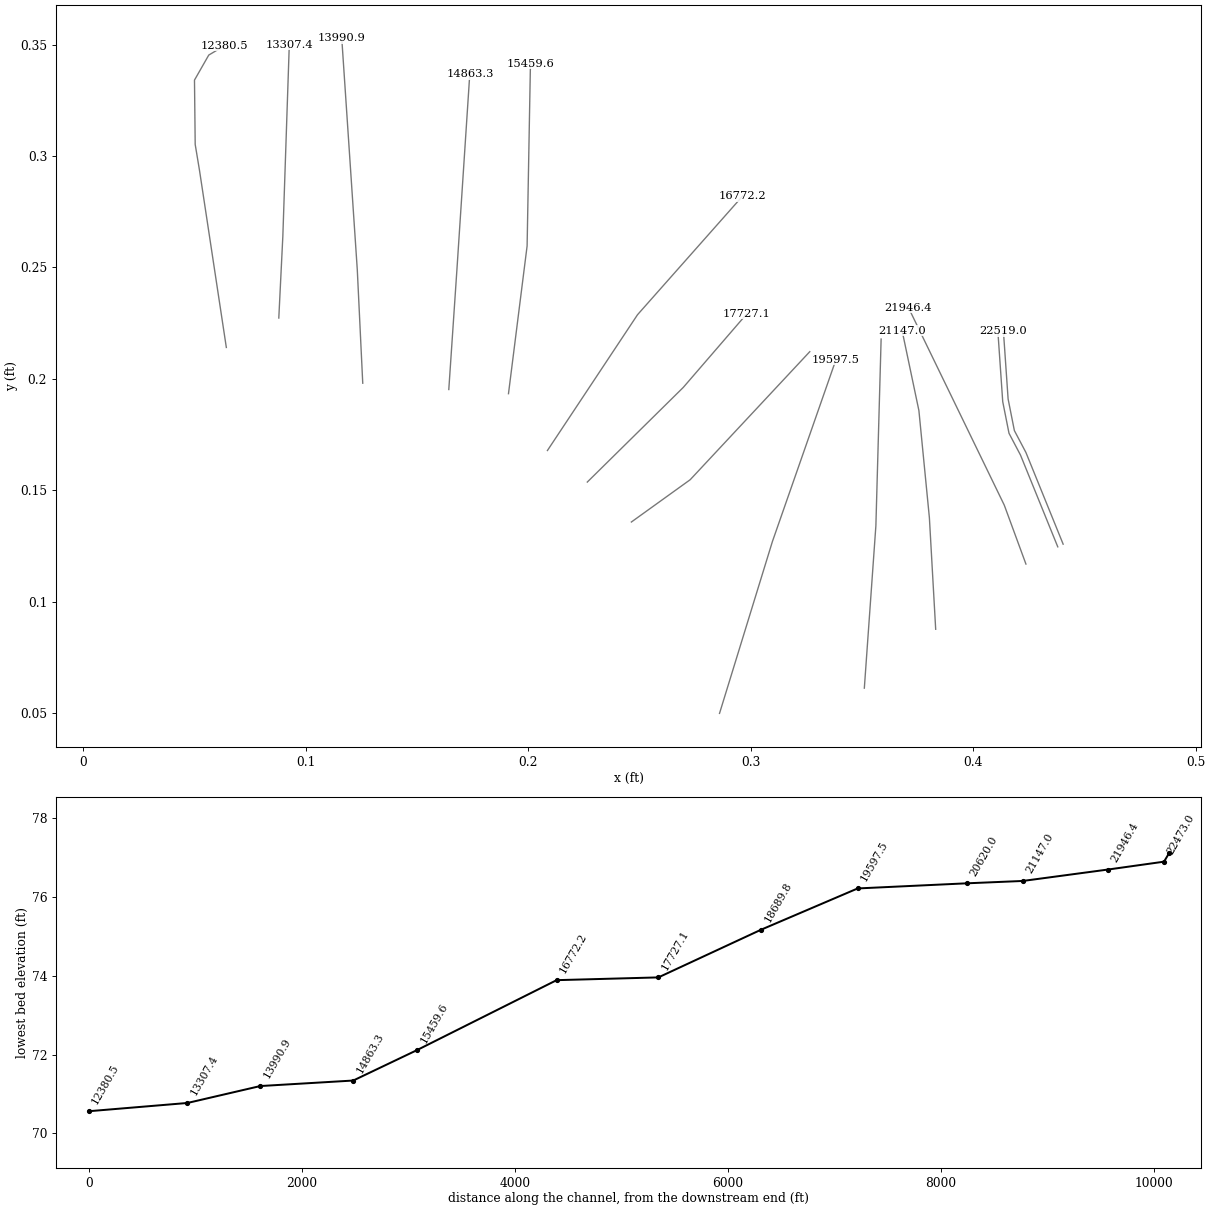
HEC-RAS study White_Oak_Swamp_US_021220.prj: White Oak Swamp US - Wilson County

--- White_Oak_Swamp_US_021220.g01 (geometry) --- (continued)

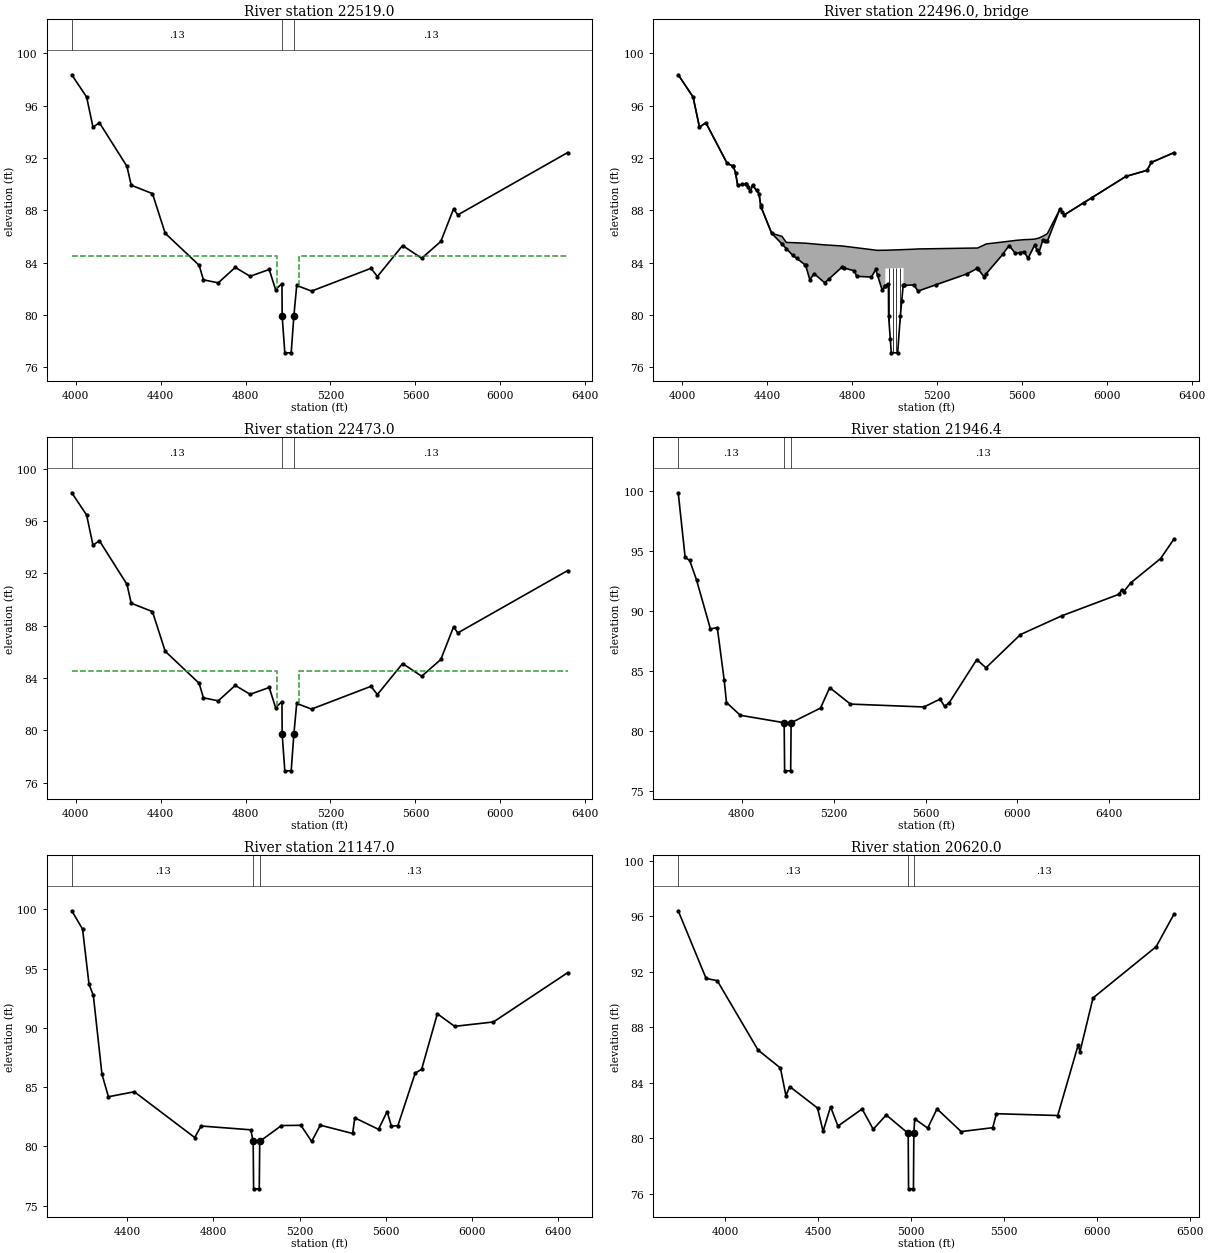
Type RM Length L Ch R = 1 ,22519.0 ,46,46,46
BEGIN DESCRIPTION:
Upstream Section of Bridge/Culvert/Weir
END DESCRIPTION:
XS GIS Cut Line= 5
       0.4404084       0.1258995        0.423672       0.1670279
       0.4184912       0.1768383       0.4156713       0.1910222
       0.4135713       0.2213275
#Sta/Elev= 30
  3981.5   98.36  4051.5   96.66  4081.5   94.35  4111.5    94.7  4241.5   91.36
  4261.5   89.92  4361.5   89.28  4421.5   86.25  4581.5    83.8  4601.5   82.69
  4671.5   82.46  4751.5   83.64  4821.5   82.96  4911.5   83.48  4941.5   81.94
  4971.5    82.4  4972.5   79.91    4985   77.11    5015   77.11  5027.5   79.91
    5041   82.26    5111   81.83    5391   83.57    5421   82.94  5539.7   85.31
  5629.7   84.34  5719.7   85.62  5779.7   88.11  5799.7   87.65  6316.6   92.41
#Mann= 3 , 1 , 0
  3981.5     .13       0  4972.5    .047       0  5027.5     .13       0
#XS Ineff= 2 , 0
       0    4947    84.5    5053       0    84.5
Permanent Ineff=
       F       F
Bank Sta=4972.5,5027.5
XS Rating Curve= 0 ,0
Exp/Cntr=0.5,0.3

Type RM Length L Ch R = 3 ,22496.0 ,,,
BEGIN DESCRIPTION:
Gardners School Rd-TOR
Structure ID: Gardners School Rd
Approximate Survey Structure
END DESCRIPTION:
Bridge Culvert--1,0,-1,-1, 0
Deck Dist Width WeirC Skew NumUp NumDn MinLoCord MaxHiCord MaxSubmerge Is_Ogee
10,26,2.6,0, 53, 53, , , 0.95, 0, 1,1,,
  3981.5  4051.5  4081.5  4111.5  4211.5  4241.5  4251.5  4261.5  4301.5  4321.5
  4331.5  4361.5  4371.5  4421.5  4470.3  4490.3  4521.5  4581.5  4601.5  4621.5
  4671.5  4751.5  4811.5  4821.5  4891.5  4911.5  4920.3  4941.5 4956.91    4957
 5042.89    5043    5091    5111    5341    5391    5421  5431.3  5509.7  5539.7
  5569.7  5609.7  5629.7  5659.7  5679.7  5699.7  5719.7  5779.7  5799.7  6089.7
  6189.7  6209.7  6316.6
   98.35   96.65   94.34   94.69   91.59   91.35   90.84   89.91   90.04   89.43
   89.92   89.27   88.25   86.24      86   85.54   85.52   85.48   85.45   85.42
   85.35   85.27   85.15   85.13   84.99   84.95   84.93   84.94   84.94   84.94
   84.99   84.99   85.02   85.04    85.1   85.11   85.33   85.42   85.57   85.63
   85.69   85.75   85.76   85.79   85.87   86.02    86.2    88.1   87.64   90.58
   91.05   91.65    92.4
   98.35   96.65   94.34   94.69   91.59   91.35   90.84   89.91   90.04   89.43
   89.92   89.27   88.25   86.24   85.41   85.07   84.54   83.79   82.68   83.15
   82.45   83.63   83.37   82.95   82.89   83.47   83.02   81.93   82.17   83.54
   83.59   82.25   82.29   81.82   83.13   83.56   82.93   83.13   84.62    85.3
    84.7   84.82   84.33   85.32   84.73   85.75   85.61    88.1   87.64   90.58
   91.05   91.65    92.4
  3981.5  4051.5  4081.5  4111.5  4211.5  4241.5  4251.5  4261.5  4301.5  4321.5
  4331.5  4361.5  4371.5  4421.5  4470.3  4490.3  4521.5  4581.5  4601.5  4621.5
  4671.5  4751.5  4811.5  4821.5  4891.5  4911.5  4920.3  4941.5 4956.91    4957
 5042.89    5043    5091    5111    5341    5391    5421  5431.3  5509.7  5539.7
  5569.7  5609.7  5629.7  5659.7  5679.7  5699.7  5719.7  5779.7  5799.7  6089.7
  6189.7  6209.7  6316.6
   98.25   96.55   94.24   94.59   91.49   91.26   90.75   89.82   89.95   89.34
   89.83   89.18   88.16   86.23      86   85.54   85.52   85.48   85.45   85.42
   85.35   85.27   85.15   85.13   84.99   84.95   84.93   84.94   84.94   84.94
   84.99   84.99   85.02   85.04    85.1   85.11   85.33   85.42   85.57   85.63
   85.69   85.75   85.76   85.79   85.87   86.02    86.2   88.01   87.55   90.48
   90.95   91.55    92.3
   98.15   96.45   94.14   94.49   91.39   91.15   90.64   89.71   89.84   89.23
   89.72   89.07   88.05   86.04   85.21   84.87   84.34   83.59   82.48   82.95
   82.25   83.43   83.17   82.75   82.69   83.27   82.82   81.73   81.97   83.34
   83.39   82.05   82.09   81.62   82.93   83.36   82.73   82.93   84.42    85.1
    84.5   84.62   84.13   85.12   84.53   85.55   85.41    87.9   87.44   90.38
   90.85   91.45    92.2
Pier Skew, UpSta & Num, DnSta & Num=  ,4974.5, 2 ,4974.5, 2 , 0 , 0 , 0 ,,
       1       1
   78.34   84.55
       1       1
   78.14   84.35
Pier Skew, UpSta & Num, DnSta & Num=  ,4991.5, 2 ,4991.5, 2 , 0 , 0 , 0 ,,
       1       1
    76.1   84.55
       1       1
    75.9   84.35
Pier Skew, UpSta & Num, DnSta & Num=  ,5008.5, 2 ,5008.5, 2 , 0 , 0 , 0 ,,
       1       1
    76.1   84.57
       1       1
    75.9   84.37
Pier Skew, UpSta & Num, DnSta & Num=  ,5025.5, 2 ,5025.5, 2 , 0 , 0 , 0 ,,
       1       1
   78.34   84.58
       1       1
   78.14   84.38
Abutment Skew #Up #Dn= , 2 , 2
  4956.8    4966
   83.54   82.31
  4956.8    4966
   83.34   82.11
Abutment Skew #Up #Dn= , 2 , 2
    5034 5043.09
   81.03   83.59
    5034 5043.09
   80.83   83.39
BR Coef= 1 , 1 , 0 ,1.25, 0 ,,,0.8,0,2,0,
WSPro=,,,, 1 ,,,, 0 ,,,, 0 ,,,,-1 ,-1 ,-1 , 0 , 0 , 0 , 0 , 0
BR U #Sta/Elev= 80
  3981.5   98.35  4051.5   96.65  4081.5   94.34  4111.5   94.69  4211.5   91.59
  4240.3   91.36  4241.5   91.35  4251.5   90.84  4261.5   89.91  4280.3   89.97
  4300.3   90.04  4301.5   90.04  4310.3   89.77  4321.5   89.43  4331.5   89.92
  4350.3   89.51  4361.5   89.27  4370.3   88.37  4371.5   88.25  4421.5   86.24
  4470.3   85.41  4490.3   85.07  4521.5   84.54  4540.3   84.31  4580.3   83.81
  4581.5   83.79  4601.5   82.68  4621.5   83.15  4671.5   82.45  4690.3   82.73
  4751.5   83.63  4760.3   83.59  4811.5   83.37  4821.5   82.95  4891.5   82.89
  4911.5   83.47  4920.3   83.02  4941.5   81.93 4956.91   82.17    4957   82.17
    4966   82.31  4971.5   82.39  4972.5    79.9  4980.3   78.15    4985    77.1
    5015    77.1  5027.5    79.9    5034   81.03    5041   82.25 5042.89   82.25
    5043   82.25    5091   82.29    5111   81.82  5195.1    82.3    5341   83.13
    5391   83.56  5395.1   83.47    5421   82.93  5431.3   83.13  5509.7   84.62
  5539.7    85.3  5569.7    84.7  5591.3   84.76  5609.7   84.82  5629.7   84.33
  5659.7   85.32  5671.3   84.98  5679.7   84.73  5699.7   85.75  5711.3   85.67
  5719.7   85.61  5779.7    88.1  5791.3   87.83  5799.7   87.64  5891.3   88.57
  5931.3   88.97  6089.7   90.58  6189.7   91.05  6209.7   91.65  6316.6    92.4
BR U #Mann= 3
  3981.5     .13  4972.5    .047  5027.5     .13
BR U Banks=4972.5,5027.5
BR D #Sta/Elev= 80
  3981.5   98.15  4051.5   96.45  4081.5   94.14  4111.5   94.49  4211.5   91.39
  4240.3   91.16  4241.5   91.15  4251.5   90.64  4261.5   89.71  4280.3   89.77
  4300.3   89.84  4301.5   89.84  4310.3   89.57  4321.5   89.23  4331.5   89.72
  4350.3   89.31  4361.5   89.07  4370.3   88.17  4371.5   88.05  4421.5   86.04
  4470.3   85.21  4490.3   84.87  4521.5   84.34  4540.3   84.11  4580.3   83.61
  4581.5   83.59  4601.5   82.48  4621.5   82.95  4671.5   82.25  4690.3   82.53
  4751.5   83.43  4760.3   83.39  4811.5   83.17  4821.5   82.75  4891.5   82.69
  4911.5   83.27  4920.3   82.82  4941.5   81.73 4956.91   81.97    4957   81.97
    4966   82.11  4971.5   82.19  4972.5    79.7  4980.3   77.95    4985    76.9
    5015    76.9  5027.5    79.7    5034   80.83    5041   82.05 5042.89   82.05
    5043   82.05    5091   82.09    5111   81.62  5195.1    82.1    5341   82.93
    5391   83.36  5395.1   83.27    5421   82.73  5431.3   82.93  5509.7   84.42
  5539.7    85.1  5569.7    84.5  5591.3   84.56  5609.7   84.62  5629.7   84.13
  5659.7   85.12  5671.3   84.78  5679.7   84.53  5699.7   85.55  5711.3   85.47
  5719.7   85.41  5779.7    87.9  5791.3   87.63  5799.7   87.44  5891.3   88.37
  5931.3   88.77  6089.7   90.38  6189.7   90.85  6209.7   91.45  6316.6    92.2
BR D #Mann= 3
  3981.5     .13  4972.5    .047  5027.5     .13
BR D Banks=4972.5,5027.5
BC Design=,, 0 ,, 0 ,,,,,,
BC HTab HWMax=98.36
BC Use User HTab Curves=0
BC User HTab FreeFlow(D)= 0

Type RM Length L Ch R = 1 ,22473.0 ,526.6,526.6,526.6
BEGIN DESCRIPTION:
Downstream Section of Bridge/Culvert/Weir
END DESCRIPTION:
XS GIS Cut Line= 5
       0.4379917       0.1246911       0.4212553       0.1658195
       0.4160745         0.17563       0.4132546       0.1898138
       0.4111547       0.2201192
#Sta/Elev= 30
  3981.5   98.15  4051.5   96.45  4081.5   94.14  4111.5   94.49  4241.5   91.15
  4261.5   89.71  4361.5   89.07  4421.5   86.04  4581.5   83.59  4601.5   82.48
  4671.5   82.25  4751.5   83.43  4821.5   82.75  4911.5   83.27  4941.5   81.73
  4971.5   82.19  4972.5    79.7    4985    76.9    5015    76.9  5027.5    79.7
    5041   82.05    5111   81.62    5391   83.36    5421   82.73  5539.7    85.1
  5629.7   84.13  5719.7   85.41  5779.7    87.9  5799.7   87.44  6316.6    92.2
#Mann= 3 , 1 , 0
  3981.5     .13       0  4972.5    .047       0  5027.5     .13       0
#XS Ineff= 2 , 0
       0    4947    84.5    5053       0    84.5
Permanent Ineff=
       F       F
Bank Sta=4972.5,5027.5
XS Rating Curve= 0 ,0
Exp/Cntr=0.5,0.3

Type RM Length L Ch R = 1 ,21946.4 ,799.4,799.4,799.4
BEGIN DESCRIPTION:
White Oak Swamp US 18.0
END DESCRIPTION:
XS GIS Cut Line= 3
       0.4236817       0.1169688        0.413956       0.1433822
       0.3708612        0.232042
#Sta/Elev= 30
  4523.9   99.82  4553.9   94.45  4573.9   94.19  4603.9   92.55  4663.9    88.5
  4693.9   88.61  4723.9   84.24  4733.9   82.38  4793.9   81.32  4984.9    80.7
  4986.9    76.7  5013.2    76.7  5015.2    80.7  5143.1   81.92  5183.1   83.62
  5273.1   82.25  5593.1   82.01  5663.1   82.66  5683.1   82.07  5703.1   82.36
  5823.1   85.95  5863.1   85.27  6013.1   88.03  6193.1   89.59  6443.1   91.39
  6453.1   91.76  6463.1   91.61  6493.1   92.33  6623.1   94.35  6681.4   95.98
#Mann= 3 , 1 , 0
  4523.9     .13       0  4984.9    .047       0  5015.2     .13       0
Bank Sta=4984.9,5015.2
XS Rating Curve= 0 ,0
Exp/Cntr=0.3,0.1

Type RM Length L Ch R = 1 ,21147.0 ,527,527,527
BEGIN DESCRIPTION:
White Oak Swamp US 17.0
END DESCRIPTION:
XS GIS Cut Line= 4
       0.3831231       0.0877289       0.3802934       0.1377197
       0.3755773       0.1858241       0.3680315       0.2216666
#Sta/Elev= 30
  4143.7   99.87  4193.7   98.33  4223.7   93.67  4243.7   92.73  4283.7   86.08
  4313.7   84.18  4433.7    84.6  4713.7   80.74  4743.7   81.71  4973.7   81.39
  4984.9   80.41  4986.9   76.41  5013.2   76.41  5015.2   80.41  5116.1   81.75
  5206.1   81.77  5256.1   80.41  5296.1   81.78  5446.1   81.08  5456.1    82.4
  5566.1   81.43  5606.1   82.93  5626.1   81.69  5656.1   81.75  5736.1   86.17
  5766.1    86.5    5839   91.18    5919   90.12    6099   90.49  6442.6   94.64
#Mann= 3 , 1 , 0
  4143.7     .13       0  4984.9    .047       0  5015.2     .13       0
Bank Sta=4984.9,5015.2
XS Rating Curve= 0 ,0
Exp/Cntr=0.3,0.1

Type RM Length L Ch R = 1 ,20620.0 ,1022.5,1022.5,1022.5
BEGIN DESCRIPTION:
White Oak Swamp US 16.0
END DESCRIPTION:
XS GIS Cut Line= 3
       0.3510535       0.0613187       0.3562448       0.1341612
       0.3585993       0.2178937
#Sta/Elev= 30
  3746.7   96.41  3896.7   91.53  3956.7   91.37  4176.7   86.36  4296.7   85.07
  4326.7   83.07  4346.7   83.73  4496.7   82.18  4526.7    80.5  4566.7   82.27
  4606.7   80.88  4736.7   82.11  4796.7   80.65  4866.7   81.68  4984.9   80.35
  4986.9   76.35  5013.2   76.35  5015.2   80.35    5020    81.4    5090   80.73
    5140   82.12    5270   80.48    5440   80.76    5460   81.77    5790   81.64
    5900   86.72    5910   86.25    5980   90.12    6320   93.82  6416.1   96.17
#Mann= 3 , 1 , 0
  3746.7     .13       0  4984.9    .047       0  5015.2     .13       0
Bank Sta=4984.9,5015.2
XS Rating Curve= 0 ,0
Exp/Cntr=0.3,0.1

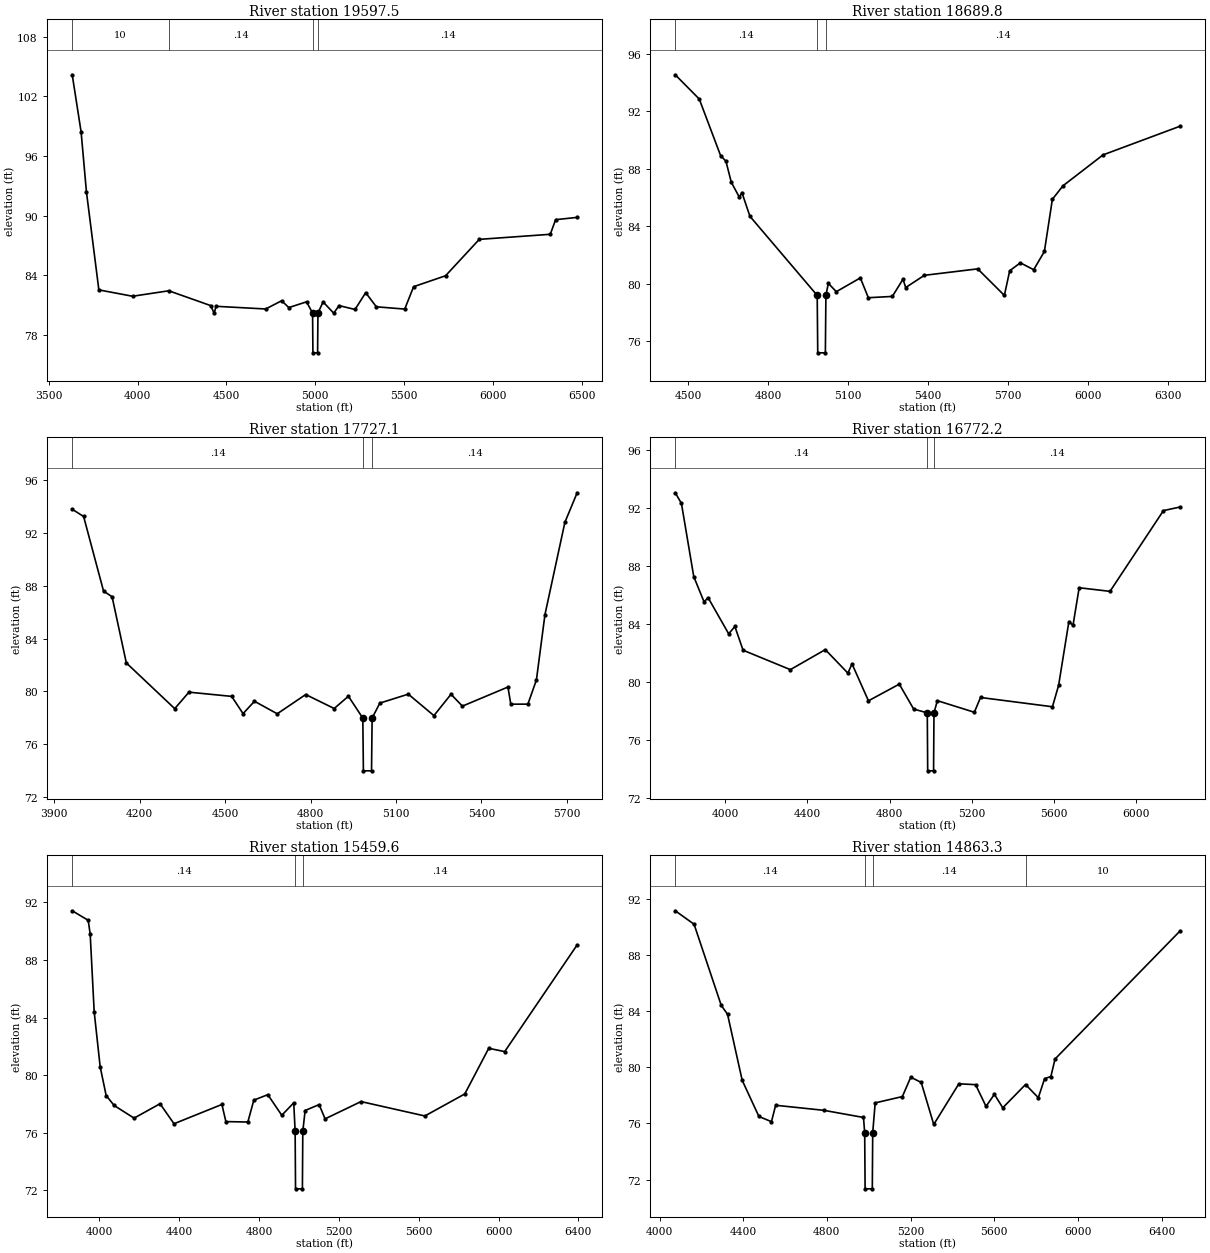
Type RM Length L Ch R = 1 ,19597.5 ,907.7,907.7,907.7
BEGIN DESCRIPTION:
White Oak Swamp US 15.0
END DESCRIPTION:
XS GIS Cut Line= 3
       0.2859711            0.05       0.3097375       0.1270759
       0.3382967       0.2086457
#Sta/Elev= 30
  3630.9  104.18  3680.9   98.44  3710.9   92.42  3780.9   82.55  3970.9   81.91
  4174.9   82.46  4410.9   80.97  4430.9   80.19  4440.9    80.9  4720.9   80.63
  4810.9   81.46  4850.9   80.77  4950.9   81.35  4984.9   80.22  4986.9   76.22
  5013.2   76.22  5015.2   80.22  5044.1   81.34  5104.1   80.21  5134.1   80.97
  5224.1   80.58  5284.1   82.27  5344.1   80.85  5504.1   80.62  5554.1   82.87
  5734.1   83.97  5924.1   87.63  6324.1   88.14  6354.1   89.61  6475.4   89.84
#Mann= 4 , 1 , 0
  3630.9      10       0  4174.9     .14       0  4984.9    .047       0
  5015.2     .14       0
Bank Sta=4984.9,5015.2
XS Rating Curve= 0 ,0
Exp/Cntr=0.3,0.1

Type RM Length L Ch R = 1 ,18689.8 ,962.7,962.7,962.7
BEGIN DESCRIPTION:
White Oak Swamp US 14.0
END DESCRIPTION:
XS GIS Cut Line= 3
       0.2463558       0.1358333       0.2727863       0.1548015
       0.3265297       0.2122343
#Sta/Elev= 30
  4451.5   94.54  4541.5   92.85  4621.5   88.91  4641.5   88.52  4661.5   87.06
  4691.5   86.02  4701.5   86.33  4731.5   84.68  4983.7   79.17  4985.7   75.17
  5014.3   75.17  5016.3   79.17  5025.4   80.01  5055.4   79.43  5145.4   80.39
  5175.4   79.01  5265.4    79.1  5305.4    80.3  5315.4   79.72  5385.4   80.57
  5585.4   81.02  5685.4   79.17  5705.4   80.89  5745.4   81.44  5795.4   80.96
  5835.4   82.23  5865.4   85.87  5905.4   86.81  6055.4   88.96  6344.5   90.96
#Mann= 3 , 1 , 0
  4451.5     .14       0  4983.7    .047       0  5016.3     .14       0
Bank Sta=4983.7,5016.3
XS Rating Curve= 0 ,0
Exp/Cntr=0.3,0.1

Type RM Length L Ch R = 1 ,17727.1 ,954.9,954.9,954.9
BEGIN DESCRIPTION:
White Oak Swamp US 13.0
END DESCRIPTION:
XS GIS Cut Line= 3
       0.2265481       0.1537545       0.2696807       0.1962004
        0.298233       0.2292123
#Sta/Elev= 30
  3963.1   93.81  4003.1   93.26  4073.1    87.6  4103.1   87.17  4153.1   82.15
  4323.1   78.68  4373.1   79.93  4523.1   79.61  4563.1    78.3  4603.1   79.24
  4683.1   78.29  4783.1   79.75  4883.1   78.69  4933.1   79.62  4983.7   77.96
  4985.7   73.96  5014.3   73.96  5016.3   77.96  5043.4    79.1  5143.4   79.78
  5233.4   78.15  5293.4   79.77  5333.4   78.87  5493.4   80.32  5503.4   79.02
  5563.4   79.02  5593.4   80.86  5623.4   85.82  5693.4   92.82  5736.4   95.06
#Mann= 3 , 1 , 0
  3963.1     .14       0  4983.7    .047       0  5016.3     .14       0
Bank Sta=4983.7,5016.3
XS Rating Curve= 0 ,0
Exp/Cntr=0.3,0.1

Type RM Length L Ch R = 1 ,16772.2 ,1312.6,1312.6,1312.6
BEGIN DESCRIPTION:
White Oak Swamp US 12.0
END DESCRIPTION:
XS GIS Cut Line= 3
       0.2086269       0.1679029       0.2491206        0.228813
       0.2963466       0.2820328
#Sta/Elev= 30
  3757.5   93.07  3787.5   92.34  3847.5   87.29  3897.5   85.55  3917.5   85.83
  4017.5   83.34  4047.5   83.85  4087.5   82.21  4317.5   80.87  4487.5   82.25
  4597.5   80.63  4617.5   81.27  4697.5   78.72  4847.5   79.87  4917.5   78.15
  4983.7   77.89  4985.7   73.89  5014.3   73.89  5016.3   77.89  5032.7   78.73
  5212.7   77.93  5242.7   78.95  5592.7   78.31  5622.7   79.79  5672.7   84.19
  5692.7   83.93  5722.7   86.52  5872.7   86.27  6132.7   91.84  6214.1   92.09
#Mann= 3 , 1 , 0
  3757.5     .14       0  4983.7    .047       0  5016.3     .14       0
Bank Sta=4983.7,5016.3
XS Rating Curve= 0 ,0
Exp/Cntr=0.3,0.1

Type RM Length L Ch R = 1 ,15459.6 ,596.3,596.3,596.3
BEGIN DESCRIPTION:
White Oak Swamp US 11.0
END DESCRIPTION:
XS GIS Cut Line= 3
       0.1911225       0.1933899       0.1994927       0.2596532
        0.200994       0.3414615
#Sta/Elev= 30
  3863.8   91.42  3943.8   90.76  3953.8   89.81  3973.8   84.41  4003.8   80.59
  4033.8   78.59  4073.8    77.9  4173.8   77.02  4303.8   78.02  4373.8   76.63
  4613.8   77.97  4633.8   76.78  4743.8   76.75  4773.8   78.27  4843.8   78.65
  4913.8   77.22  4973.8   78.08  4980.8   76.11  4982.8   72.11  5017.2   72.11
  5019.2   76.11  5030.9   77.55  5100.9   77.96  5130.9   76.97  5310.9   78.17
  5630.9   77.17  5830.9    78.7  5950.9   81.87  6030.9   81.64  6393.9   89.05
#Mann= 3 , 1 , 0
  3863.8     .14       0  4980.8    .047       0  5019.2     .14       0
Bank Sta=4980.8,5019.2
XS Rating Curve= 0 ,0
Exp/Cntr=0.3,0.1

Type RM Length L Ch R = 1 ,14863.3 ,872.4,872.4,872.4
BEGIN DESCRIPTION:
White Oak Swamp US 10.0
END DESCRIPTION:
XS GIS Cut Line= 3
       0.1642954       0.1952563        0.167979       0.2495149
       0.1737276       0.3367397
#Sta/Elev= 30
  4075.1   91.17  4165.1   90.21  4295.1   84.42  4325.1   83.79  4395.1   79.08
  4475.1    76.5  4535.1   76.13  4555.1    77.3  4785.1   76.94  4975.1   76.43
  4980.8   75.34  4982.8   71.34  5017.2   71.34  5019.2   75.34    5031   77.47
    5161   77.92    5201    79.3    5251   78.93    5311   75.93    5431   78.83
    5511   78.77    5561   77.22    5601   78.08    5641   77.12  5749.9   78.78
    5811   77.84    5841    79.2    5871   79.35    5891    80.6  6489.2   89.74
#Mann= 4 , 1 , 0
  4075.1     .14       0  4980.8    .047       0  5019.2     .14       0
  5749.9      10       0
Bank Sta=4980.8,5019.2
XS Rating Curve= 0 ,0
Exp/Cntr=0.3,0.1

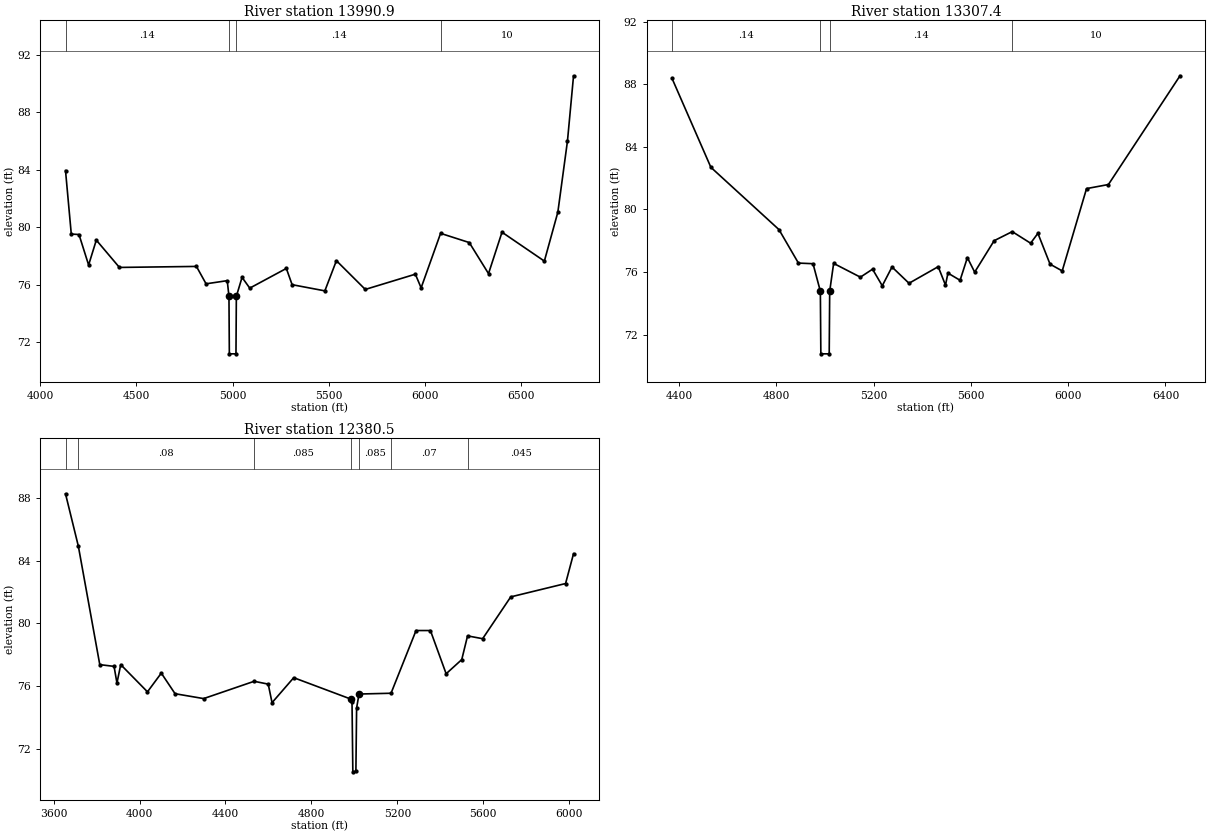
Type RM Length L Ch R = 1 ,13990.9 ,683.5,683.5,683.5
BEGIN DESCRIPTION:
White Oak Swamp US 9.0
END DESCRIPTION:
XS GIS Cut Line= 3
       0.1256233        0.198086       0.1231721       0.2489478
        0.116191       0.3527745
#Sta/Elev= 30
  4131.9   83.95  4161.9   79.53  4201.9    79.5  4251.9   77.38  4291.9   79.11
  4411.9   77.21  4811.9   77.28  4861.9   76.07  4971.9   76.29  4980.8    75.2
  4982.8    71.2  5017.2    71.2  5019.2    75.2  5048.8   76.52  5088.8   75.77
  5278.8   77.14  5308.8   76.01  5478.8   75.58  5538.8   77.68  5688.8   75.68
  5948.8   76.74  5978.8   75.79  6079.9   79.58  6228.8   78.94  6328.8   76.78
  6398.8   79.66  6618.8   77.65  6688.8   81.05  6738.8      86  6770.4   90.54
#Mann= 4 , 1 , 0
  4131.9     .14       0  4980.8    .047       0  5019.2     .14       0
  6079.9      10       0
Bank Sta=4980.8,5019.2
XS Rating Curve= 0 ,0
Exp/Cntr=0.3,0.1

Type RM Length L Ch R = 1 ,13307.4 ,926.9,926.9,926.9
BEGIN DESCRIPTION:
White Oak Swamp US 8.0
END DESCRIPTION:
XS GIS Cut Line= 3
       0.0878944       0.2273259       0.0897087       0.2639779
       0.0926105       0.3499449
#Sta/Elev= 30
  4370.6   88.38  4530.6   82.69  4810.6   78.71  4890.6   76.57  4950.6   76.53
  4980.8   74.77  4982.8   70.77  5017.2   70.77  5019.2   74.77  5035.4   76.55
  5145.4   75.67  5195.4   76.18  5235.4   75.12  5275.4   76.32  5345.4   75.28
  5465.4   76.34  5495.4   75.16  5505.4   75.93  5555.4   75.47  5585.4   76.92
  5615.4   75.99  5695.4      78  5769.9   78.58  5845.4   77.84  5875.4   78.47
  5925.4    76.5  5975.4   76.07  6075.4   81.33  6165.4   81.59  6459.8   88.54
#Mann= 4 , 1 , 0
  4370.6     .14       0  4980.8    .047       0  5019.2     .14       0
  5769.9      10       0
Bank Sta=4980.8,5019.2
XS Rating Curve= 0 ,0
Exp/Cntr=0.3,0.1

Type RM Length L Ch R = 1 ,12380.5 ,0,0,0
BEGIN DESCRIPTION:
White Oak Swamp US 7.8 (Tie-in to new DTL STUDY)
END DESCRIPTION:
XS GIS Cut Line= 6
       0.0643138       0.2141208       0.0522458       0.2936181
       0.0503208        0.305168            0.05       0.3340426
       0.0564166       0.3452716       0.0634748       0.3494424
#Sta/Elev= 30
 3655.38   88.25 3715.25   84.91 3814.91   77.38 3881.38   77.27 3894.83   76.21
 3912.46   77.38 4036.89   75.65 4101.27   76.84 4165.38   75.53 4298.41   75.22
 4533.38   76.32 4599.01   76.14 4616.73   74.96 4717.66   76.55  4985.3   75.18
    4989   74.98 4992.83   70.56 5007.07   70.59  5010.4   74.62 5021.55   75.51
 5170.63   75.56 5287.05   79.55 5353.94   79.55 5427.12    76.8  5499.8    77.7
 5526.82   79.21 5597.02   79.03 5727.81   81.69 5983.08   82.54 6020.19   84.44
#Mann= 7 ,-1 , 0
 3655.38    .045       0 3715.25     .08       0 4533.38    .085       0
  4985.3     .05       0 5021.55    .085       0 5170.63     .07       0
 5526.82    .045       0
Bank Sta=4985.3,5021.55
XS Rating Curve= 0 ,0
Exp/Cntr=0.3,0.1

Chan Stop Cuts=-1
Use User Specified Reach Order=0