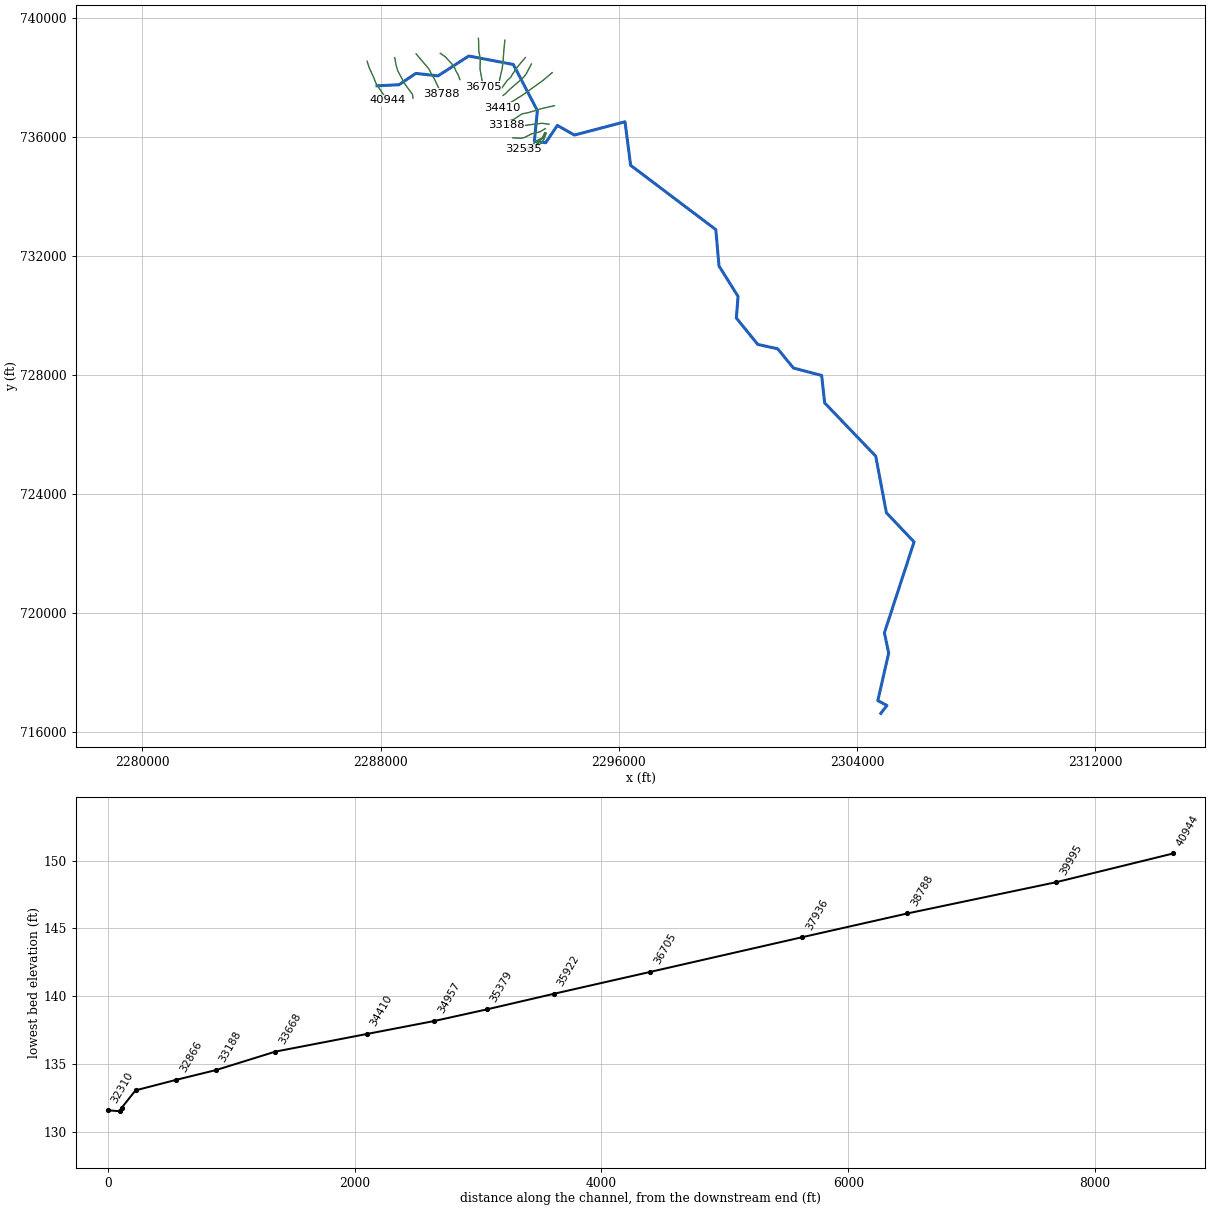
--- dtl_Bloomery_Swamp.prj (project) ---

Proj Title=DTL_Bloomery_Swamp
Current Plan=p01
Default Exp/Contr=0.3,0.1
English Units
Geom File=g01
Flow File=f01
Flow File=f02
Plan File=p01
Plan File=p02
Y Axis Title=Elevation
X Axis Title(PF)=Main Channel Distance
X Axis Title(XS)=Station
BEGIN DESCRIPTION:
END DESCRIPTION:
DSS File=dss
DSS Export Rating Curves= 0
DSS Export Rating Curve Sorted= 0
DSS Export Volume Flow Curves= 0
DXF OffsetX= 0
DXF OffsetY= 0
DXF ScaleX= 1
DXF ScaleY= 10

--- dtl_Bloomery_Swamp.p01 (plan) ---

Plan Title=DTL_Bloomery_Swamp
Program Version=4.00
Short Identifier=Mutiple
Geom File=g01
Flow File=f01
Subcritical Flow
K Sum by GR= 0
Std Step Tol= 0.01
Critical Tol= 0.01
Num of Std Step Trials= 20
Max Error Tol= 0.3
Flow Tol Ratio= 0.001
Split Flow NTrial= 30
Split Flow Tol= 0.02
Split Flow Ratio= 0.02
Log Output Level= 0
Friction Slope Method= 1
Unsteady Friction Slope Method= 2
Unsteady Bridges Friction Slope Method= 1
Parabolic Critical Depth
Global Vel Dist= 0 , 0 , 0
Global Log Level= 0
CheckData=True
Encroach Param=-1 ,10,10, 2
Encroach River=Bloomery Swamp
Encroach Reach=Bloomery Swamp
Encroach Node=40944
       1     811     944
Encroach Node=39995
       1  809.26  979.43
Encroach Node=38788
       1     725    1031
Encroach Node=37936
       1  473.45   705.6
Encroach Node=36705
       1  605.36  863.43
Encroach Node=35922
       1  523.12  888.94
Encroach Node=35379
       1  442.46  776.79
Encroach Node=34957
       1  459.85  804.66
Encroach Node=34410
       1  592.66 1294.29
Encroach Node=33668
       1  362.99  792.53
Encroach Node=33188
       1  181.89  735.36
Encroach Node=32866
       1  175.93  638.05
Encroach Node=32535
       1     108     705
Encroach Node=32421
       1  384.98  435.07
Encroach Node=32405
       1     389     462
Encroach Node=32310
       1  358.05  434.76
Encroach Node=32259
       1     337     466
Encroach Node=32012
       1     164     435
Encroach Node=31380
       1     143     375
Encroach Node=31312
       1  369.69     488
Encroach Node=31230
       1     345  471.07
Encroach Node=31131
       1     226     493
Encroach Node=30629
       1     666     958
Encroach Node=30078
       1     465     704
Encroach Node=29708
       1     599     758
Encroach Node=29608
       1     488     634
Encroach Node=29397
       1     424     572
Encroach Node=29184
       1     576     894
Encroach Node=28914
       1     150     750
Encroach Node=27911
       1  587.75 1345.77
Encroach Node=27492
       1  491.83  1124.5
Encroach Node=27192
       1     522 1217.95
Encroach Node=26437
       1  456.85  825.75
Encroach Node=25891
       1  312.82  626.75
Encroach Node=25463
       1  127.88  576.52
Encroach Node=25406
       1  596.71  688.33
Encroach Node=25401
       1  812.41  863.18
Encroach Node=25184
       1  740.31  796.31
Encroach Node=24903
       1  565.97     640
Encroach Node=24452
       1  469.04     520
Encroach Node=24287
       1     398     455
Encroach Node=24153
       1  393.37  464.62
Encroach Node=23959
       1  346.97  442.97
Encroach Node=23520
       1  258.15     448
Encroach Node=23049
       1  231.54     488
Encroach Node=22556
       1  145.37  391.49
Encroach Node=21818
       1  512.85   826.7
Encroach Node=20983
       1  232.55  539.82
Encroach Node=20212
       1     523     855
Encroach Node=19321
       1  462.65  647.83
Encroach Node=18602
       1     604     870
Encroach Node=17424
       1    1303    1683
Encroach Node=16464
       1    1303    1686
Encroach Node=14809
       1 1332.12 1663.18
Encroach Node=13629
       1 1461.12 1892.76
Encroach Node=13310
       1 1513.89 2035.67
Encroach Node=12968
       1    1684    1892
Encroach Node=12777
       1    1698    1906
Encroach Node=12467
       1    1470    1757
Encroach Node=12274
       1    1506    1751
Encroach Node=12065
       1    1506    1751
Encroach Node=11585
       1    1013    1565
Encroach Node=10910
       1  820.57  1187.5
Encroach Node=9890
       1  868.33 1324.08
Encroach Node=8067
       1 1513.72 1854.96
Encroach Node=5958
       1     781    1345
Encroach Node=4623
       1    1489    1850
Encroach Node=3673
       1    1832    2080
Encroach Node=3387
       1    1823    1993
Encroach Node=3204
       1    1779 1920.67
Encroach Node=2665
       1     793    1177
Encroach Node=2060
       1  747.07 1178.78
Encroach Node=951
       1 1288.92 2011.64
Computation Interval=1HOUR
Output Interval=1HOUR
Run HTab= 0
Run UNet= 0
Run PostProcess= 0
Run WQNet= 0
UNET Theta= 1
UNET Theta Warmup= 1
UNET ZTol= 0.02
UNET ZSATol= 0.05
UNET MxIter= 20
UNET MaxInSteps= 0
UNET DtIC= 0
UNET DtMin= 0
UNET MaxCRTS= 20
UNET WFStab= 2
UNET SFStab= 1
UNET WFX= 1
UNET SFX= 1
UNET DSS MLevel= 4
UNET DZMax Abort= 100
UNET Convert EG Bridges= 0
UNET Use Existing IB Tables=-1
UNET Froude Reduction=False
UNET Froude Limit= 1
UNET Froude Power= 10
UNET Time Slicing=0,0, 5
Instantaneous Interval=1HOUR
DSS File=dss
Write IC File= 0
Echo Input=False
Echo Output=False
Write Detailed= 0
Detailed Automatic Start=False, 10
WQ ULTIMATE=-1
WQ Max Comp Step=1HOUR
WQ Output Interval=15MIN
WQ Output Selected Increments= 0
WQ Output face flow=0
WQ Output face velocity=0
WQ Output face area=0
WQ Output face dispersion=0
WQ Output cell volume=0
WQ Output cell surface area=0
WQ Output cell continuity=0
WQ Output face conc=0
WQ Output face dconc_dx=0
WQ Output face courant=0
WQ Output face peclet=0
WQ Output face adv mass=0
WQ Output face disp mass=0
WQ Output cell mass=0
WQ Output cell source sink temp=0
WQ Output cell source sink nsm=0
WQ Output MaxMinRange=-1
WQ Daily Max Min Mean=-1
WQ Daily Range=0
WQ Daily Time=0
WQ Create Restart=0
WQ Fixed Restart=0
WQ System Summary=False
Sorting and Armoring Iterations= 10
XS Update Threshold= 0.02
Hydraulics Update Threshold= 0.02
Energy Slope Method= 1
Volume Change Method= 0
XS Weighting Method= 0
Number of US Weighted Cross Sections= 1
Number of DS Weighted Cross Sections= 1
Upstream XS Weight=0.25
Main XS Weight=0.5
Downstream XS Weight=0.25
Number of DS XS's Weighted with US Boundary= 1
Upstream Boundary Weight= 1
Weight of XSs Associated with US Boundary= 0
Number of US XS's Weighted with DS Boundary= 1
Downstream Boundary Weight= 0.5
Weight of XSs Associated with DS Boundary= 0.5
Sediment Output Level= 4
Mass or Volume Output= 0
Output Increment Type= 1
Profile and TS Output Increment= 10
XS Output Flag= 0
XS Output Increment= 10
Disregard all LS=0
Disregard all Conn=0
Disregard all Breaches=0
Disregard all Pumps=0

--- dtl_Bloomery_Swamp.p02 (plan) ---

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Plan Title=DTL_Bloomery_Swamp_Future
Program Version=3.13
Short Identifier=Future
Geom File=g01
Flow File=f02
Encroach Param=-1 ,0,0, 0
UNET Convert EG Bridges=-1

--- dtl_Bloomery_Swamp.f01 (steady flow) ---

Flow Title=DTL_Bloomery_Swamp
Program Version=4.00
Number of Profiles= 6
Profile Names=100-yr,FW,10-yr,25-yr,50-yr,500-yr
River Rch & RM=Bloomery Swamp,Bloomery Swamp  ,40944
    1620    1620     720    1030    1300    2520
River Rch & RM=Bloomery Swamp,Bloomery Swamp  ,36705
    2040    2040     930    1320    1660    3150
River Rch & RM=Bloomery Swamp,Bloomery Swamp  ,32012
    2130    2130     970    1370    1730    3270
River Rch & RM=Bloomery Swamp,Bloomery Swamp  ,29608
    2230    2230    1020    1440    1810    3410
River Rch & RM=Bloomery Swamp,Bloomery Swamp  ,23049
    2510    2510    1160    1630    2040    3820
River Rch & RM=Bloomery Swamp,Bloomery Swamp  ,16464
    2540    2540    1180    1650    2070    3870
River Rch & RM=Bloomery Swamp,Bloomery Swamp  ,12968
    2610    2610    1210    1770    2130    3970
River Rch & RM=Bloomery Swamp,Bloomery Swamp  ,8067
    2690    2690    1260    1760    2200    4090
River Rch & RM=Bloomery Swamp,Bloomery Swamp  ,4623
    2830    2830    1330    1850    2310    4290
Boundary for River Rch & Prof#=Bloomery Swamp,Bloomery Swamp  , 1
Up Type= 0
Dn Type= 3
Dn Slope=5.500451E-04
Boundary for River Rch & Prof#=Bloomery Swamp,Bloomery Swamp  , 2
Up Type= 0
Dn Type= 3
Dn Slope=5.500451E-04
Boundary for River Rch & Prof#=Bloomery Swamp,Bloomery Swamp  , 3
Up Type= 0
Dn Type= 3
Dn Slope=5.500451E-04
Boundary for River Rch & Prof#=Bloomery Swamp,Bloomery Swamp  , 4
Up Type= 0
Dn Type= 3
Dn Slope=5.500451E-04
Boundary for River Rch & Prof#=Bloomery Swamp,Bloomery Swamp  , 5
Up Type= 0
Dn Type= 3
Dn Slope=5.500451E-04
Boundary for River Rch & Prof#=Bloomery Swamp,Bloomery Swamp  , 6
Up Type= 0
Dn Type= 3
Dn Slope=5.500451E-04
Gate Openings=Bloomery Swamp  ,Bloomery Swamp  ,32514   ,Gate #1     ,
     2.4       2     2.4       2     2.4       2     2.4       2     2.4       2
     2.4       2
DSS Import GetInterval= 0
DSS Import GetPeak= 0
DSS Import FillOption= 0

--- dtl_Bloomery_Swamp.f02 (steady flow) ---

Flow Title=DTL_Bloomery_Swamp_Future
Program Version=3.13
Number of Profiles= 3
Profile Names=100-yr-10%,100-yr-20%,100-yr-35%
River Rch & RM=Bloomery Swamp,Bloomery Swamp  ,40944
    2740    3520    4290
River Rch & RM=Bloomery Swamp,Bloomery Swamp  ,36705
    3440    4410    5390
River Rch & RM=Bloomery Swamp,Bloomery Swamp  ,32012
    3580    4580    5600
River Rch & RM=Bloomery Swamp,Bloomery Swamp  ,29608
    3740    4790    5850
River Rch & RM=Bloomery Swamp,Bloomery Swamp  ,23049
    4190    5370    6560
River Rch & RM=Bloomery Swamp,Bloomery Swamp  ,16464
    4240    5440    6640
River Rch & RM=Bloomery Swamp,Bloomery Swamp  ,12968
    4350    5580    6810
River Rch & RM=Bloomery Swamp,Bloomery Swamp  ,8067
    4490    5750    7030
River Rch & RM=Bloomery Swamp,Bloomery Swamp  ,4623
    4710    6040    7380
Boundary for River Rch & Prof#=Bloomery Swamp,Bloomery Swamp  , 1
Up Type= 0
Dn Type= 3
Dn Slope=5.500451E-04
Boundary for River Rch & Prof#=Bloomery Swamp,Bloomery Swamp  , 2
Up Type= 0
Dn Type= 3
Dn Slope=5.500451E-04
Boundary for River Rch & Prof#=Bloomery Swamp,Bloomery Swamp  , 3
Up Type= 0
Dn Type= 3
Dn Slope=5.500451E-04
Gate Openings=Bloomery Swamp  ,Bloomery Swamp  ,32514   ,Gate #1     ,
     2.4       2     2.4       2     2.4       2
DSS Import GetInterval= 0
DSS Import GetPeak= 0
DSS Import FillOption= 0

--- dtl_Bloomery_Swamp.g01 (geometry) ---

Geom Title=DTL_Bloomery_Swamp
Program Version=4.00

River Reach=Bloomery Swamp  ,Bloomery Swamp
Reach XY= 30
2287879.48661639737733.3691951932288617.01731852737769.052342594
2289180.38537407738150.1287315042289926.04509632738066.795398191
2290960.76731853738735.1981759522292457.29509632738450.475953743
2293264.58676298736900.1287315192293163.89231852735866.274564832
2293543.23259632  735820.26762042293935.31291932 736402.86095421
2294507.40397923736078.3974306292296207.29509632736524.260675967
2296396.53120738735061.5870648622299257.64231847732900.128731489
2299363.54509628731681.3787314892300005.03815186730653.600953758
2299946.01037402729930.5106759522300667.36454079729040.753731504
 2301335.7673185728894.9203981762301863.54509631728249.087064818
2302811.46176299727999.0870648472302913.02426296 727076.34400928
2304628.30204077725285.5453981762304985.94092961723385.371787056
2305915.62842965722404.4690092952304919.10065186719348.913453728
2305063.19787404718668.3578981762304698.61454077717072.871787056
2305004.17009631716907.9412314892304798.44092962716642.316231504

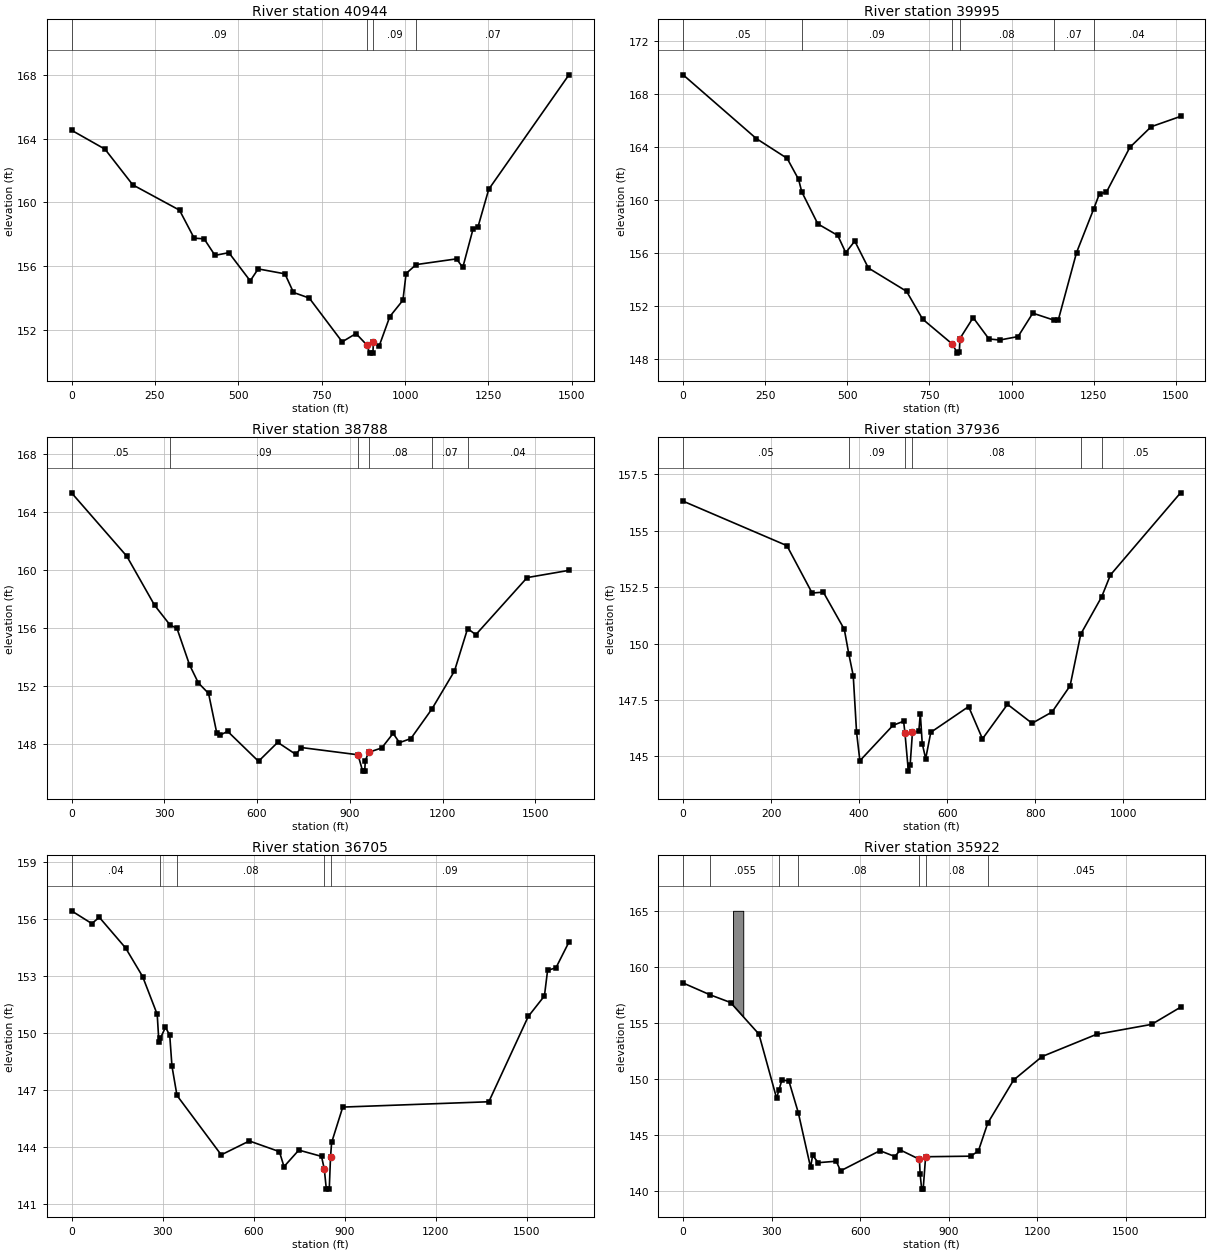
Type RM Length L Ch R = 1 ,40944   ,908.35,948.22,899.18
XS GIS Cut Line= 6
 2287547.1561704  738557.9796151 2287614.2870716  738346.5172765
 2287761.9750541  738024.2889511 2287855.9583157   737789.330797
 2288127.8384653  737393.2584803  2288228.534817  737242.2139528
#Sta/Elev= 30
       0  164.53  100.32  163.34  183.57   161.1  323.71  159.51  367.69  157.75
  397.44  157.71  430.08  156.67  471.62  156.84  535.67  155.07  559.59  155.82
  639.77  155.51  665.45  154.34  712.62  153.99  811.46  151.24  852.86  151.76
   884.5  151.06  894.32  150.53  903.52  150.53  905.08  151.23  921.83  150.95
  954.32  152.83  993.52  153.85 1003.04  155.53 1033.04  156.09 1154.18  156.45
    1173  155.91 1203.84  158.33 1218.21  158.43 1250.82  160.82 1491.32  168.01
#Mann= 4 ,-1 , 0
       0     .09       0   884.5     .05       0  905.08     .09       0
 1033.04     .07       0
Bank Sta=884.5,905.08
XS Rating Curve= 0 ,0
Exp/Cntr=0.3,0.1

Type RM Length L Ch R = 1 ,39995   ,1040.57,1207.98,1012.48
XS GIS Cut Line= 6
 2288473.5626061  738675.4586921 2288517.1976919  738437.1439931
 2288570.9024128  738245.8209248  2288819.286747   737785.974252
 2289071.0276263  737443.6066562 2289087.8103516   737319.414489
#Sta/Elev= 30
       0  169.43  222.61  164.62  316.65  163.12  351.56  161.53  361.02   160.6
  410.07  158.17  470.73   157.3  495.02     156  522.58  156.87  563.97  154.84
  680.18  153.08  729.02  150.98  819.26   149.1  835.01  148.41  840.98  148.53
  842.68  149.51  882.98  151.09  931.04  149.48  964.06   149.4 1019.66  149.66
  1064.5  151.43  1130.3  150.89  1142.1  150.91 1197.66     156 1249.63  159.28
 1267.64  160.46 1288.29  160.55 1359.96  163.95 1424.89  165.51 1514.34  166.29
#Mann= 6 ,-1 , 0
       0     .05       0  361.02     .09       0  819.26     .05       0
  842.68     .08       0  1130.3     .07       0 1249.63     .04       0
Bank Sta=819.26,842.68
XS Rating Curve= 0 ,0
Exp/Cntr=0.3,0.1

Type RM Length L Ch R = 1 ,38788   ,767.43,851.04,784.93
XS GIS Cut Line= 6
 2289191.8632484  738806.3639493 2289517.4481189  738423.7178128
 2289631.5706509  738286.0994655 2289705.4146421  738121.6287577
 2289806.1109938    737963.87114 2290044.4256929  737457.0328364
#Sta/Elev= 30
       0  165.34  178.64  160.96   268.8  157.56  318.69   156.2  340.96  155.97
  381.59  153.45  410.12   152.2  443.18  151.47  469.88  148.72   478.6  148.57
   504.9  148.85  604.69  146.78  666.83  148.09  725.17  147.26  743.63  147.73
  926.36  147.23  941.53   146.1  948.15   146.1  950.04  146.81  960.55   147.4
 1003.07   147.7 1040.05  148.71 1060.59  148.07 1097.39  148.35 1165.35  150.39
 1238.47  153.02 1281.02  155.96 1307.38  155.53 1473.49  159.48 1608.71  159.98
#Mann= 6 ,-1 , 0
       0     .05       0  318.69     .09       0  926.36     .05       0
  960.55     .08       0 1165.35     .07       0 1281.02     .04       0
Bank Sta=926.36,960.55
XS Rating Curve= 0 ,0
Exp/Cntr=0.3,0.1

Type RM Length L Ch R = 1 ,37936   ,1124.39,1230.99,912.07
BEGIN DESCRIPTION:
Surveyed Section
END DESCRIPTION:
XS GIS Cut Line= 6
 2290004.2045824  738825.6836065 2290172.6108846  738707.5478423
    2290464.3913      738392.171 2290531.2620217  738227.9757263
 2290605.9614741  738100.5193849 2290661.1575954  737942.0276655
#Sta/Elev= 30
       0  156.31  235.71  154.34  293.02  152.24 318.433  152.28 366.145  150.63
 376.328  149.54 386.406  148.58 393.953  146.07 401.493  144.81 476.777  146.38
  500.83  146.56  503.85  146.04 511.641  144.35 515.676  144.63 520.941  146.08
 535.322  146.11 538.748   146.9 543.139  145.57 550.954   144.9 562.598  146.07
  648.45  147.21  679.92  145.78  736.77  147.31  792.61  146.47     838  146.97
  878.99  148.13  903.21  150.42  950.67  152.07  970.57  153.04 1129.87  156.68
#Mann= 6 ,-1 , 0
       0     .05       0 376.328     .09       0  503.85     .05       0
 520.941     .08       0  903.21     .07       0  950.67     .05       0
Bank Sta=503.85,520.941
XS Rating Curve= 0 ,0
Exp/Cntr=0.3,0.1

Type RM Length L Ch R = 1 ,36705   ,790.22,783.04,757.88
XS GIS Cut Line= 6
 2291283.2197143  739328.8508702 2291289.9328044  739251.6503339
 2291296.6458945  738915.9958282 2291346.9940704  738640.7591335
 2291336.9244352  738305.1046278 2291444.3338771  737704.2830626
#Sta/Elev= 30
       0  156.41   66.82  155.74   91.45  156.07  178.08  154.46  234.18  152.96
  282.35  150.97  287.89  149.51  293.08  149.73  309.57  150.29  323.58  149.88
  330.93  148.25   347.5  146.71  493.23  143.59  585.92  144.32     685  143.76
  700.13  142.97  749.02  143.84  823.74  143.51  832.86  142.85  839.64  141.79
  849.29  141.79  853.43  143.48  857.12  144.24  893.77   146.1 1375.13  146.38
 1505.05  150.86 1558.34  151.94 1568.73  153.28 1596.44  153.42 1639.17  154.77
#Mann= 5 ,-1 , 0
       0     .04       0  293.08    .035       0   347.5     .08       0
  832.86     .05       0  853.43     .09       0
#XS Ineff= 2 , 0
       0                    1088       0
Permanent Ineff=
       F       F
Bank Sta=832.86,853.43
XS Rating Curve= 0 ,0
Exp/Cntr=0.3,0.1

Type RM Length L Ch R = 1 ,35922   ,619.23,543.41,439.9
XS GIS Cut Line= 6
 2292172.4752591  739266.2106222 2292138.9098085  738927.1995714
  2292112.057448  738557.9796151 2292085.2050876  738326.3780062
 2292028.1438216  738084.7067621 2291927.4474699  737601.3642738
#Sta/Elev= 30
       0  158.56   91.05  157.51  160.67  156.82  256.95     154  316.83  148.28
  325.24  149.05  334.76   149.9  358.45  149.82  390.49  146.98   431.9  142.12
  439.04  143.19  457.87  142.53  519.03  142.66  533.67   141.8  667.07   143.6
  717.56  143.08  736.34  143.66  801.04  142.83  803.21  141.55  808.59  140.17
  813.68  140.17  821.95  143.06  974.47  143.11 1000.76  143.57 1032.54  146.06
 1120.46  149.91 1216.74     152 1401.17  153.98 1588.07  154.87 1686.05   156.4
#Mann= 7 ,-1 , 0
       0     .04       0   91.05    .055       0  325.24    .035       0
  390.49     .08       0  801.04     .05       0  821.95     .08       0
 1032.54    .045       0
#Block Obstruct= 1 ,-1
  169.22  203.77     165
Bank Sta=801.04,821.95
XS Rating Curve= 0 ,0
Exp/Cntr=0.3,0.1

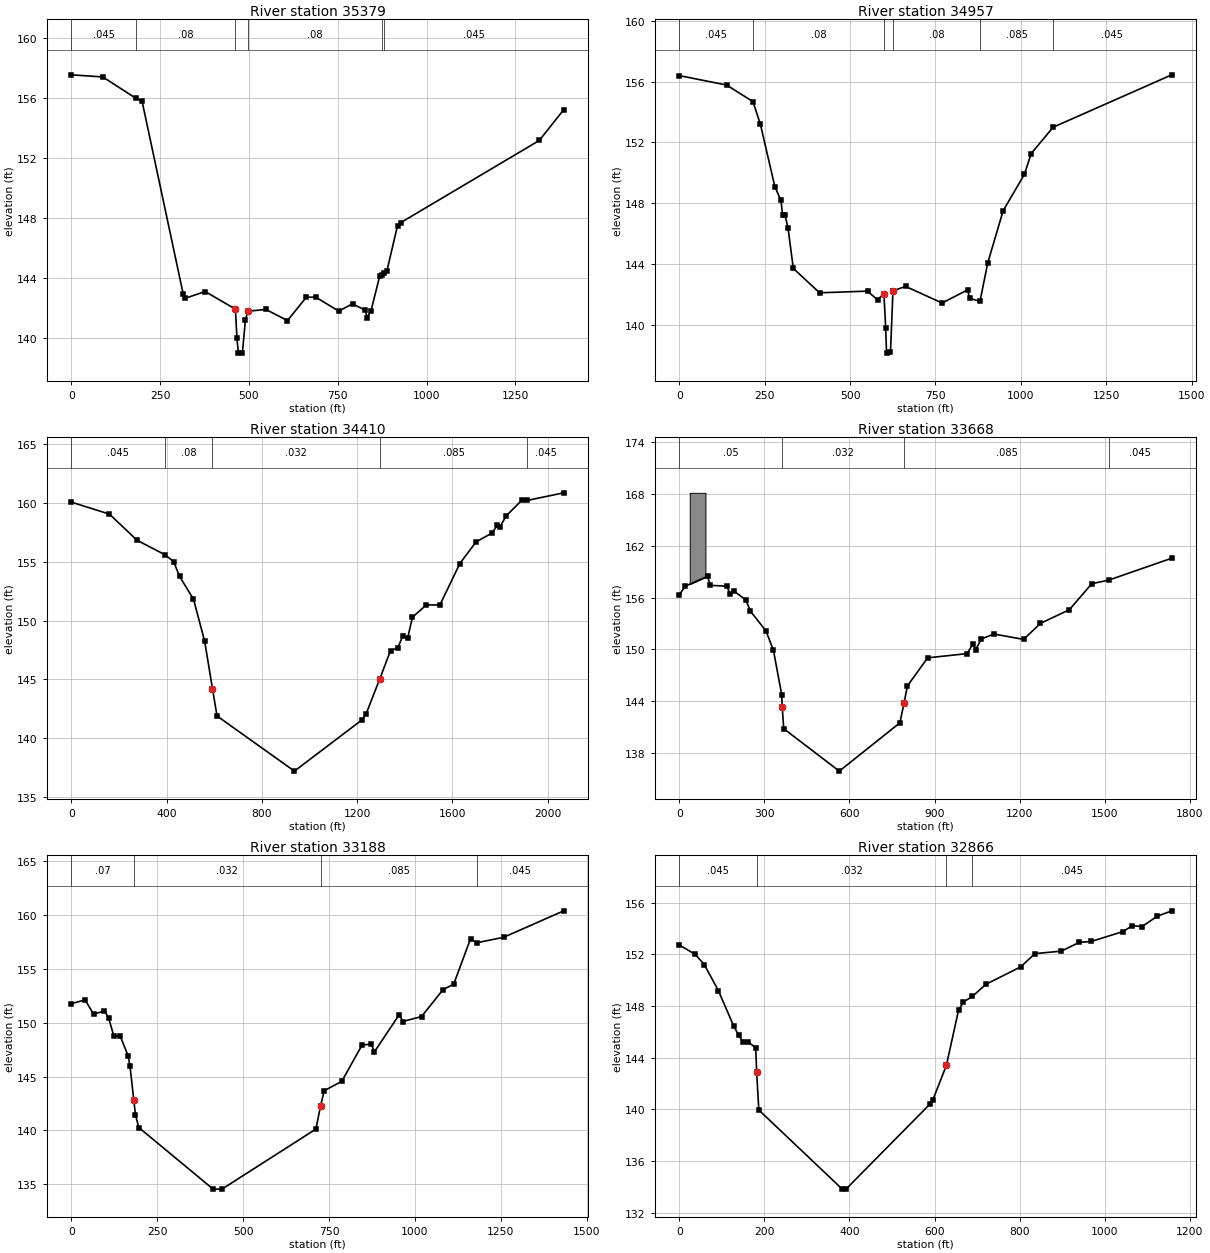
Type RM Length L Ch R = 1 ,35379   ,396.36,422.36,345.93
XS GIS Cut Line= 6
 2292860.5669957  738682.1717822 2292588.6868461  738359.9434567
  2292404.076868  738084.7067621 2292377.2245075  738031.0020411
 2292246.3192503   737906.809874 2292018.0741865  737587.9380936
#Sta/Elev= 30
       0  157.55   88.51  157.41  182.38  155.98  199.02  155.81     315  142.95
  320.35  142.67  376.83  143.12  461.91  141.95  466.12  140.04   470.2  139.02
  481.44  139.02  490.03  141.23  497.12  141.81  547.35  141.93   608.4  141.19
  661.39  142.74  687.71  142.75  752.51  141.82  791.41   142.3   827.2  141.88
  832.38  141.39  843.39  141.83   868.1  144.16  874.22  144.25  879.76  144.33
  887.89  144.46  918.06  147.51   927.2  147.71 1317.11  153.18 1385.88  155.23
#Mann= 6 ,-1 , 0
       0    .045       0  182.38     .08       0  461.91     .05       0
  497.12     .08       0  874.22    .085       0  879.76    .045       0
Bank Sta=461.91,497.12
XS Rating Curve= 0 ,0
Exp/Cntr=0.3,0.1

Type RM Length L Ch R = 1 ,34957   ,564.28,546.84,457.51
XS GIS Cut Line= 6
 2293063.8397366  738466.7473726 2292884.2634236   738124.581695
 2292784.7684393  738003.2463484 2292326.1208289  737605.2664113
 2292192.6519476  737469.3708231 2292112.5706188  737408.7031497
#Sta/Elev= 30
       0  156.39  138.49  155.77  215.82  154.68  237.65  153.18  279.77   149.1
  297.76  148.19  302.38  147.25  309.66  147.21  318.32  146.39  333.82  143.73
  410.77  142.13  551.13  142.24  580.35  141.67  599.01  142.06  604.25  139.84
  606.73  138.17  618.29  138.22  625.62  142.27  626.54  142.27  662.52  142.55
  769.42  141.46     844  142.32  849.89  141.77  880.27  141.57  903.16   144.1
  948.16  147.52 1010.49  149.91  1030.1  151.27  1094.5     153 1441.65  156.44
#Mann= 6 ,-1 , 0
       0    .045       0  215.82     .08       0  599.01     .05       0
  626.54     .08       0  880.27    .085       0  1094.5    .045       0
Bank Sta=599.01,626.54
XS Rating Curve= 0 ,0
Exp/Cntr=0.3,0.1

Type RM Length L Ch R = 1 ,34410   ,874.18,741.34,663.47
XS GIS Cut Line= 6
2293760.30462639738175.542540625 2293452.1128459737913.458191842
2292762.92807686737418.4099774812292381.93508834737180.592698023
2292124.70415342737056.8306444442292068.88989398737001.016384974
#Sta/Elev= 30
       0  160.08  160.28  159.06  275.79  156.84  392.77  155.61  429.59  155.03
  454.34  153.77  512.96  151.83  559.91  148.25  592.67  144.22  611.72   141.9
  936.59  137.21 1218.57  141.54  1236.9  142.04 1294.28  145.02    1340  147.45
 1370.44  147.69 1392.32  148.73 1412.02  148.53 1432.25   150.3  1490.5  151.34
 1547.42  151.34 1631.19  154.86 1698.78  156.69 1765.99  157.45  1788.8  158.12
 1798.49  157.94 1825.93  158.92 1893.29  160.28 1915.07  160.23 2067.21  160.87
#Mann= 5 ,-1 , 0
       0    .045       0  392.77     .08       0  592.67    .032       0
 1294.28    .085       0 1915.07    .045       0
Bank Sta=592.67,1294.28
XS Rating Curve= 0 ,0
Exp/Cntr=0.3,0.1

Type RM Length L Ch R = 1 ,33668   ,562.39,480.76,459.68
XS GIS Cut Line= 6
2293832.70438688 737064.369231062293423.46682717736971.752309665
2292953.92057443736829.5961046812292747.14791264736790.826230615
2292469.29714842736603.4385059032292202.21579359736523.744875833
#Sta/Elev= 30
       0  156.33   21.24  157.33   99.79  158.48  108.94  157.43  167.69  157.33
   179.8  156.38  191.78  156.78  234.55  155.75  250.78  154.43  305.19  152.18
  331.93  149.91  361.03  144.78     363   143.3   368.2  140.83  564.14  135.91
  777.91  141.51  792.52  143.83  804.26  145.78  875.54  149.03 1014.52  149.52
 1035.81  150.67 1044.43  149.97 1065.25  151.22 1109.12  151.79 1213.89  151.17
 1273.26  153.02 1375.31  154.61 1454.19  157.62 1514.51  158.04 1736.03  160.57
#Mann= 4 ,-1 , 0
       0     .05       0  361.03    .032       0  792.52    .085       0
 1514.51    .045       0
#Block Obstruct= 1 ,-1
   36.86    92.3 168.143
Bank Sta=363,792.52
XS Rating Curve= 0 ,0
Exp/Cntr=0.3,0.1

Type RM Length L Ch R = 1 ,33188   ,281.86,322.02,373.71
XS GIS Cut Line= 6
2293656.08607163736441.8973638862293421.31294528736474.205592275
2293141.30829911736441.8973638862292839.76483406736400.973607913
2292475.75879407736431.1279544232292232.37014012 736403.12748982
#Sta/Elev= 30
       0  151.77   40.15  152.13   64.85   150.8    96.6   151.1   108.6  150.46
  123.86  148.77  142.53  148.76  165.22  146.94  170.77  145.99   181.9  142.83
  186.69  141.46  196.47  140.27  412.83  134.55  438.48  134.55  711.92  140.13
  725.36  142.27  736.11   143.7  787.13  144.56  846.14  147.93  873.08  148.02
  882.06   147.3  954.74  150.77  964.64  150.12 1019.21  150.58 1081.89  153.08
 1112.87  153.59 1162.01  157.82 1179.83  157.43 1258.81  157.95 1433.13   160.4
#Mann= 4 ,-1 , 0
       0     .07       0   181.9    .032       0  725.36    .085       0
 1179.83    .045       0
Bank Sta=181.9,725.36
XS Rating Curve= 0 ,0
Exp/Cntr=0.3,0.1

Type RM Length L Ch R = 1 ,32866   ,163.01,331.12,349.08
XS GIS Cut Line= 6
2293531.16092183736295.4333951322293354.54260658736189.893182367
2293076.69184232736120.9689617752292831.14930648735996.043811962
2292721.30132991735970.197229251 2292445.6044476735983.120520592
#Sta/Elev= 30
       0  152.72   37.51  151.99   58.83   151.2   92.02  149.18  128.28  146.42
  139.77  145.73  149.55  145.23  161.37  145.22  179.62  144.77  181.92  142.86
  186.96  139.95  383.09  133.83  391.84  133.83  588.93   140.4  595.68   140.7
  628.05  143.43   656.3  147.66  667.82  148.31  689.05  148.74  720.89  149.68
  802.81  151.03  835.86  152.05  897.64  152.24   940.3  152.92  968.27  152.99
 1042.31  153.75  1065.1  154.21 1087.68  154.14 1123.25  154.94 1157.47  155.36
#Mann= 4 ,-1 , 0
       0    .045       0  181.92    .032       0  628.05    .085       0
  689.05    .045       0
Bank Sta=181.92,628.05
XS Rating Curve= 0 ,0
Exp/Cntr=0.5,0.3

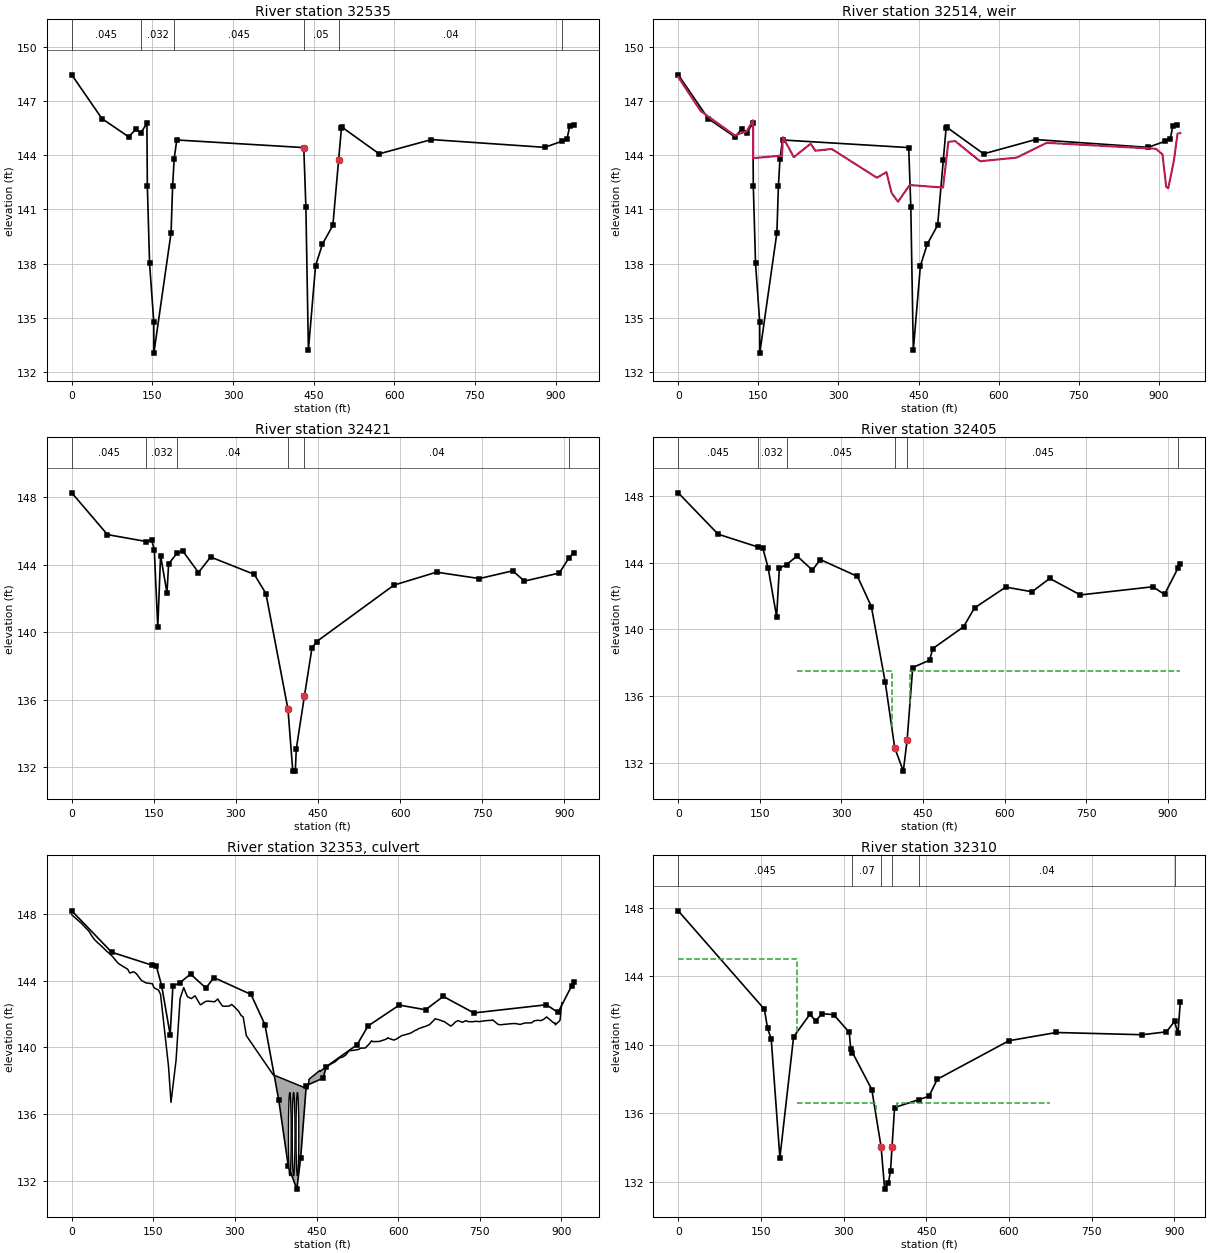
Type RM Length L Ch R = 1 ,32535   ,11.81,113.27,52.78
BEGIN DESCRIPTION:
Surveyed Section
END DESCRIPTION:
XS GIS Cut Line= 6
2293510.70408709736154.5716809932293430.34006579735981.908387706
2293191.45732775735864.5285825432293141.09170979735778.819019362
2293100.23795426735746.7196400022292808.42541456735605.190558255
#Sta/Elev= 30
       0  148.44   56.08  146.02  105.92  145.01  119.09  145.43  128.34  145.23
  139.77  145.75   140.6   142.3  144.76  138.01  152.61  134.75  152.75  133.05
  184.75  139.71  187.62  142.29  190.55  143.81  195.36 144.837  431.65 144.416
  435.54  141.14  440.23  133.21  453.53  137.88  466.38  139.08  485.78  140.12
  496.37  143.71  501.73  145.52  503.41  145.53  571.92  144.07  669.11  144.86
  879.95  144.43  912.23  144.77  921.39  144.89  926.37  145.61  934.08  145.64
#Mann= 6 ,-1 , 0
       0    .045       0  128.34    .032       0  190.55    .045       0
  431.65     .05       0  496.37     .04       0  912.23    .065       0
#XS Ineff= 2 , 0
       0     129     145     506       0     144
Permanent Ineff=
       F       F
Bank Sta=431.65,496.37
XS Rating Curve= 0 ,0
Exp/Cntr=0.5,0.3

Type RM Length L Ch R = 5 ,32514   ,,,
BEGIN DESCRIPTION:
Dam near Countryside Road
END DESCRIPTION:
IW Pilot Flow=0
#Inline Weir SE= 30
       0  148.32   42.26  146.43  106.15  145.08  128.24  145.32  140.22  145.93
  140.23 143.831   194.4 143.976  196.07  144.99  216.45  143.89     248  144.63
  256.78  144.24  287.36  144.34  372.04  142.75  390.02  143.06  399.55  141.91
  411.52  141.42  433.46 142.344  495.88 142.206  505.92  144.73   518.5  144.78
  565.29  143.66  633.53  143.86  690.25  144.68  894.66  144.35  906.82  144.04
  913.92  142.24  917.72  142.17  927.86  143.63  935.14  145.19  940.28  145.22
IW Dist,WD,Coef,Skew,MaxSub,Min_El,Is_Ogee,SpillHt,DesHd
20,2.8,2.6,0,0.98,, 0 ,,,0,0,
IW Gate Name Wd,H,Inv,GCoef,Exp_T,Exp_O,Exp_H,Type,WCoef,Is_Ogee,SpillHt,DesHd,#Openings
Gate #1     ,3.5,2.4,139.46,0.5,0,1,0.5, 0 ,3, 0 ,,, 2 ,0,0.8, 0 ,0.5,,0,0,0, 0
     448     463

Type RM Length L Ch R = 1 ,32421   ,7.79,16.07,12.17
XS GIS Cut Line= 6
 2293525.3618798  736150.1235621 2293450.0982569  735977.4827776
 2293332.5473406  735916.9615138 2293272.4140337  735785.4441521
 2293112.1878673  735692.7224723 2292875.5342076  735574.0076856
#Sta/Elev= 30
       0  148.27   65.21  145.79  136.22  145.38  146.15  145.47  150.78  144.87
  157.13  140.29  162.26  144.54  173.98  142.34  176.92  144.04  192.17  144.69
  202.72  144.82   231.5  143.54  253.65  144.46  333.43  143.43  354.72  142.29
  394.98  135.43  403.81  131.75  408.42  131.77  410.19  133.07  425.07  136.21
  438.77  139.04  447.41  139.44  588.54  142.79   666.4  143.56  744.73  143.18
   805.5  143.64  827.05  143.03  890.81  143.51  908.12   144.4   917.3  144.72
#Mann= 6 ,-1 , 0
       0    .045       0  136.22    .032       0  192.17     .04       0
  394.98    .068       0  425.07     .04       0  908.12    .065       0
#XS Ineff= 2 , 0
       0  253.65  144.46               0
Permanent Ineff=
       F       F
Bank Sta=394.98,425.07
XS Rating Curve= 0 ,0
Exp/Cntr=0.5,0.3

Type RM Length L Ch R = 1 ,32405   ,37,95.62,65.67
BEGIN DESCRIPTION:
Surveyed Section
END DESCRIPTION:
XS GIS Cut Line= 6
 2293536.8457593  736152.3676343 2293452.0579774  735969.4920264
    2293337.9462     735905.8051    2293298.6609     735789.3541
  2293036.972747  735629.7923094 2292897.0600756  735565.1015044
#Sta/Elev= 30
       0  148.19    73.3  145.71  146.75  144.94  155.33  144.89  165.16  143.71
  180.88  140.76  185.87  143.67  199.08  143.89  218.44   144.4  246.59  143.56
  261.16  144.19  329.51  143.18  355.02  141.37 380.562  136.83 397.945  132.91
 413.757  131.51 420.819   133.4 431.044  137.72  462.11  138.16  467.79  138.85
  524.43  140.16  544.61  141.29  602.07  142.54  650.42  142.26  682.85  143.06
  739.13  142.07  872.54  142.56   893.9   142.1  918.88  143.69  922.94  143.92
#Mann= 6 ,-1 , 0
       0    .045       0  146.75    .032       0  199.08    .045       0
 397.945    .057       0 420.819    .045       0  918.88    .065       0
#XS Ineff= 3 ,-1
       0  218.44   144.4  218.44 392.945  137.52 425.819  922.94  137.52
Permanent Ineff=
       F       F       F
Bank Sta=397.945,420.819
XS Rating Curve= 0 ,0
Exp/Cntr=0.5,0.3

Type RM Length L Ch R = 2 ,32353   ,,,
BEGIN DESCRIPTION:
Dirt Road to Countryside Road
END DESCRIPTION:
Bridge Culvert--1,0,-1,-1, 0
Deck Dist Width WeirC Skew NumUp NumDn MinLoCord MaxHiCord MaxSubmerge Is_Ogee
48,9,2.6,0, 179, 169, , , 0.95, 0, 1,1,,
       0    5.19   16.76   17.98   18.87   18.87   20.27   31.52    36.2   41.17
   47.88   54.24   54.24   60.34   63.21   70.76   75.73   75.73   84.49   85.89
   85.89   87.25   87.25  102.75  106.68  113.59  118.56  118.56  127.43  129.15
  130.98  136.25  148.17  148.17  151.13  151.13   159.4  163.21  163.21  177.77
  182.38  191.69  191.69   199.1  205.81  210.35  212.72  219.88  226.61  226.61
  235.02  235.02  236.75   245.5   245.5  249.37  262.74  268.43  270.97   276.8
  280.35  289.18  293.81  298.21  306.32  311.24  311.24  315.04  315.04 320.896
 370.347 434.092  436.17  436.68  436.68  456.01  456.01  457.18  458.08  458.08
  468.54  468.54  469.59  474.87  483.81  489.36  492.22  498.19  503.77  509.75
  515.57  526.86  526.86  529.66  530.44  539.51  547.12  551.19  553.44  553.44
  565.12  578.26  581.01  583.37  590.92  592.33  593.72  593.72  597.09  597.09
  606.49  613.77  619.46  622.81  631.23  631.23  635.13  636.88  645.48  652.93
  657.95  664.36  667.95  677.98  677.98  681.75  683.86  686.91   696.6  701.12
  704.81  704.81  709.99   718.3  724.48  728.73  736.95  741.37  749.83  754.42
  754.42  762.42  771.05  771.05  772.55  772.55  773.87  783.66  783.66  784.44
  787.69  787.69  797.42  797.42  809.02  812.68  815.27  816.11  824.67  826.66
  833.58  838.87  845.66  845.66  849.57  855.61  862.32  867.14  872.81  885.66
  885.66  887.71  887.71  888.48  888.48  889.05  897.47  900.83  900.85
  147.95   147.8  147.47  147.44   147.4   147.4  147.35  146.97  146.72  146.49
  146.27  146.09  146.09  145.89   145.8  145.59  145.42  145.42  145.07  145.04
  145.04     145     145  144.69  144.46  144.54  144.43  144.43  144.05  143.99
  143.97  143.87  143.82  143.82  143.58  143.58  143.44  143.18  143.18  138.89
  136.71  139.23  139.23  142.93  143.59  143.21  143.04  142.93   143.1   143.1
  142.62  142.62  142.56  142.75  142.75  142.78  142.74  142.91  142.76  142.49
  142.47  142.48  142.58  142.46  142.19  141.92  141.92  141.83  141.83  140.71
  138.36  137.51   138.1  138.11  138.11  138.62  138.62  138.57  138.61  138.61
  138.85  138.85  138.85  138.98  139.14   139.3  139.38  139.43  139.55  139.81
  139.82  139.88  139.88  139.93  139.96  139.97  140.22   140.4  140.35  140.35
  140.36   140.5  140.58  140.54  140.46  140.44  140.47  140.47  140.51  140.51
  140.71  140.77  140.83  140.86  141.02  141.02  141.07  141.12  141.22   141.3
  141.38  141.59  141.72  141.63  141.63  141.57  141.57   141.5  141.28  141.39
  141.52  141.52  141.61  141.51  141.61  141.55  141.54  141.57  141.55  141.58
  141.58  141.61  141.63  141.63  141.63  141.63  141.65  141.38  141.38  141.38
  141.36  141.36  141.39  141.39  141.43  141.43  141.44  141.43  141.38  141.41
  141.47  141.47  141.48  141.48  141.59  141.63  141.61  141.68  141.83  141.48
  141.48  141.46  141.46  141.47  141.47  141.36  141.62  142.68  142.68
                                                                                
                                                                                
                                                                                
                                                                                
                                                                                
                                                                                
                                                                                
                                                                                
                                                                                
                                                                                
                                                                                
                                                                                
                                                                                
                                                                                
                                                                                
                                                                                
                                                                                
                                                                        
       0    5.19   16.76   17.98   18.87   18.87   20.27   31.52    36.2   41.17
   47.88   54.24   54.24   60.34   63.21   70.76   75.73   75.73   84.49   85.89
   85.89   87.25   87.25  102.75  106.68  113.59  118.56  118.56  127.43  129.15
  130.98  136.25  148.17  148.17  151.13  151.13  212.72  219.88  226.61  226.61
  235.02  235.02  236.75   245.5   245.5  249.37  262.74  268.43  270.97   276.8
  280.35  289.18  293.81  298.21  306.32  311.24  311.24  315.04  315.04 320.896
 370.347 434.092  436.17  436.68  436.68  456.01  456.01  457.18  458.08  458.08
  468.54  468.54  469.59  474.87  483.81  489.36  492.22  498.19  503.77  509.75
  515.57  526.86  526.86  529.66  530.44  539.51  547.12  551.19  553.44  553.44
  565.12  578.26  581.01  583.37  590.92  592.33  593.72  593.72  597.09  597.09
  606.49  613.77  619.46  622.81  631.23  631.23  635.13  636.88  645.48  652.93
  657.95  664.36  667.95  677.98  677.98  681.75  683.86  686.91   696.6  701.12
  704.81  704.81  709.99   718.3  724.48  728.73  736.95  741.37  749.83  754.42
  754.42  762.42  771.05  771.05  772.55  772.55  773.87  783.66  783.66  784.44
  787.69  787.69  797.42  797.42  809.02  812.68  815.27  816.11  824.67  826.66
  833.58  838.87  845.66  845.66  849.57  855.61  862.32  867.14  872.81  885.66
  885.66  887.71  887.71  888.48  888.48  889.05  897.47  900.83  900.85
  147.95   147.8  147.47  147.44   147.4   147.4  147.35  146.97  146.72  146.49
  146.27  146.09  146.09  145.89   145.8  145.59  145.42  145.42  145.07  145.04
  145.04     145     145  144.69  144.46  144.54  144.43  144.43  144.05  143.99
  143.97  143.87  143.82  143.82  143.58  143.58  143.04  142.93   143.1   143.1
  142.62  142.62  142.56  142.75  142.75  142.78  142.74  142.91  142.76  142.49
  142.47  142.48  142.58  142.46  142.19  141.92  141.92  141.83  141.83  140.71
  138.36  137.51   138.1  138.11  138.11  138.62  138.62  138.57  138.61  138.61
  138.85  138.85  138.85  138.98  139.14   139.3  139.38  139.43  139.55  139.81
  139.82  139.88  139.88  139.93  139.96  139.97  140.22   140.4  140.35  140.35
  140.36   140.5  140.58  140.54  140.46  140.44  140.47  140.47  140.51  140.51
  140.71  140.77  140.83  140.86  141.02  141.02  141.07  141.12  141.22   141.3
  141.38  141.59  141.72  141.63  141.63  141.57  141.57   141.5  141.28  141.39
  141.52  141.52  141.61  141.51  141.61  141.55  141.54  141.57  141.55  141.58
  141.58  141.61  141.63  141.63  141.63  141.63  141.65  141.38  141.38  141.38
  141.36  141.36  141.39  141.39  141.43  141.43  141.44  141.43  141.38  141.41
  141.47  141.47  141.48  141.48  141.59  141.63  141.61  141.68  141.83  141.48
  141.48  141.46  141.46  141.47  141.47  141.36  141.62  142.68  142.68
                                                                                
                                                                                
                                                                                
                                                                                
                                                                                
                                                                                
                                                                                
                                                                                
                                                                                
                                                                                
                                                                                
                                                                                
                                                                                
                                                                                
                                                                                
                                                                                
                                                                        
BR Coef=-1 , 0 , 0 ,, 0 ,,,0.8,-1,,0,
WSPro=,,,, 1 ,,,, 0 ,,,, 0 ,,,,-1 ,-1 ,-1 , 0 , 0 , 0 , 0 , 0
Culvert=1,5,,23.17,0.024,0.5,1,2,1,132.3012,400.79,131.6679,370.92,Culvert #1  , 0 ,41.7
Culvert Bottom n=0.024
Culvert Bottom Depth=5
Culvert Depth Blocked=1
Culvert=1,5,,23.17,0.024,0.5,1,2,1,132.3012,407.79,131.6679,377.92,Culvert #2  , 0 ,41.7
Culvert Bottom n=0.024
Culvert Bottom Depth=5
Culvert Depth Blocked=1
Culvert=1,5,,23.17,0.024,0.5,1,2,1,132.3012,414.79,131.6679,384.92,Culvert #3  , 0 ,41.7
Culvert Bottom n=0.024
Culvert Bottom Depth=5
Culvert Depth Blocked=1
BC Design=,, 0 ,, 0 ,,,,,,
BC Use User HTab Curves=0
BC User HTab FreeFlow(D)= 0

Type RM Length L Ch R = 1 ,32310   ,27.33,50.65,46.38
BEGIN DESCRIPTION:
Surveyed Section
END DESCRIPTION:
XS GIS Cut Line= 6
 2293561.9380176  736142.5700804 2293490.4342326  735945.9346717
    2293353.4584     735743.9367 2293200.8854303  735667.1714577
 2293063.4256635  735562.1825019 2292961.6837888  735514.5586457
#Sta/Elev= 30
       0  147.82  156.22  142.08  161.97  140.98  168.71  140.33  184.41  133.41
  209.33  140.47  238.83  141.78  249.27   141.4  261.08  141.82  282.04  141.76
  310.32  140.73 312.966  139.73  316.07  139.55 351.166  137.39 368.053  134.04
 374.495  131.58 381.325  131.95 385.167  132.65  387.78  134.01 392.478  136.34
  437.21  136.81 454.827     137   469.9  137.99  599.95  140.24  685.94  140.72
  842.14  140.59   885.8  140.76  900.38  141.37  906.59  140.67  910.86  142.52
#Mann= 6 ,-1 , 0
       0    .045       0  316.07     .07       0 368.053     .05       0
  387.78     .09       0  437.21     .04       0  900.38     .09       0
#XS Ineff= 3 ,-1
       0     216     145     216 358.053  136.58  397.78     675  136.58
Permanent Ineff=
       F       F       F
Bank Sta=368.053,387.78
XS Rating Curve= 0 ,0
Exp/Cntr=0.5,0.3