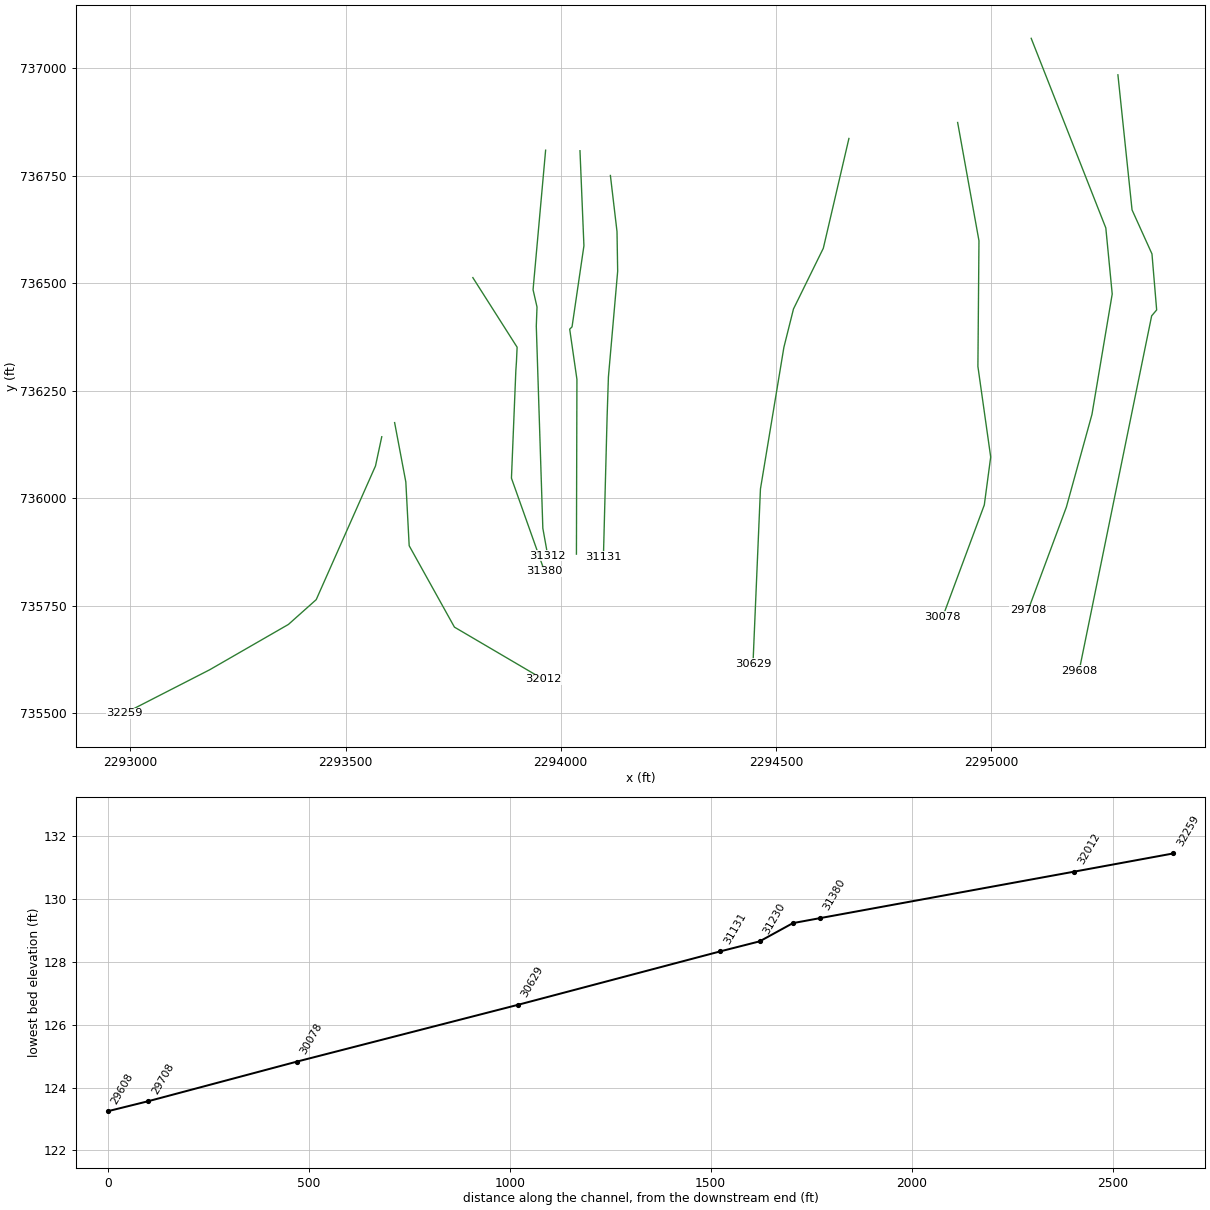
HEC-RAS study dtl_Bloomery_Swamp.prj: DTL_Bloomery_Swamp

--- dtl_Bloomery_Swamp.g01 (geometry) --- (continued)

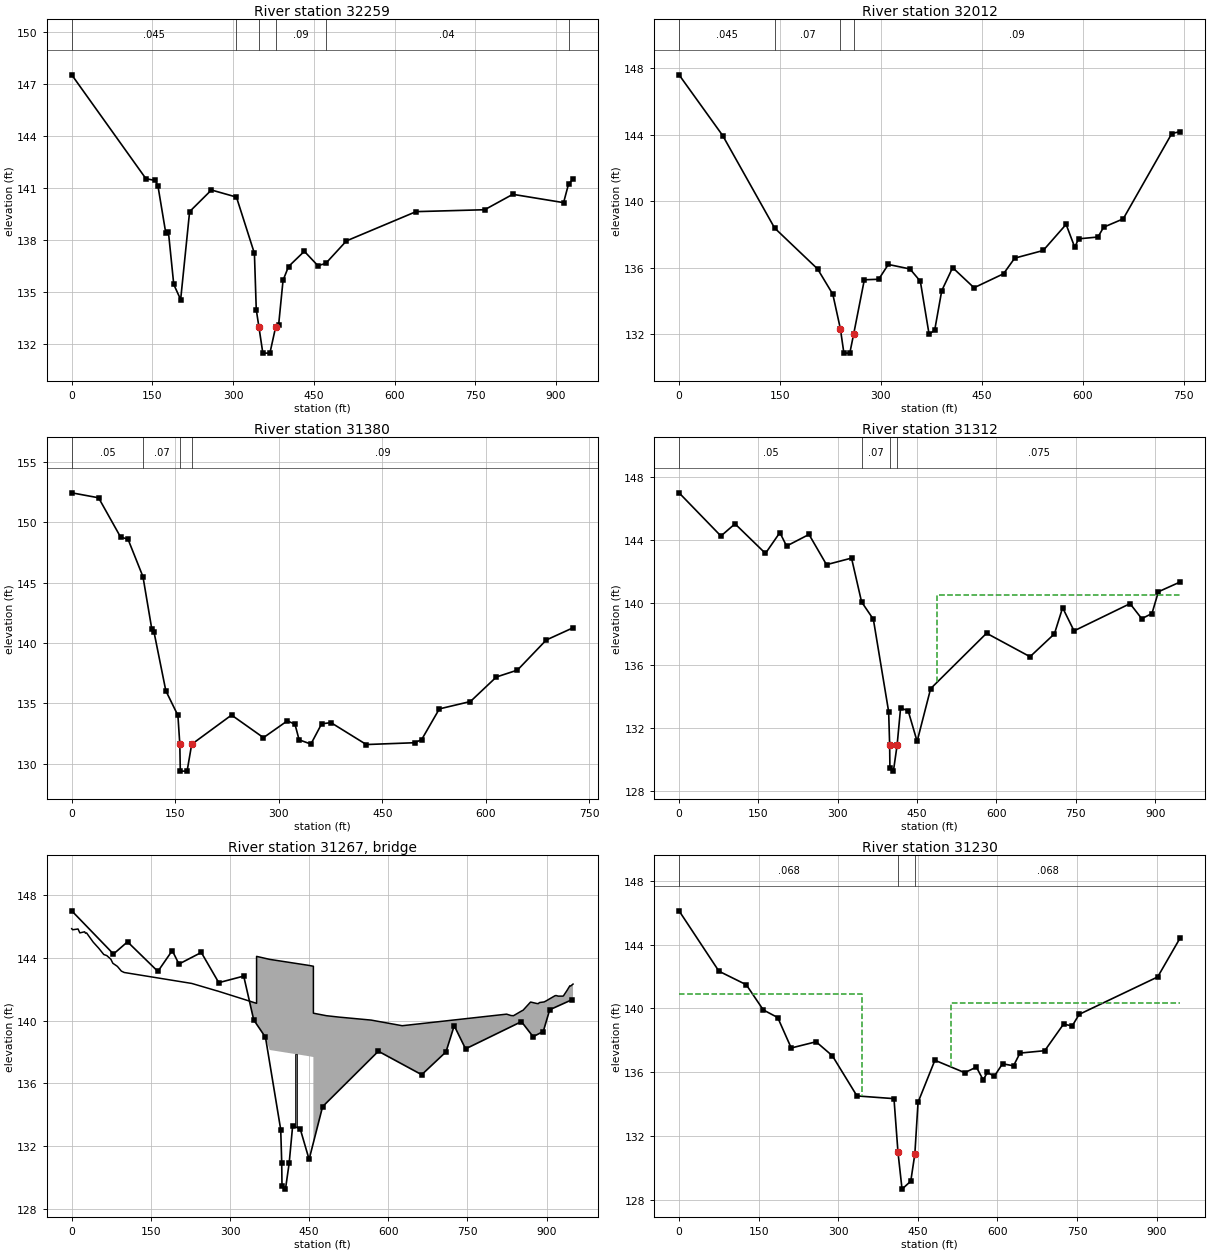
Type RM Length L Ch R = 1 ,32259   ,95.97,246.65,508.27
XS GIS Cut Line= 6
   2293584.01662  736143.0863343 2293569.4784023  736075.2413184
 2293431.6693372  735764.2630319  2293367.035069  735706.5893773
 2293184.0703716  735601.1858017 2292986.1900739  735499.7597194
#Sta/Elev= 30
       0  147.53   137.9  141.53  155.51  141.43  160.32  141.09  174.59  138.42
  179.59  138.48  189.54  135.43  202.38  134.55  219.02  139.63  259.54  140.88
  306.06  140.47  339.43  137.22  342.86  133.97   347.7  132.99  355.08  131.46
   368.2  131.46   378.7  132.94  384.48  133.11  392.61  135.66   402.8  136.46
  432.16  137.34  457.36  136.51  471.95  136.64  510.38  137.94  639.74  139.63
  767.23  139.74  819.45  140.63  913.85  140.15  923.12  141.23  931.41   141.5
#Mann= 6 ,-1 , 0
       0    .045       0  306.06     .07       0   347.7     .05       0
   378.7     .09       0  471.95     .04       0  923.12     .09       0
#XS Ineff= 2 , 0
       0  259.54             650       0
Permanent Ineff=
       F       F
Bank Sta=347.7,378.7
XS Rating Curve= 0 ,0
Exp/Cntr=0.3,0.1

Type RM Length L Ch R = 1 ,32012   ,417.32,632.33,561.58
XS GIS Cut Line= 5
2293613.91133346736175.9821378442293639.94439721736038.006900176
2293647.75431629735889.6184370522293752.93115792735700.345374808
 2293959.3151437735579.094783142
#Sta/Elev= 30
       0  147.61   64.83  143.96     142   138.4  205.86  135.94  228.47  134.42
  239.68  132.35  244.95  130.88  253.71  130.88  259.43  132.02  275.32  135.29
  296.66  135.32  310.93  136.21  343.09  135.94  358.53   135.2  371.55  132.01
  379.91  132.27  390.32  134.63  406.52  136.02  438.33  134.81  482.13  135.65
  498.74  136.59  541.08  137.05  575.14  138.62  588.01  137.24   593.6  137.75
  622.51  137.86  630.88  138.45  659.97  138.95  732.19  144.08   744.9   144.2
#Mann= 4 ,-1 , 0
       0    .045       0     142     .07       0  239.68     .05       0
  259.43     .09       0
#XS Ineff= 2 , 0
       0                     530       0
Permanent Ineff=
       F       F
Bank Sta=239.68,259.43
XS Rating Curve= 0 ,0
Exp/Cntr=0.3,0.1

Type RM Length L Ch R = 1 ,31380   ,104.52,67.84,116.89
XS GIS Cut Line= 6
 2293795.7254913  736513.1401591 2293898.6207588  736351.3089031
 2293897.1308016  736318.5298439 2293895.6408444  736296.1804855
 2293885.4550255  736046.7490372 2293962.2531569  735830.4343003
#Sta/Elev= 30
       0  152.43   38.89  152.02   70.85  148.76   81.49   148.6  103.19  145.49
  116.01  141.15  119.12  140.93  136.31  136.05   153.8  134.01  156.55  131.64
  157.27   129.4  167.11   129.4  173.77  131.62   231.5  134.04  277.73  132.17
   312.3  133.56  323.38  133.28  329.39  131.99  346.47  131.64  362.07  133.32
  375.61  133.41  426.76   131.6  496.62  131.75  506.78     132  532.51  134.55
  577.52  135.16  615.12  137.19  645.64  137.76  687.38  140.25  726.17  141.26
#Mann= 4 ,-1 , 0
       0     .05       0  103.19     .07       0  156.55     .05       0
  173.77     .09       0
Bank Sta=156.55,173.77
XS Rating Curve= 0 ,0
Exp/Cntr=0.5,0.3

Type RM Length L Ch R = 1 ,31312   ,108.31,82.63,84.39
BEGIN DESCRIPTION:
Surveyed Section
END DESCRIPTION:
XS GIS Cut Line= 6
 2293964.8799979  736809.5230458    2293935.6949     736485.0118
     2293944.863     736444.8072    2293943.1873     736400.3793
 2293958.4132503  735930.2718712 2293969.9329701  735866.2734283
#Sta/Elev= 30
       0  147.02   79.14  144.26  105.77  145.04  163.31  143.15  190.55  144.48
  203.22  143.62  245.59  144.36  278.73  142.43 326.016  142.85 344.998  140.05
 367.282  138.94 396.167  133.04 398.039  130.94 398.566  129.47 405.169  129.24
 412.139  130.89 418.748  133.27 433.025   133.1 449.968  131.14 475.536  134.51
  581.24  138.05  663.42  136.55  709.49  138.01  725.01  139.68  746.58   138.2
  852.44  139.94  874.59  138.98  893.86  139.31  906.07   140.7  947.54  141.33
#Mann= 4 ,-1 , 0
       0     .05       0 344.998     .07       0 398.039     .05       0
 412.139    .075       0
#XS Ineff= 2 , 0
       0     320  141.11     488       0  140.48
Permanent Ineff=
       F       F
Bank Sta=398.039,412.139
XS Rating Curve= 0 ,0
Exp/Cntr=0.5,0.3

Type RM Length L Ch R = 3 ,31267   ,,,
BEGIN DESCRIPTION:
Lamm Road (SR 1001) High cord represents concrete barrier.
END DESCRIPTION:
Bridge Culvert--1,0,-1,-1, 0
Deck Dist Width WeirC Skew NumUp NumDn MinLoCord MaxHiCord MaxSubmerge Is_Ogee
23.5,28,2.6,0, 60, 59, , , 0.98, 0, 1,1,,
       0    1.64   11.93   15.37   24.44   26.04   28.11   40.71   51.43   60.72
   66.47   74.12   77.93   86.56   94.03   99.59 227.614 274.932 275.296 350.394
 350.396 375.087 448.367 458.096 458.097 482.662 506.759 567.548 626.468  824.41
  832.75  837.38  852.61  852.61  855.56  868.86  868.86  869.64  870.14  870.14
  881.58  881.58  884.24  884.24  886.77   895.4  899.49  915.75  915.75  918.02
  922.25  930.85  932.12  932.12   938.8   938.8  944.22  944.22  945.86  950.26
  145.88  145.81  145.86  145.61  145.68  145.59  145.61  145.02  144.62  144.23
  144.16  143.93  143.67  143.47  143.17  143.08  142.38  141.91  141.91  141.11
  144.11  143.92  143.54  143.48  140.48  140.32  140.23  140.04  139.68  140.42
  140.33  140.32  140.62  140.62  140.67  141.16  141.16  141.19  141.19  141.19
   141.1   141.1  141.09  141.09  141.16   141.2  141.27  141.59  141.59  141.61
  141.57  141.57  141.59  141.59  141.93  141.93  142.23  142.23  142.22  142.34
                                                                                
                                                                                
  138.31  138.13  137.74  137.68
                                                                                
                                                                                
                                                                                
       0    1.64   11.93   15.37   24.44   26.04   28.11   40.71   51.43   60.72
   66.47   74.12   77.93   86.56   94.03   99.59 227.614 274.932 275.296 350.396
 375.084 375.087 448.367 482.662 482.663 506.759 567.548 626.468  824.41  832.75
  837.38  852.61  852.61  855.56  868.86  868.86  869.64  870.14  870.14  881.58
  881.58  884.24  884.24  886.77   895.4  899.49  915.75  915.75  918.02  922.25
  930.85  932.12  932.12   938.8   938.8  944.22  944.22  945.86  950.26
  145.88  145.81  145.86  145.61  145.68  145.59  145.61  145.02  144.62  144.23
  144.16  143.93  143.67  143.47  143.17  143.08  142.38  141.91  141.91  141.11
  140.92  143.92  143.54  143.32  140.32  140.23  140.04  139.68  140.42  140.33
  140.32  140.62  140.62  140.67  141.16  141.16  141.19  141.19  141.19   141.1
   141.1  141.09  141.09  141.16   141.2  141.27  141.59  141.59  141.61  141.57
  141.57  141.59  141.59  141.93  141.93  142.23  142.23  142.22  142.34
                                                                                
                                                                                
          138.13  137.74  137.52
                                                                                
                                                                                
                                                                        
Pier Skew, UpSta & Num, DnSta & Num=  ,425.6, 2 ,450.16, 2 , 0 , 0 , 0 ,,
     3.7     3.7
  131.14  138.31
     3.7     3.7
  131.14  138.31
Abutment Skew #Up #Dn= , 2 , 2
   350.4   359.6
  138.12     128
  375.09  384.29
  138.12     128
Abutment Skew #Up #Dn= , 2 , 2
   446.1   458.1
   129.3  137.68
  470.66  482.66
   129.3  137.52
BR Coef=-1 , 0 , 0 ,, 0 ,,,0.8,0,,0,
WSPro=,,,, 1 ,,,, 0 ,,,, 0 ,,,,-1 ,-1 ,-1 , 0 , 0 , 0 , 0 , 0
BC Design=,, 0 ,, 0 ,,,,,,
BC Use User HTab Curves=0
BC User HTab FreeFlow(D)= 0

Type RM Length L Ch R = 1 ,31230   ,92.27,98.13,90.22
BEGIN DESCRIPTION:
Surveyed Section
END DESCRIPTION:
XS GIS Cut Line= 6
 2294044.7365948  736808.2752865 2294053.9032243  736587.0949659
    2294026.2768     736398.6019    2294020.8494     736393.2868
    2294037.6397     736276.5761 2294036.4913506  735870.1133349
#Sta/Elev= 30
       0  146.13   75.15  142.34  126.73  141.49  158.75  139.91  185.98  139.43
  211.41  137.52  258.24  137.91  288.95  137.03 335.306  134.51  405.07  134.34
 412.662  130.96  420.26  128.66 436.735  129.16 444.412  130.87 450.432  134.11
 482.171  136.75 538.455  135.97  560.32  136.32  573.13  135.52  581.33  135.99
  594.08  135.74  609.66  136.53   630.4   136.4  642.53   137.2  689.21  137.35
   724.7  139.02   740.9   138.9  754.11  139.63  902.07  141.98  944.81  144.45
#Mann= 3 ,-1 , 0
       0    .068       0 412.662    .065       0 444.412    .068       0
#XS Ineff= 2 , 0
       0     345  140.92     512       0  140.32
Permanent Ineff=
       F       F
Bank Sta=412.662,444.412
XS Rating Curve= 0 ,0
Exp/Cntr=0.5,0.3

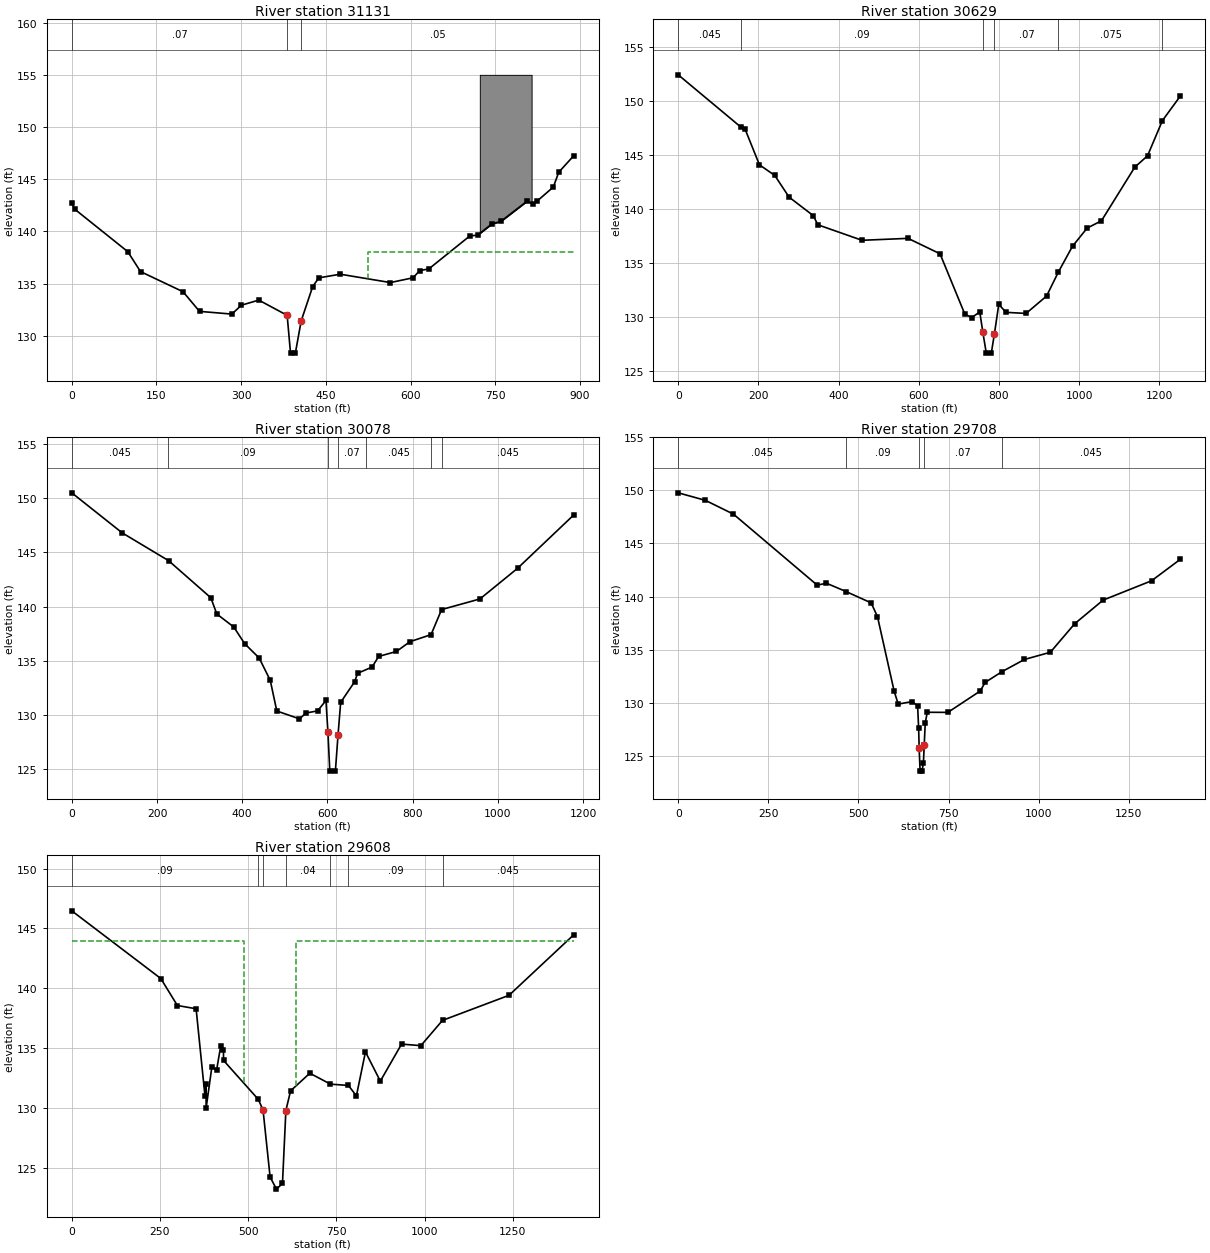
Type RM Length L Ch R = 1 ,31131   ,493.79,502.84,529.01
XS GIS Cut Line= 6
 2294115.4387712  736750.6972149 2294130.8015427  736620.1136573
 2294132.3378198  736527.9370285 2294110.8299397  736282.1326849
 2294107.7573855  736188.4197789 2294099.2098246  735863.7134906
#Sta/Elev= 30
       0  142.73    4.95  142.14   99.15  138.06  121.75  136.15  197.05  134.22
  226.17  132.34  283.45  132.08  300.36  132.93  331.14  133.42  381.38  131.96
  387.33  128.34  395.89  128.34  406.23  131.43  426.54  134.71  437.39  135.55
  475.43   135.9  564.18   135.1  604.54  135.56  615.97  136.25  632.08   136.4
   704.7  139.56  718.68  139.65  743.89  140.72  759.49  140.95     806  142.89
   816.2  142.64  823.22  142.87  852.66  144.25  862.25  145.67     889  147.26
#Mann= 3 ,-1 , 0
       0     .07       0  381.38     .05       0  406.23     .05       0
#XS Ineff= 2 , 0
       0     175          524.98       0     138
Permanent Ineff=
       F       F
#Block Obstruct= 1 ,-1
  722.49  814.19     155
Bank Sta=381.38,406.23
XS Rating Curve= 0 ,0
Exp/Cntr=0.3,0.1

Type RM Length L Ch R = 1 ,30629   ,555.58,550.38,621.03
XS GIS Cut Line= 6
 2294669.8314907  736836.7498624 2294610.3685282  736581.5546482
 2294540.9950719  736440.3301121 2294518.6964609  736351.1356683
 2294464.1887453  736021.6117509 2294446.8453812  735615.2815069
#Sta/Elev= 30
       0  152.44  157.45  147.56  166.95  147.39  202.54   144.1   240.9  143.11
  276.58   141.1  337.12  139.38  348.13  138.54  458.53   137.1  573.31  137.28
  653.12  135.85  714.83  130.27  731.89  129.93  752.31  130.46  759.92  128.58
  768.53  126.64  781.05  126.64  788.88  128.44  799.65  131.16  817.86  130.42
  867.72  130.32  918.91  131.93  948.66  134.18  983.65  136.55 1020.09  138.23
 1055.89  138.91 1139.01  143.88 1170.74  144.93    1208   148.2 1252.59  150.47
#Mann= 6 ,-1 , 0
       0    .045       0  157.45     .09       0  759.92     .05       0
  788.88     .07       0  948.66    .075       0    1208    .045       0
#XS Ineff= 2 , 0
       0  573.31  137.28               0
Permanent Ineff=
       F       F
Bank Sta=759.92,788.88
XS Rating Curve= 0 ,0
Exp/Cntr=0.3,0.1

Type RM Length L Ch R = 1 ,30078   ,312.53,369.72,303.08
XS GIS Cut Line= 6
 2294922.5490815   736873.914214 2294972.1015503  736598.8980123
 2294969.6239268  736306.5384464 2294999.3554081  736095.9404541
 2294984.4896675  735984.4473993 2294887.8623533  735724.2969382
#Sta/Elev= 30
       0  150.48  118.32  146.79  227.14  144.23  326.27  140.81  340.39  139.31
  380.24  138.11  405.61  136.58  439.68  135.26   465.7   133.2  481.12  130.37
   534.2  129.65  549.97  130.19  576.64  130.38  596.47  131.34  601.08   128.4
  605.45  124.83  618.57  124.83  624.78  128.17  630.99  131.17  663.43  133.05
  670.79  133.85  704.62  134.42  720.13   135.4  761.86  135.86  793.52  136.76
  843.05  137.41  867.79  139.72  957.82   140.7 1045.97  143.52  1178.1  148.45
#Mann= 7 ,-1 , 0
       0    .045       0   224.9     .09       0  601.08     .05       0
  624.78     .07       0  690.25    .045       0  843.05    .075       0
  867.79    .045       0
Bank Sta=601.08,624.78
XS Rating Curve= 0 ,0
Exp/Cntr=0.3,0.1

Type RM Length L Ch R = 1 ,29708   ,95.11,100.86,101.43
XS GIS Cut Line= 6
 2295093.5050988  737069.6464657 2295266.9387395  736628.6294935
 2295281.8044802  736475.0168403 2295234.7296348  736195.0453917
 2295175.2666723  735979.4921525 2295086.0722285  735739.1626789
#Sta/Elev= 30
       0  149.77    75.5  149.06   153.3  147.76  385.43  141.08  411.14  141.26
  465.19  140.48  535.07  139.41  552.66  138.12  599.01  131.09  610.27  129.88
   649.1  130.12  664.11   129.7  666.89  127.61  668.31  125.77  670.89  123.57
  676.25  123.58  680.08  124.33  682.41  126.04  685.19   128.1  690.82  129.11
  747.97   129.1  837.66  131.11  851.37  131.92  898.39  132.94  960.29  134.08
 1032.24  134.76 1099.96  137.45 1178.59  139.67 1313.01  141.49 1392.79  143.51
#Mann= 5 ,-1 , 0
       0    .045       0  465.19     .09       0  668.31     .05       0
  682.41     .07       0  898.39    .045       0
Bank Sta=668.31,682.41
XS Rating Curve= 0 ,0
Exp/Cntr=0.5,0.3

Type RM Length L Ch R = 1 ,29608   ,210.29,210.09,217.06
BEGIN DESCRIPTION:
Surveyed Section
END DESCRIPTION:
XS GIS Cut Line= 6
 2295295.0486263  736984.7871739 2295327.9114599  736670.6571463
    2295374.2147     736568.2672    2295385.1052     736438.0123
    2295373.4722     736424.2381 2295205.0204988  735599.2544487
#Sta/Elev= 30
       0  146.47  252.36  140.82  299.28  138.57  352.33   138.3  377.36  131.04
  380.52  132.06  380.73  130.02  397.17  133.48  410.22  133.15  422.24  135.22
  429.92  134.87 430.008  133.99  528.49  130.74 541.987  129.85 561.996  124.26
 580.029  123.25 597.057  123.72  606.73  129.81 620.031  131.45 674.622  132.92
 732.981  132.01  783.91   131.9  806.56  131.03   832.2   134.7  874.34  132.26
   934.5  135.35  989.19  135.22 1050.53  137.33 1238.96  139.42 1422.71  144.48
#Mann= 7 ,-1 , 0
       0     .09       0  528.49     .04       0 541.987     .05       0
  606.73     .04       0 732.981     .07       0  783.91     .09       0
 1050.53    .045       0
#XS Ineff= 2 , 0
       0     488  143.97     634       0  143.96
Permanent Ineff=
       F       F
Bank Sta=541.987,606.73
XS Rating Curve= 0 ,0
Exp/Cntr=0.5,0.3