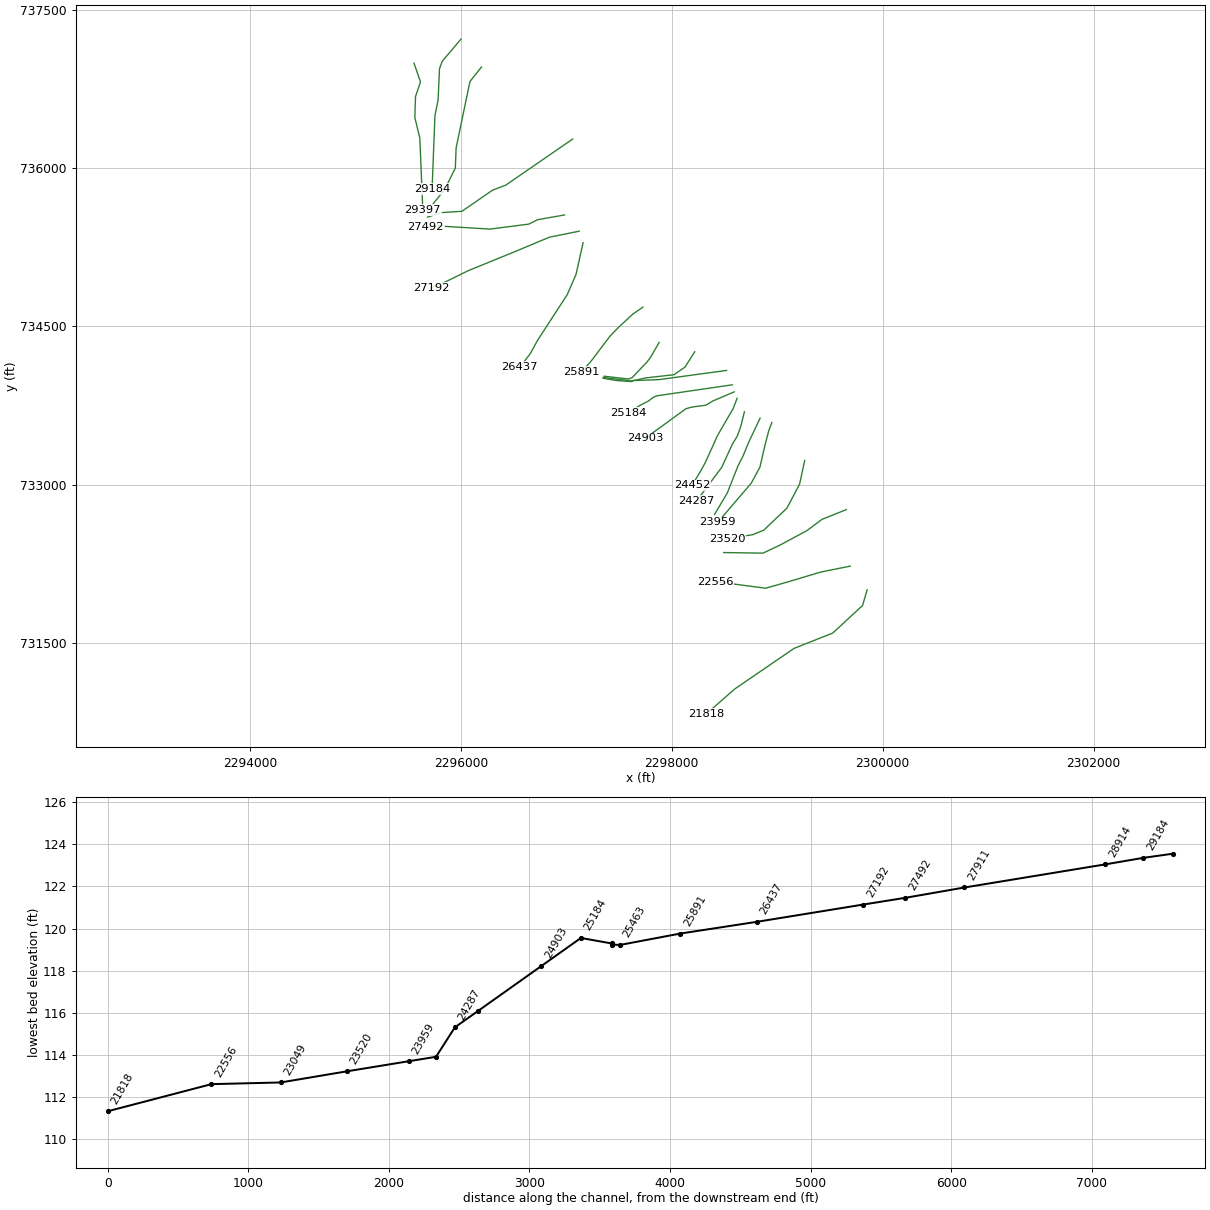
HEC-RAS study dtl_Bloomery_Swamp.prj: DTL_Bloomery_Swamp

--- dtl_Bloomery_Swamp.g01 (geometry) --- (continued)

Type RM Length L Ch R = 3 ,29569   ,,,
BEGIN DESCRIPTION:
I-95
END DESCRIPTION:
Bridge Culvert--1,0,-1,-1, 0
Deck Dist Width WeirC Skew NumUp NumDn MinLoCord MaxHiCord MaxSubmerge Is_Ogee
26.2,154.2,2.6,0, 64, 64, , , 0.98, 0, 1,1,,
       0    3.26    9.49   13.85   13.85   22.58   22.58   36.08   36.24   36.26
    36.3   36.34   36.34   50.72   62.85   62.85    67.4    67.4   69.29   69.29
   69.92    77.1    77.1   86.77   86.77   88.53   88.53   92.95   92.95   96.87
  101.37  101.37  112.29  112.29  122.46  128.63   130.9  135.12  142.64  148.42
  153.92  153.92 339.416 390.606 391.094 439.991 440.177 508.013 543.546 578.543
 578.552 614.128  614.48 666.671 720.581 783.621 1357.77 1367.77 1368.82 1380.78
 1388.32 1391.63 1396.39    1450
  143.26  143.21  143.18  143.22  143.22   143.3   143.3  143.45  143.45  143.45
  143.45  143.45  143.45  143.35  143.43  143.43  143.44  143.44  143.43  143.43
  143.44  143.31  143.31  143.33  143.33  143.33  143.33  143.33  143.33  143.28
  143.29  143.29   143.3   143.3  143.34  143.25  143.28  143.27  143.41  143.41
  143.53  143.53  144.09  143.98  143.98  143.96  143.96  143.97  143.99  143.99
  143.99  143.96  143.96  144.04  144.05  144.08  144.59  144.45  144.43  144.53
  144.67  144.68  144.54  144.67
                                                                                
                                                                                
                                                                                
                                                                                
                                                          139.97  139.99  139.99
  139.99  139.99  139.96
                                
     -63  -59.74  -53.51  -49.15  -49.15  -40.42  -40.42  -26.92  -26.76  -26.74
   -26.7  -26.66  -26.66  -12.28    -.15    -.15     4.4     4.4    6.29    6.29
    6.92    14.1    14.1   23.77   23.77   25.53   25.53   29.95   29.95   33.87
   38.37   38.37   49.29   49.29   59.46   65.63    67.9   72.12   79.64   85.42
   90.92   90.92 276.416 327.606 328.094 376.991 377.177 445.013 480.546 515.543
 515.552 551.128  551.48 603.671 657.581 720.621 1294.77 1304.77 1305.82 1317.78
 1325.32 1328.63 1333.39    1450
  143.26  143.21  143.18  143.22  143.22   143.3   143.3  143.45  143.45  143.45
  143.45  143.45  143.45  143.35  143.43  143.43  143.44  143.44  143.43  143.43
  143.44  143.31  143.31  143.33  143.33  143.33  143.33  143.33  143.33  143.28
  143.29  143.29   143.3   143.3  143.34  143.25  143.28  143.27  143.41  143.41
  143.53  143.53  144.09  143.98  143.98  143.96  143.96  143.97  143.99  143.99
  143.99  143.96  143.96  144.04  144.05  144.08  144.59  144.45  144.43  144.53
  144.67  144.68  144.54  144.67
                                                                                
                                                                                
                                                                                
                                                                                
                                                          139.97  139.99  139.99
  139.99  139.99  139.96
                                
Pier Skew, UpSta & Num, DnSta & Num=  ,543.55, 2 ,480.55, 2 , 0 , 0 , 0 ,,
     2.5     2.5
     128     148
     2.5     2.5
     128     148
Pier Skew, UpSta & Num, DnSta & Num=  ,578.54, 2 ,515.54, 2 , 0 , 0 , 0 ,,
     2.5     2.5
     128     148
     2.5     2.5
     128     148
Abutment Skew #Up #Dn= , 2 , 2
  508.01  528.01
  139.97     128
  445.01  465.01
  139.97     128
Abutment Skew #Up #Dn= , 2 , 2
  594.13  614.13
     128  139.99
  531.48  551.48
     128  139.96
BR Coef=-1 , 0 , 0 ,, 0 ,,,0.8,0,,0,
WSPro=,,,, 1 ,,,, 0 ,,,, 0 ,,,,-1 ,-1 ,-1 , 0 , 0 , 0 , 0 , 0
BC Design=,, 0 ,, 0 ,,,,,,
BC Use User HTab Curves=0
BC User HTab FreeFlow(D)= 0

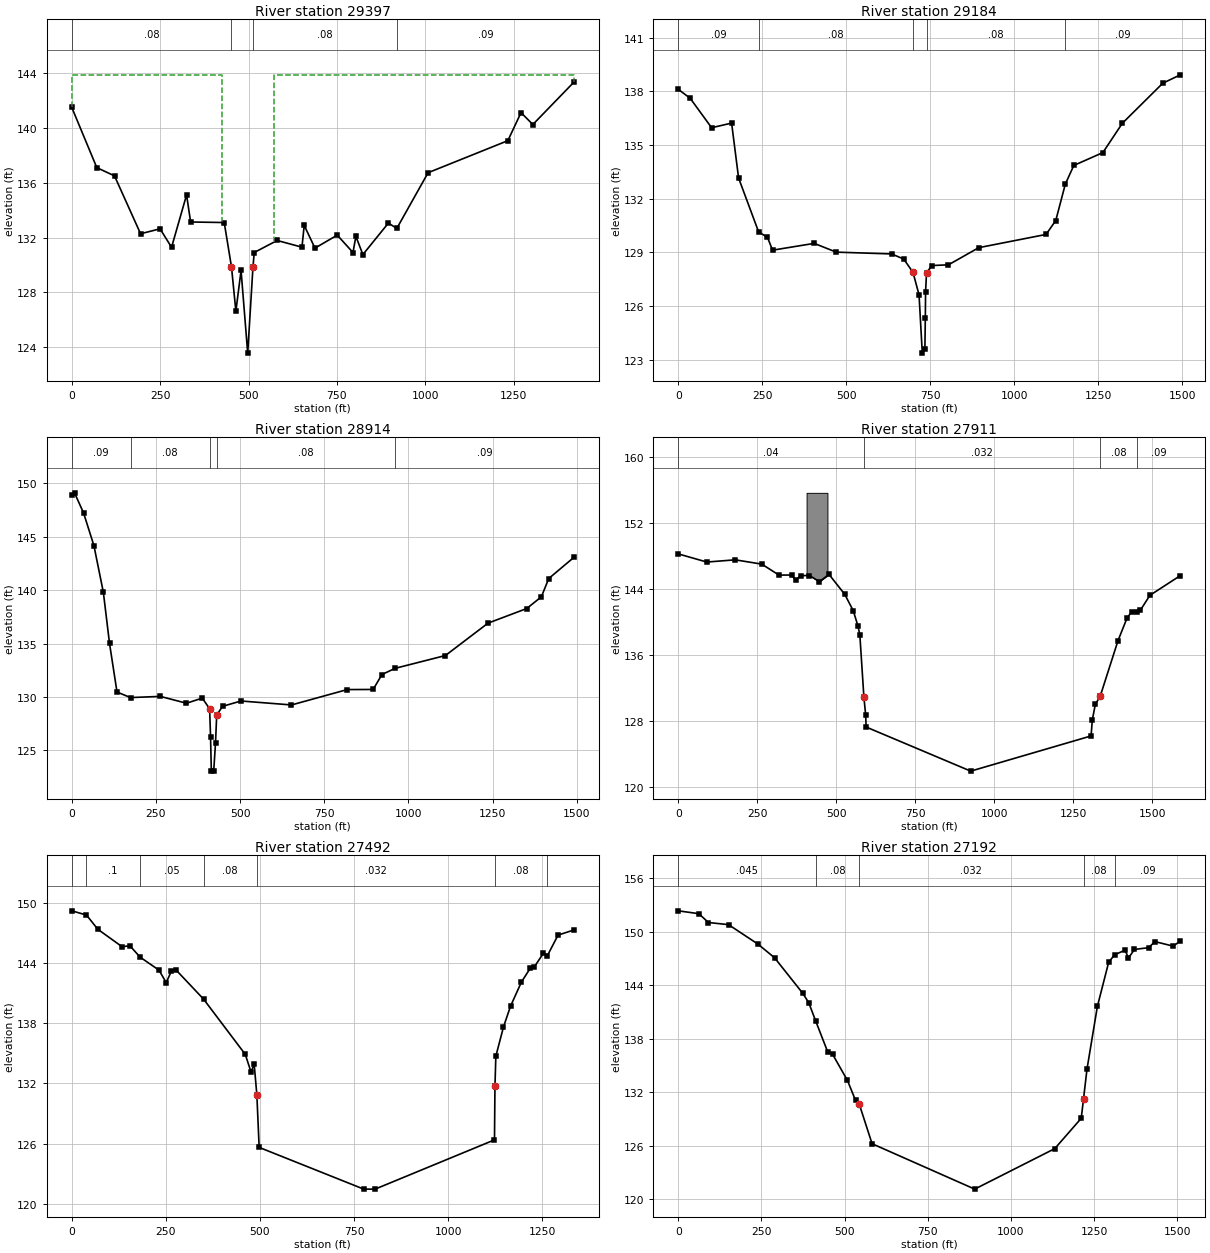
Type RM Length L Ch R = 1 ,29397   ,252.59,213.73,178.21
BEGIN DESCRIPTION:
Surveyed Section
END DESCRIPTION:
XS GIS Cut Line= 6
 2295555.8585502  736993.9081904 2295617.8776392   736815.640236
    2295570.5764      736676.097    2295564.3906      736477.512
 2295611.5327622  736284.5924774  2295639.943703  735602.1539367
#Sta/Elev= 30
       0  141.51   70.81  137.11  120.85  136.51  194.54  132.28  249.67  132.64
  282.24  131.29  324.67  135.12 336.115  133.14 431.175   133.1 451.676  129.86
  464.11  126.62 478.753   129.6 497.553  123.56 512.406  129.84 515.948  130.91
 580.839  131.79 650.987   131.3  657.35  132.89  687.77  131.23  750.75  132.18
  795.32  130.91  803.47  132.09   823.3  130.76  895.43  133.06  919.25  132.67
 1007.71  136.74 1233.25  139.08 1270.53  141.13 1303.94  140.26 1419.91  143.35
#Mann= 4 ,-1 , 0
       0     .08       0 451.676     .05       0 512.406     .08       0
  919.25     .09       0
#XS Ineff= 2 , 0
       0     424  143.89     572       0  143.86
Permanent Ineff=
       F       F
Bank Sta=451.676,512.406
XS Rating Curve= 0 ,0
Exp/Cntr=0.5,0.3

Type RM Length L Ch R = 1 ,29184   ,278.14,270.24,299.89
XS GIS Cut Line= 6
 2296002.0807724  737220.6870052 2295824.6825111  737011.6972728
 2295797.9512663  736940.0089344 2295784.7620383  736643.4952341
  2295755.030557  736497.3154512 2295727.7766992  735801.1032649
#Sta/Elev= 30
       0  138.12   35.47  137.62   99.33  135.97  158.81  136.23  179.55  133.16
  239.19  130.14  265.49  129.84  280.61  129.12  404.54   129.5  470.19  129.01
  635.06  128.91  671.09  128.62  698.51  127.88  716.52  126.62   726.2  123.36
  733.88  123.57  735.22  125.35  735.99   126.8  738.74  127.83  753.91  128.26
  804.04   128.3  894.13  129.26 1094.44     130 1123.37  130.78 1151.83  132.82
 1177.05  133.86 1263.54  134.58 1321.46  136.22 1441.69  138.46 1493.94  138.93
#Mann= 5 ,-1 , 0
       0     .09       0  239.19     .08       0  698.51     .05       0
  738.74     .08       0 1151.83     .09       0
#XS Ineff= 2 , 0
       0     353             978       0
Permanent Ineff=
       F       F
Bank Sta=698.51,738.74
XS Rating Curve= 0 ,0
Exp/Cntr=0.3,0.1

Type RM Length L Ch R = 1 ,28914   ,948.13,1002.1,767.46
XS GIS Cut Line= 6
 2296196.0475292  736955.6757875 2296087.0320979  736819.4064983
 2295955.7180556  736190.0901448 2295948.2851853    735999.31314
 2295846.7026243   735796.148018 2295686.7325793  735597.3711391
#Sta/Elev= 30
       0  148.94    8.13  149.12   35.12  147.23   65.84  144.17   93.84   139.8
  112.17  135.01  134.39  130.46  174.51  129.94   263.2  130.05  340.76  129.41
  387.66  129.89   409.6  128.89  412.32  126.23  414.65  123.05  421.69  123.05
  427.08   125.7  430.59   128.3     448  129.12  502.76  129.62   652.8  129.25
  818.44  130.69  895.36   130.7  921.54   132.1  960.74  132.68 1110.17  133.88
 1236.51  136.91 1351.63  138.28 1395.21  139.38 1417.07  141.09 1491.66  143.07
#Mann= 5 ,-1 , 0
       0     .09       0  174.51     .08       0   409.6     .05       0
  430.59     .08       0  960.74     .09       0
Bank Sta=409.6,430.59
XS Rating Curve= 0 ,0
Exp/Cntr=0.3,0.1

Type RM Length L Ch R = 1 ,27911   ,503.77,419.9,149.79
XS GIS Cut Line= 6
2297060.73810944 736274.329341712296426.46650898735838.267616436
2296302.58533704735791.1927711072296010.22577126735590.505272537
2295816.97114299735578.1171553432295685.65710074735535.997556865
#Sta/Elev= 30
       0  148.26    90.5  147.27  180.45  147.54   264.4  147.02  319.01  145.69
   358.6   145.7   371.8  145.08  387.54  145.63   415.2  145.64  446.95   144.9
  477.23  145.78  527.33  143.35  554.14  141.37  568.88  139.54  574.93  138.44
  587.76  130.91  593.32  128.76   594.9  127.29  925.95  121.95  1306.9  126.21
 1310.92  128.17 1320.47  130.04 1335.77  131.01 1392.26  137.76 1420.91   140.5
 1435.09  141.23 1452.44  141.26 1462.91  141.43 1493.17  143.24 1589.45  145.63
#Mann= 4 ,-1 , 0
       0     .04       0  587.76    .032       0 1335.77     .08       0
 1452.44     .09       0
#Block Obstruct= 1 ,-1
  406.27  472.33 155.654
Bank Sta=587.76,1335.77
XS Rating Curve= 0 ,0
Exp/Cntr=0.3,0.1

Type RM Length L Ch R = 1 ,27492   ,218.36,299.02,510.13
XS GIS Cut Line= 6
2296983.93178281735555.8185443732296728.73656857735511.221322477
2296644.49737166735469.1017240142296275.33147925735422.026878685
2295789.71728514735451.7583599392295668.31373665735441.847866178
#Sta/Elev= 30
       0   149.2   39.09  148.78   69.24  147.36  133.78  145.62  154.53  145.72
  181.31  144.59   231.7  143.29  250.99  142.04  264.61  143.19  276.68  143.32
  350.21   140.4  461.06  134.89  476.19  133.15  484.72   133.9  491.84  130.84
  497.93  125.62  775.83  121.46  805.99  121.46 1123.26  126.37 1124.49  131.69
 1126.88  134.71  1147.2  137.63 1165.82  139.69 1194.84   142.1 1218.47  143.49
 1229.01   143.6 1253.46  144.99 1263.96  144.74 1292.17  146.78 1334.13  147.29
#Mann= 7 ,-1 , 0
       0    .045       0   39.09      .1       0  181.31     .05       0
  350.21     .08       0  491.84    .032       0 1124.49     .08       0
 1263.96     .09       0
Bank Sta=491.84,1124.49
XS Rating Curve= 0 ,0
Exp/Cntr=0.3,0.1

Type RM Length L Ch R = 1 ,27192   ,588.25,755.33,999.59
XS GIS Cut Line= 6
2297122.67869541735402.2058911622296840.22962332735345.220552087
2296495.83996531735201.5183925932296069.68873379735028.084751844
 2295797.1501555734894.2930861412295717.86620542734867.039228305
#Sta/Elev= 30
       0  152.34   61.95  152.02   90.68  151.03  151.21  150.79  239.49  148.61
  289.44  147.08   374.3  143.09   392.1  142.05  412.97     140  449.76  136.47
  463.69  136.27  508.59  133.32  532.88  131.08   543.9  130.68  582.51  126.23
  890.96  121.14 1131.54  125.68  1211.1  129.08 1217.94  131.25  1228.4  134.59
 1259.59  141.62 1293.52  146.57 1311.19  147.41 1342.94  147.93 1352.94  147.04
 1370.96  148.01 1413.82  148.21 1432.48  148.89 1487.47  148.38 1508.85  148.96
#Mann= 5 ,-1 , 0
       0    .045       0  412.97     .08       0   543.9    .032       0
 1217.94     .08       0 1311.19     .09       0
Bank Sta=543.9,1217.94
XS Rating Curve= 0 ,0
Exp/Cntr=0.3,0.1

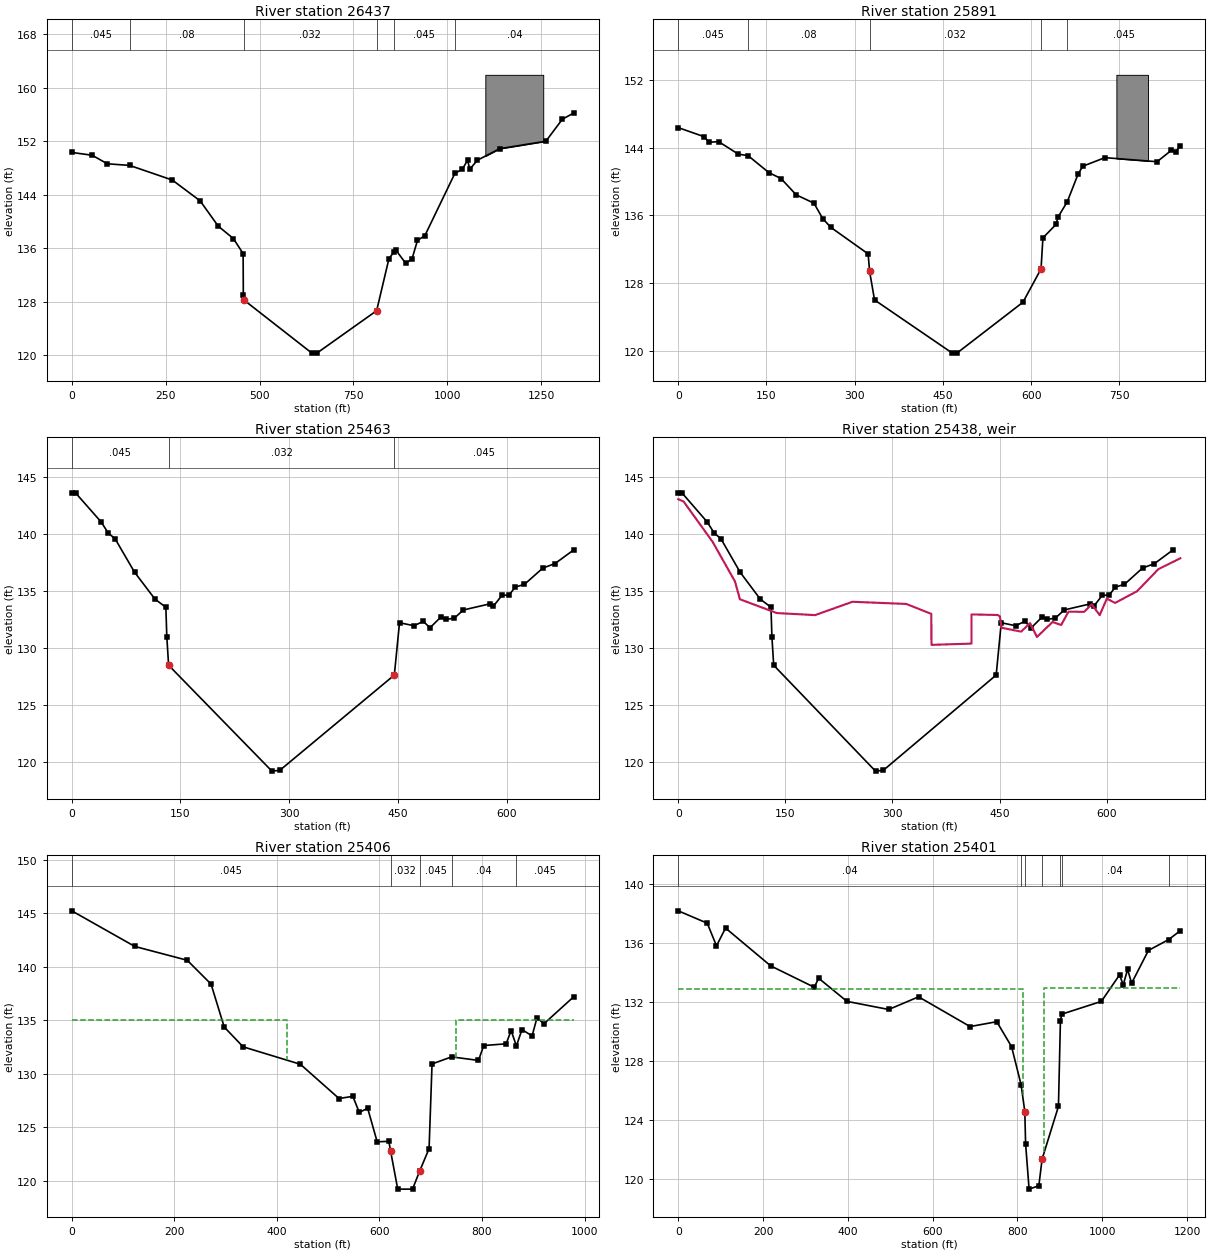
Type RM Length L Ch R = 1 ,26437   ,621.45,546.61,535.14
XS GIS Cut Line= 6
2297159.84304699735293.1904598332297092.94721411 734993.39802371
 2297008.7080172734800.1433954832296731.21419202734373.992163941
2296656.88548885734240.2004982382296560.25817473734116.319326267
#Sta/Elev= 30
       0  150.35   54.27  149.93   94.74  148.65  154.03  148.41  267.68  146.22
  341.78  143.11  390.04  139.32   430.6  137.45  456.33  135.21  456.86  129.08
  458.86  128.25  639.45  120.32  652.77  120.32  811.88  126.67  844.55  134.44
  857.31  135.41  862.31  135.79  889.51  133.75  906.22  134.44  920.63  137.19
  940.19  137.89 1020.16  147.21 1040.34  147.86 1053.94  149.18 1059.96  147.85
 1080.35  149.19 1139.52  150.91 1262.55  152.03 1306.48  155.32 1337.03  156.26
#Mann= 6 ,-1 , 0
       0    .045       0  154.03     .08       0  458.86    .032       0
  811.88     .09       0  857.31    .045       0 1020.16     .04       0
#Block Obstruct= 1 ,-1
 1101.28  1255.5 161.963
Bank Sta=458.86,811.88
XS Rating Curve= 0 ,0
Exp/Cntr=0.3,0.1

Type RM Length L Ch R = 1 ,25891   ,403.36,427.8,314.44
XS GIS Cut Line= 6
2297727.21881457734683.695093811  2297628.113877734614.321637541
 2297496.7998347734492.9180890172297415.03826123734408.678892076
2297229.21650332734163.394171625 2297142.4996829734069.244480938
#Sta/Elev= 30
       0  146.35   44.41  145.27   52.18  144.62   68.64   144.7  102.16  143.22
  118.64  143.05     154  141.05  174.82  140.34  200.47  138.43  230.68  137.44
  245.59  135.63  259.37  134.59  322.82  131.46  325.32  129.39  333.71  126.03
  465.53  119.78  473.76  119.76  586.01  125.76  616.75  129.69  619.95  133.35
  642.15  134.93  645.61   135.8  661.22  137.59  680.04  140.92  687.87   141.8
  725.33  142.81  814.04  142.33  838.22  143.67  846.27  143.53  853.52   144.2
#Mann= 5 ,-1 , 0
       0    .045       0  118.64     .08       0  325.32    .032       0
  616.75     .09       0  661.22    .045       0
#Block Obstruct= 1 ,-1
  744.85  798.51 152.575
Bank Sta=325.32,616.75
XS Rating Curve= 0 ,0
Exp/Cntr=0.5,0.3

Type RM Length L Ch R = 1 ,25463   ,248.59,56.9,33.79
XS GIS Cut Line= 6
2297880.83146775734349.2159295382297798.72786579734206.888902113
2297766.16422808734164.2351230832297625.36089301 734016.09350349
2297591.42132691734002.7928627132297358.88943484734029.394144252
#Sta/Elev= 30
       0  143.64    5.55  143.61    40.6  141.08   50.03  140.14   59.96  139.59
   86.59  136.68  114.88  134.31  129.84   133.6  131.18  130.99  133.66  128.51
  276.24  119.22  287.13  119.29  445.18  127.65  452.31  132.24  472.34  131.98
  485.19  132.36  494.34   131.8  509.62  132.75  516.05  132.53  527.98  132.64
  540.38  133.36  576.52  133.89  581.61  133.67  593.92  134.66  603.23  134.65
  612.24  135.38  624.63   135.6  650.15  137.04  666.87  137.43  692.92  138.64
#Mann= 3 ,-1 , 0
       0    .045       0  133.66    .032       0  445.18    .045       0
Bank Sta=133.66,445.18
XS Rating Curve= 0 ,0
Exp/Cntr=0.5,0.3

Type RM Length L Ch R = 5 ,25438   ,,,
BEGIN DESCRIPTION:
Dam off Raleigh Rd (Business 264)
END DESCRIPTION:
IW Pilot Flow=0
#Inline Weir SE= 30
       0  143.08    7.59  142.87   48.17  139.34   79.46  135.86  86.354   134.3
 138.037  133.09 191.596  132.91 243.958  134.08 319.223  133.89 354.297  133.02
 354.588   130.3 410.639  130.41 410.639  132.97  447.38  132.92  450.38   132.8
   452.7   131.8  480.15  131.46  492.59  132.21  502.27  130.99  524.18  132.31
  536.15  132.04  546.43  133.21  568.42   133.2     579  133.85  590.14  132.91
  600.16  134.35  611.73  133.98  642.57  135.01  672.25  136.94  703.02   137.9
IW Dist,WD,Coef,Skew,MaxSub,Min_El,Is_Ogee,SpillHt,DesHd
25.5,1.5,2.6,0,0.95,, 0 ,,,0,0,

Type RM Length L Ch R = 1 ,25406   ,31.94,4.4,14.54
XS GIS Cut Line= 6
 2298218.8060378  734261.0472753 2298126.3350278  734116.2341841
  2298021.951269  734043.4383618 2297750.0656179  734012.8808763
 2297621.6901006  733983.8405713  2297352.223453  734017.1094957
#Sta/Elev= 30
       0  145.24  122.95  141.91  225.16  140.62  271.63  138.39  297.29  134.38
  334.14  132.53   445.8   130.9  521.15   127.7  548.14   127.9  560.71   126.4
  577.03  126.79  595.59  123.65  618.31   123.7  621.64  122.82  635.67  119.23
  664.53  119.23  678.33   120.9  696.79  123.02  702.59  130.93   740.7  131.59
  793.17  131.26  803.36  132.65  847.08  132.81  856.79  134.05  867.11  132.61
  877.97  134.14  897.69  133.55  907.35  135.26  920.68  134.68  979.12  137.22
#Mann= 5 ,-1 , 0
       0    .045       0  621.64    .032       0  678.33    .045       0
   740.7     .04       0  867.11    .045       0
#XS Ineff= 2 , 0
       0     420     135     750       0     135
Permanent Ineff=
       F       F
Bank Sta=621.64,678.33
XS Rating Curve= 0 ,0
Exp/Cntr=0.5,0.3

Type RM Length L Ch R = 1 ,25401   ,157.97,217.91,293.48
XS GIS Cut Line= 6
  2298520.389379  734084.1037823 2297879.7332066   733997.190119
 2297629.7431609  733988.0881922 2297622.4041275  733978.6873584
 2297475.0358392  733988.4833725 2297349.2364526  734010.4897558
#Sta/Elev= 30
       0  138.19   68.44  137.35   90.24  135.81  111.57  137.02  218.12  134.45
  320.78     133  331.21  133.61  397.99  132.04  496.41  131.49  566.93  132.35
  688.33  130.33  751.23  130.66   786.1  128.97  808.65  126.38  817.41  124.55
  819.24  122.37   827.5  119.29   850.5  119.52  858.18  121.33  896.72  124.91
  901.37  130.71  904.33  131.17  997.98  132.04 1040.85  133.84 1049.57  133.16
 1059.72  134.21 1069.35  133.28 1108.93   135.5 1156.78  136.24 1184.14  136.84
#Mann= 7 ,-1 , 0
       0     .04       0  808.65    .045       0  817.41     .05       0
  858.18    .032       0  901.37    .045       0  904.33     .04       0
 1156.78    .045       0
#XS Ineff= 2 , 0
       0  812.41  132.89  863.18       0  132.95
Permanent Ineff=
       F       F
Bank Sta=817.41,858.18
XS Rating Curve= 0 ,0
Exp/Cntr=0.5,0.3

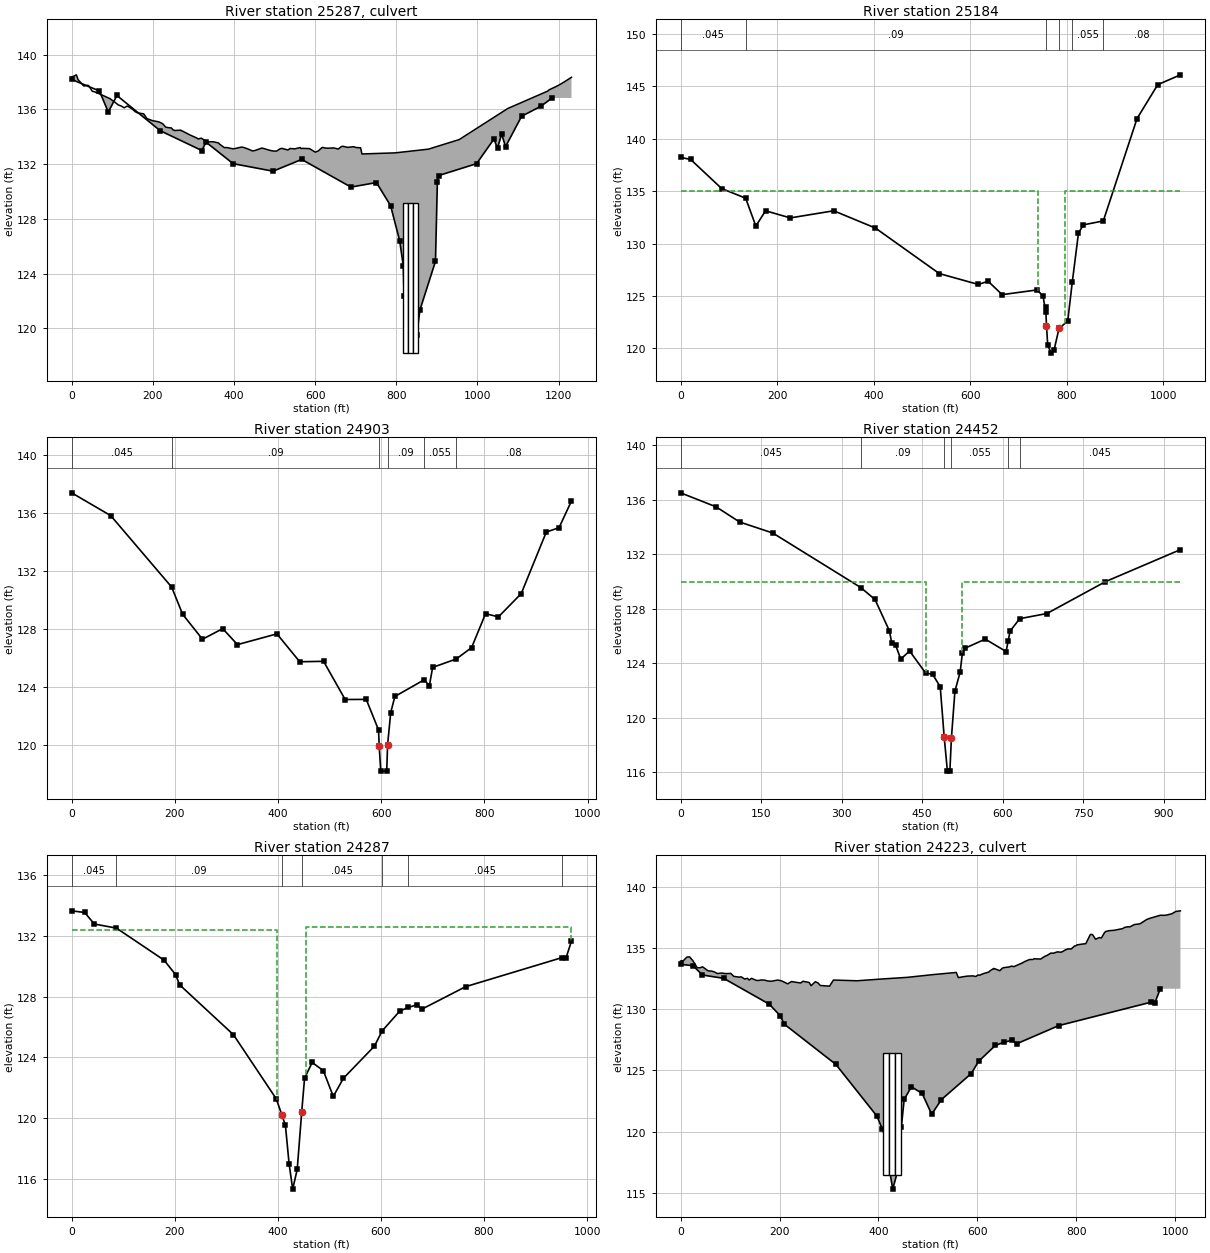
Type RM Length L Ch R = 2 ,25287   ,,,
BEGIN DESCRIPTION:
Raleigh Rd (Business 264)
END DESCRIPTION:
Bridge Culvert--1,0,-1,-1, 0
Deck Dist Width WeirC Skew NumUp NumDn MinLoCord MaxHiCord MaxSubmerge Is_Ogee
17.7,120,2.6,0, 156, 148, , , 0.95, 0, 1,1,,
       0   11.74   15.85   29.11   30.68   36.99   40.29   41.89   41.89   50.83
   56.48   56.48   70.62   70.62   71.12   71.12   71.36   72.04    75.3   90.33
   91.51   94.44   94.44  100.34  100.34  106.98  114.78  114.83  122.28  122.28
  129.46  129.46  137.02  137.02  149.08  149.08  157.39  158.53  162.36  177.56
  177.56  185.68  185.68  194.51  199.53  210.99  212.23  212.23  216.95  222.34
  224.59  232.32  232.32  239.07  239.07   245.7   245.7  250.21   252.4  253.66
  269.14  270.27   273.3  291.44     304  308.72  311.98  318.59  319.55  330.65
  334.32  340.99  340.99  349.27  349.29  349.36  349.36  362.42  362.42  364.12
  364.12  376.42  382.21  382.21  396.75     402  415.06  415.06  420.24  425.52
  435.52   445.7  447.87  451.68   467.3   467.3  468.71  471.77  471.77  490.13
  498.64  498.64  505.11  505.11  513.35  513.35  515.82  517.75  533.05  538.44
  550.21  550.21  551.28  563.13  563.13  565.69  565.69  569.07  586.25   600.5
  607.74  607.74  617.62  617.62  625.64  625.64  631.96  645.95  645.95  657.05
  664.99  668.63  680.36  680.36  690.08  694.69  694.69  700.36  700.83  712.16
  712.16 715.496 797.462 879.121 955.0761074.783  1173.2  1173.2 1176.42  1193.6
  1193.6 1201.44 1201.44 1213.94 1231.22 1231.88
  138.36  138.53  138.18  137.74  137.71  137.76  137.76  137.74  137.74  137.33
  137.29  137.29  137.11  137.11   137.1   137.1   137.1  137.09  137.05  136.85
  136.83  136.79  136.79  136.66  136.66  136.52  136.33  136.33  136.25  136.25
  136.12  136.12  136.25  136.25  136.04  136.04  135.82  135.81  135.75  135.68
  135.68  135.33  135.33  135.23  135.18  135.12  135.11  135.11  135.07  134.99
  134.95   134.7   134.7  134.67  134.67  134.65  134.65   134.5  134.49  134.46
  134.49  134.44  134.42  134.14  133.97  133.91  133.84   133.9   133.9   133.7
  133.62  133.64  133.64  133.64  133.64  133.64  133.64  133.55  133.55  133.48
  133.48  133.21  133.22  133.22  133.13  133.14  133.23  133.23  133.25  133.21
   133.1  132.97  132.98     133  133.17  133.17  133.18  133.16  133.16     133
  132.96  132.96  132.96  132.96  133.12  133.12  133.14  133.16  133.04  133.15
  133.12  133.12  133.13  133.22  133.22  133.14  133.14  133.16  133.14  132.88
  132.97  132.97  133.23  133.23  133.18  133.18  133.17  133.19  133.19  133.11
  133.29  133.31  133.23  133.23  133.26  133.28  133.28  133.22  133.22   133.2
   133.2  132.75  132.83   133.1   133.8  136.07  137.34  137.34  137.43  137.67
  137.67  137.79  137.79  138.01  138.34  138.35
                                                                                
                                                                                
                                                                                
                                                                                
                                                                                
                                                                                
                                                                                
                                                                                
                                                                                
                                                                                
                                                                                
                                                                                
                                                                                
                                                                                
                                                                                
                                                
       0   11.74   15.85   29.11   30.68   36.99   40.29   41.89   41.89   50.83
   56.48   56.48   70.62   70.62   71.12   71.12   71.36   72.04    75.3   90.33
   91.51   94.44   94.44  100.34  100.34  106.98  114.78  114.83  122.28  122.28
  129.46  129.46  137.02  137.02  149.08  149.08  157.39  158.53  162.36  177.56
  177.56  185.68  185.68  194.51  199.53  210.99  212.23  212.23  216.95  222.34
  224.59  232.32  232.32  239.07  239.07   245.7   245.7  250.21   252.4  253.66
  269.14  270.27   273.3  291.44     304  308.72  311.98  318.59  319.55  330.65
  334.32  340.99  340.99  349.27  349.29  349.36  349.36  362.42  362.42  364.12
  364.12  376.42  382.21  382.21  396.75     402  415.06  415.06  420.24  425.52
  435.52   445.7  447.87  451.68   467.3   467.3  468.71  471.77  471.77  490.13
  498.64  498.64  505.11  505.11  513.35  513.35  515.82  517.75  533.05  538.44
  550.21  550.21  551.28  563.13  563.13  565.69  565.69  569.07  586.25   600.5
  607.74  607.74  617.62 700.893 733.997 774.649 814.739 867.221 985.5961129.513
 1132.65 1135.53 1143.21 1143.21 1154.33 1154.33  1168.9  1168.9  1173.2  1173.2
 1176.42  1193.6  1193.6 1201.44 1201.44 1213.94 1231.22 1231.88
  138.36  138.53  138.18  137.74  137.71  137.76  137.76  137.74  137.74  137.33
  137.29  137.29  137.11  137.11   137.1   137.1   137.1  137.09  137.05  136.85
  136.83  136.79  136.79  136.66  136.66  136.52  136.33  136.33  136.25  136.25
  136.12  136.12  136.25  136.25  136.04  136.04  135.82  135.81  135.75  135.68
  135.68  135.33  135.33  135.23  135.18  135.12  135.11  135.11  135.07  134.99
  134.95   134.7   134.7  134.67  134.67  134.65  134.65   134.5  134.49  134.46
  134.49  134.44  134.42  134.14  133.97  133.91  133.84   133.9   133.9   133.7
  133.62  133.64  133.64  133.64  133.64  133.64  133.64  133.55  133.55  133.48
  133.48  133.21  133.22  133.22  133.13  133.14  133.23  133.23  133.25  133.21
   133.1  132.97  132.98     133  133.17  133.17  133.18  133.16  133.16     133
  132.96  132.96  132.96  132.96  133.12  133.12  133.14  133.16  133.04  133.15
  133.12  133.12  133.13  133.22  133.22  133.14  133.14  133.16  133.14  132.88
  132.97  132.97  133.23  134.13  134.12  134.14  134.23  134.27  134.91  137.14
  136.15  136.21  136.36  136.36  136.69  136.69  137.19  137.19  137.34  137.34
  137.43  137.67  137.67  137.79  137.79  138.01  138.34  138.35
                                                                                
                                                                                
                                                                                
                                                                                
                                                                                
                                                                                
                                                                                
                                                                                
                                                                                
                                                                                
                                                                                
                                                                                
                                                                                
                                                                                
                                                                
BR Coef=-1 , 0 , 0 ,, 0 ,,,0.8,-1,,0,
WSPro=,,,, 1 ,,,, 0 ,,,, 0 ,,,,-1 ,-1 ,-1 , 0 , 0 , 0 , 0 , 0
Multiple Barrel Culv=2,11,12,155,0.012,0.4,1,8,1,118.2,118, 3,Culvert #1  , 0 ,5.1
  822.82  755.81  835.32  768.31  847.82  780.81
Culvert Bottom n=0.012
BC Design=,, 0 ,, 0 ,,,,,,
BC Use User HTab Curves=0
BC User HTab FreeFlow(D)= 0

Type RM Length L Ch R = 1 ,25184   ,255.48,280.45,284.24
BEGIN DESCRIPTION:
Surveyed Section
END DESCRIPTION:
XS GIS Cut Line= 6
 2298574.7501047  733947.9315005 2297859.7570619  733843.8898433
     2297828.244       733830.99    2297775.4894     733791.8855
 2297702.1086297  733754.9779483 2297591.1111291  733685.2080908
#Sta/Elev= 30
       0  138.22   20.71  138.03   85.14  135.25  134.88  134.33  155.94  131.67
  176.03  133.13  227.33  132.45  317.36  133.13  403.84  131.48  536.19  127.14
  617.22   126.1   637.2  126.41  666.46  125.13   739.1  125.58   751.3  124.98
  756.54   123.5 756.681  123.92  758.34  122.17  760.91   120.3  768.16  119.55
 774.255  119.88 784.242   121.9 802.322  122.61  811.86 126.342  824.65  131.01
  834.99  131.79  876.09  132.16  946.04  141.93  988.93  145.16 1035.94   146.1
#Mann= 6 ,-1 , 0
       0    .045       0  134.88     .09       0  758.34     .05       0
 784.242     .09       0  811.86    .055       0  876.09     .08       0
#XS Ineff= 2 , 0
       0  740.31     135  796.31       0     135
Permanent Ineff=
       F       F
Bank Sta=758.34,784.242
XS Rating Curve= 0 ,0
Exp/Cntr=0.5,0.3

Type RM Length L Ch R = 1 ,24903   ,420.02,451.23,483.85
XS GIS Cut Line= 6
 2298592.5114279  733881.0505889 2298389.4716404  733794.4832376
 2298324.9396149  733755.1344416 2298195.8755639  733737.8209714
  2298136.065394   733722.081453 2297747.2992892  733440.3440734
#Sta/Elev= 30
       0  137.38   75.73  135.81  193.82  130.89  215.02  129.02  253.56   127.3
   292.7  128.03  321.35  126.93  397.78  127.67  441.99  125.75  488.23  125.78
  530.01  123.15  570.87  123.16  594.69  121.06  596.05  119.93  599.01  118.22
   610.6  118.22  612.21     120  618.25  122.24  626.36  123.36  683.27  124.51
  693.23   124.1  699.52  125.36  745.26  125.94  775.02  126.72  802.11  129.06
  827.06  128.84  871.23  130.44  919.82  134.68  944.52  134.98  968.62  136.82
#Mann= 6 ,-1 , 0
       0    .045       0  193.82     .09       0  596.05     .05       0
  612.21     .09       0  683.27    .055       0  745.26     .08       0
#XS Ineff= 2 , 0
       0  556.82          651.71       0
Permanent Ineff=
       F       F
Bank Sta=596.05,612.21
XS Rating Curve= 0 ,0
Exp/Cntr=0.3,0.1

Type RM Length L Ch R = 1 ,24452   ,165.32,164.55,159.61
XS GIS Cut Line= 6
  2298620.842561  733821.2404189  2298581.493765  733720.5075011
 2298435.1162438  733468.6752065  2298323.365663  733221.5647675
 2298277.7210597   733136.571368 2298192.7276602  732996.4896542
#Sta/Elev= 30
       0  136.51   66.21  135.48  109.82  134.37  171.71  133.56  335.49  129.56
  362.15  128.68  389.07  126.37  393.26  125.49   400.5  125.33  410.17   124.3
  426.54   124.9  456.32  123.29  469.49  123.18  483.65  122.28  491.02   118.6
  497.03  116.08  501.64  116.08  504.49   118.5  511.05  121.95  520.79  123.35
  524.87  124.73  529.66   125.1   567.5  125.77  606.41  124.86  610.09  125.61
  613.72  126.35  631.69  127.27  682.42  127.65  791.53  129.99  931.15  132.34
#Mann= 6 ,-1 , 0
       0    .045       0  335.49     .09       0  491.02     .05       0
  504.49    .055       0  610.09     .08       0  631.69    .045       0
#XS Ineff= 2 , 0
       0  456.32     130  524.87       0     130
Permanent Ineff=
       F       F
Bank Sta=491.02,504.49
XS Rating Curve= 0 ,0
Exp/Cntr=0.5,0.3

Type RM Length L Ch R = 1 ,24287   ,134.11,134.18,135.99
BEGIN DESCRIPTION:
Surveyed Section
END DESCRIPTION:
XS GIS Cut Line= 6
  2298689.731543   733692.784548 2298654.6388753  733552.5282784
  2298621.756552  733461.4168409 2298575.1732606  733386.0615167
     2298474.382     733166.5515 2298236.2585451   732848.820913
#Sta/Elev= 30
       0  133.65   25.31  133.54   43.91  132.78   86.89  132.51  179.22   130.4
  201.48  129.45  209.48  128.77  313.89  125.48 396.982  121.25   407.6  120.21
 414.659  119.51 421.853  116.96 428.809   115.3 437.558   116.6  446.28  120.39
 451.855  122.62 466.567  123.65 488.286  123.11 507.513  121.41 527.211  122.61
  587.43  124.73  602.29  125.73  636.48  127.04  653.24  127.28  670.21  127.46
  679.02  127.16  764.37  128.65  951.72  130.57  958.76  130.51  969.62  131.66
#Mann= 7 ,-1 , 0
       0    .045       0   86.89     .09       0   407.6     .05       0
  446.28    .045       0  602.29     .08       0  653.24    .045       0
  951.72    .085       0
#XS Ineff= 2 , 0
       0     398   132.4     455       0   132.6
Permanent Ineff=
       F       F
Bank Sta=407.6,446.28
XS Rating Curve= 0 ,0
Exp/Cntr=0.5,0.3

Type RM Length L Ch R = 2 ,24223   ,,,
BEGIN DESCRIPTION:
Merck Road
END DESCRIPTION:
Bridge Culvert--1,0,-1,-1, 0
Deck Dist Width WeirC Skew NumUp NumDn MinLoCord MaxHiCord MaxSubmerge Is_Ogee
32,63.9,2.6,0, 176, 176, , , 0.95, 0, 1,1,,
       0    2.32    4.74   12.85   12.85   18.15   24.81   33.47   33.47    38.8
   44.45   48.78   48.78   55.48   58.68   58.68   63.04   68.88   74.33   77.68
   77.68   82.48   82.48   92.91   92.91   94.14  101.56  101.56   107.4  113.22
  113.22  117.86  122.54  129.56  134.99  138.52  138.52  143.38  153.17  156.77
  163.65  170.23   175.4   182.5  184.46  196.42  196.44  196.46  204.22  204.25
  216.45   224.3   224.3  227.96  242.55  242.55  247.41  247.41   259.9  263.67
  272.32  277.98  282.18  284.18  296.23  299.23  299.23  301.07 308.939 356.484
 408.512 458.397 509.257 557.315  561.28  561.28  571.05  571.05  579.66  590.61
  590.61  596.68  601.36  605.08  605.48  609.08  614.15   622.9   622.9  625.29
  625.29  633.13  633.69  635.18  645.16  645.16  650.13  650.13  652.96  660.27
  664.54   668.9   673.3   673.3  679.55     691     691  695.13  705.09  712.29
  715.06  725.31  725.31  727.62  727.62  736.33  740.73  740.73  748.35  753.72
  753.72  761.41  768.93  772.92  777.71     783  789.73  796.28  796.28   798.4
   798.4  801.34  810.71     817  819.06   828.1  830.25  832.75  838.86  846.23
  850.48  857.11  857.95  859.53  859.53  866.75  876.04  876.04  879.93  879.93
  893.81  897.02  904.15  908.22  912.26  917.22  927.82  927.82  928.65  928.65
  929.81  929.81   941.6  949.29   955.5  967.07     968   968.8  969.46  977.46
  983.08  983.08  992.85 1001.08 1001.08 1010.31
  133.92  133.95  133.92  134.25  134.25  134.26  133.95  133.38  133.38  133.37
  133.45  133.32  133.32  133.12  133.11  133.11   133.1  133.02   132.9  132.92
  132.92  132.94  132.94  132.89  132.89   132.9  132.91  132.91  132.67  132.64
  132.64  132.61  132.63  132.45  132.51  132.37  132.37  132.51  132.34  132.33
  132.38  132.36   132.3  132.27  132.28  132.37  132.37  132.37   132.3   132.3
  132.06  132.25  132.25  132.22  132.13  132.13  132.27  132.27  132.17  131.91
  132.23  132.13  131.93  131.92  131.89  131.88  131.88  131.87  132.37  132.31
  132.46  132.59  132.81  132.99  132.57  132.57  132.64  132.64  132.69  132.71
  132.71  132.66  132.78  132.77  132.78  132.85  132.92  133.02  133.02  133.12
  133.12  133.32  133.28  133.29  133.13  133.13  133.33  133.33  133.38  133.42
  133.44  133.51  133.46  133.46  133.57  133.77  133.77  133.87  134.04  134.05
  134.11  134.09  134.09  134.08  134.08  134.31  134.38  134.38  134.57  134.56
  134.56  134.67  134.64  134.71  134.83  134.91  134.91  135.15  135.15  135.16
  135.16  135.24   135.3  135.33  135.34  136.08   136.1  136.07   135.7  135.84
   135.8  136.26  136.28  136.34  136.34   136.4  136.43  136.43  136.46  136.46
  136.57  136.66  136.72  136.71   136.8   136.9  136.96  136.96  136.96  136.96
  136.99  136.99   137.3  137.42  137.49  137.63  137.63  137.65  137.66  137.65
  137.68  137.68  137.78  137.97  137.97  138.02
                                                                                
                                                                                
                                                                                
                                                                                
                                                                                
                                                                                
                                                                                
                                                                                
                                                                                
                                                                                
                                                                                
                                                                                
                                                                                
                                                                                
                                                                                
                                                                                
                                                                                
                                                
       0    2.32    4.74   12.85   12.85   18.15   24.81   33.47   33.47    38.8
   44.45   48.78   48.78   55.48   58.68   58.68   63.04   68.88   74.33   77.68
   77.68   82.48   82.48   92.91   92.91   94.14  101.56  101.56   107.4  113.22
  113.22  117.86  122.54  129.56  134.99  138.52  138.52  143.38  153.17  156.77
  163.65  170.23   175.4   182.5  184.46  196.42  196.44  196.46  204.22  204.25
  216.45   224.3   224.3  227.96  242.55  242.55  247.41  247.41   259.9  263.67
  272.32  277.98  282.18  284.18  296.23  299.23  299.23  301.07 308.939 356.484
 408.512 458.397 509.257 557.315  561.28  561.28  571.05  571.05  579.66  590.61
  590.61  596.68  601.36  605.08  605.48  609.08  614.15   622.9   622.9  625.29
  625.29  633.13  633.69  635.18  645.16  645.16  650.13  650.13  652.96  660.27
  664.54   668.9   673.3   673.3  679.55     691     691  695.13  705.09  712.29
  715.06  725.31  725.31  727.62  727.62  736.33  740.73  740.73  748.35  753.72
  753.72  761.41  768.93  772.92  777.71     783  789.73  796.28  796.28   798.4
   798.4  801.34  810.71     817  819.06   828.1  830.25  832.75  838.86  846.23
  850.48  857.11  857.95  859.53  859.53  866.75  876.04  876.04  879.93  879.93
  893.81  897.02  904.15  908.22  912.26  917.22  927.82  927.82  928.65  928.65
  929.81  929.81   941.6  949.29   955.5  967.07     968   968.8  969.46  977.46
  983.08  983.08  992.85 1001.08 1001.08 1010.31
  133.92  133.95  133.92  134.25  134.25  134.26  133.95  133.38  133.38  133.37
  133.45  133.32  133.32  133.12  133.11  133.11   133.1  133.02   132.9  132.92
  132.92  132.94  132.94  132.89  132.89   132.9  132.91  132.91  132.67  132.64
  132.64  132.61  132.63  132.45  132.51  132.37  132.37  132.51  132.34  132.33
  132.38  132.36   132.3  132.27  132.28  132.37  132.37  132.37   132.3   132.3
  132.06  132.25  132.25  132.22  132.13  132.13  132.27  132.27  132.17  131.91
  132.23  132.13  131.93  131.92  131.89  131.88  131.88  131.87  132.37  132.31
  132.46  132.59  132.81  132.99  132.57  132.57  132.64  132.64  132.69  132.71
  132.71  132.66  132.78  132.77  132.78  132.85  132.92  133.02  133.02  133.12
  133.12  133.32  133.28  133.29  133.13  133.13  133.33  133.33  133.38  133.42
  133.44  133.51  133.46  133.46  133.57  133.77  133.77  133.87  134.04  134.05
  134.11  134.09  134.09  134.08  134.08  134.31  134.38  134.38  134.57  134.56
  134.56  134.67  134.64  134.71  134.83  134.91  134.91  135.15  135.15  135.16
  135.16  135.24   135.3  135.33  135.34  136.08   136.1  136.07   135.7  135.84
   135.8  136.26  136.28  136.34  136.34   136.4  136.43  136.43  136.46  136.46
  136.57  136.66  136.72  136.71   136.8   136.9  136.96  136.96  136.96  136.96
  136.99  136.99   137.3  137.42  137.49  137.63  137.63  137.65  137.66  137.65
  137.68  137.68  137.78  137.97  137.97  138.02
                                                                                
                                                                                
                                                                                
                                                                                
                                                                                
                                                                                
                                                                                
                                                                                
                                                                                
                                                                                
                                                                                
                                                                                
                                                                                
                                                                                
                                                                                
                                                                                
                                                                                
                                                
BR Coef=-1 , 0 , 0 ,, 0 ,,,0.8,-1,,0,
WSPro=,,,, 1 ,,,, 0 ,,,, 0 ,,,,-1 ,-1 ,-1 , 0 , 0 , 0 , 0 , 0
Multiple Barrel Culv=2,10,12,101.5,0.012,0.4,1,8,1,116.4306,116.3539, 3,Culvert #1  , 0 ,14.7
  414.51  416.04  427.01  428.57  439.51  441.04
Culvert Bottom n=0.012
BC Design=,, 0 ,, 0 ,,,,,,
BC Use User HTab Curves=0
BC User HTab FreeFlow(D)= 0

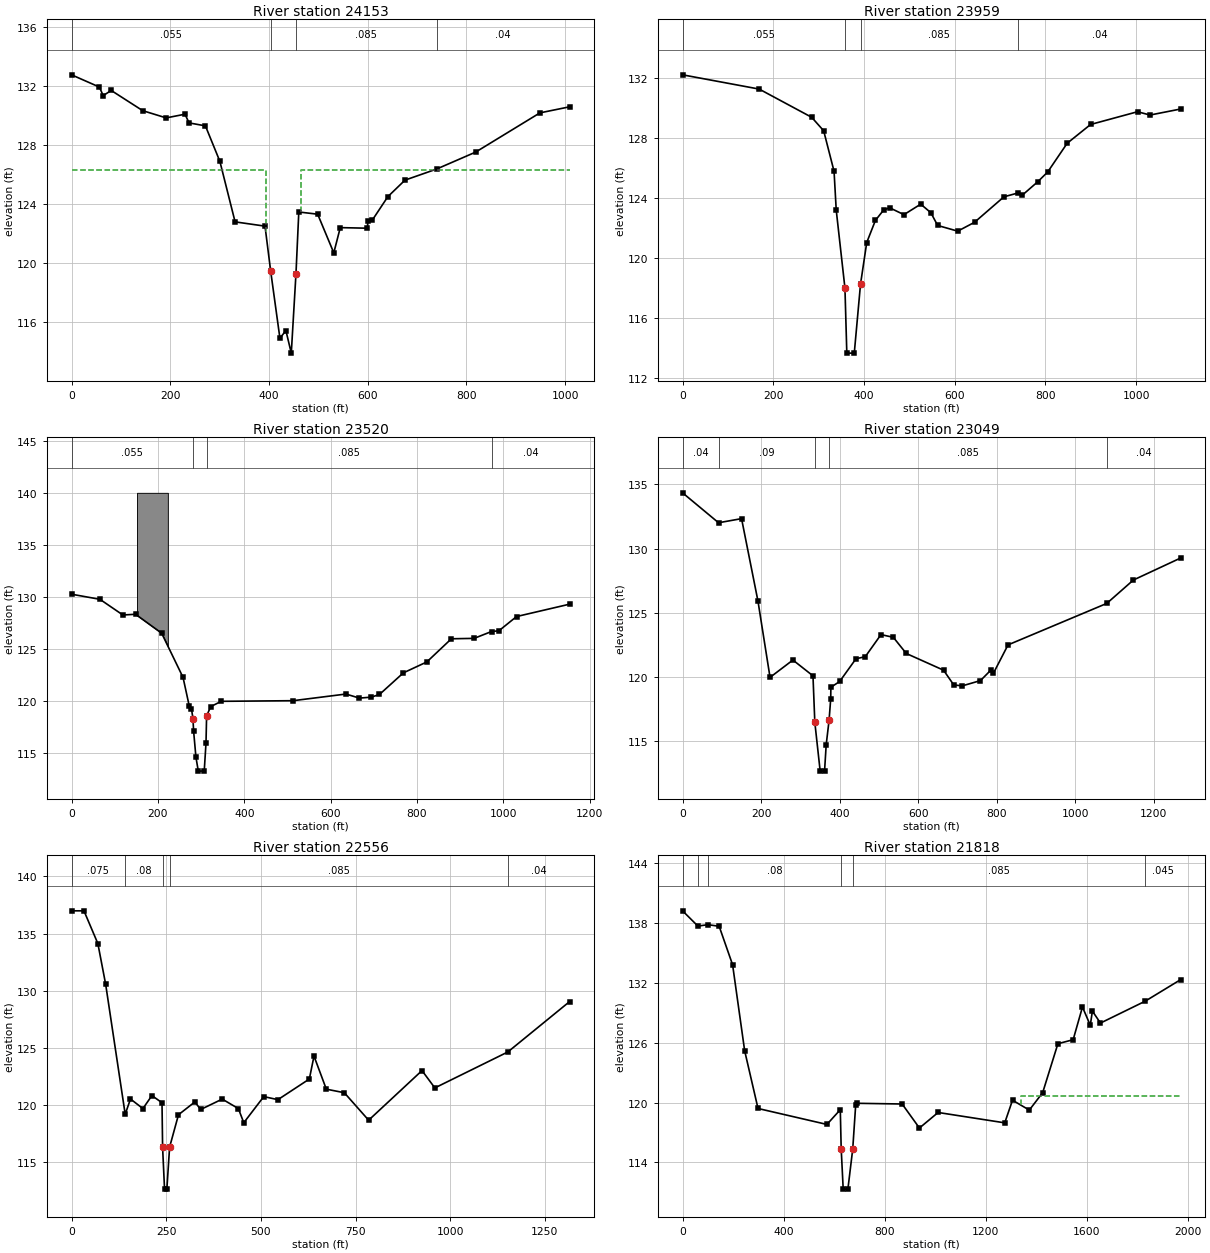
Type RM Length L Ch R = 1 ,24153   ,182.93,193.69,191.46
BEGIN DESCRIPTION:
Surveyed Section
END DESCRIPTION:
XS GIS Cut Line= 6
 2298838.3699146  733632.3214816 2298733.4194416  733410.7232592
      2298677.08     733275.6037     2298628.843     733180.6638
 2298527.3565595  732924.2987515 2298407.5705666  732722.8561914
#Sta/Elev= 30
       0  132.77   56.39  131.94   64.03  131.36   80.37  131.71  144.12  130.34
  191.69  129.85  229.75   130.1   238.1  129.51  271.17  129.31  300.49   126.9
  331.28   122.8 391.899  122.51 403.373  119.46 422.094  114.91 434.221  115.43
 445.126   113.9 454.623  119.28 460.346  123.47 498.581  123.32 531.239   120.7
 544.347  122.41 599.301  122.37  600.18  122.87  608.89   122.9   640.8  124.51
  675.47  125.63  739.45  126.38  818.62  127.53  948.81  130.19  1008.8   130.6
#Mann= 4 ,-1 , 0
       0    .055       0 403.373     .05       0 454.623    .085       0
  739.45     .04       0
#XS Ineff= 2 , 0
       0 393.373  126.35 464.623       0  126.35
Permanent Ineff=
       F       F
Bank Sta=403.373,454.623
XS Rating Curve= 0 ,0
Exp/Cntr=0.5,0.3

Type RM Length L Ch R = 1 ,23959   ,450.18,439.94,418.06
XS GIS Cut Line= 6
 2298949.7984958  733591.4434501 2298919.8934108  733511.1719062
 2298886.8404222  733385.2557589 2298836.4739633  733168.0504048
 2298754.6284675  733016.9510281 2298437.8020997  732647.2773584
#Sta/Elev= 30
       0  132.24  168.91  131.29   284.6  129.41  311.05  128.51  333.92  125.81
  338.74  123.22  357.94  118.02  362.06  113.69  378.51  113.69  392.23  118.28
  405.94  121.06  425.14  122.54  442.97  123.22  456.32  123.38  488.02  122.92
  524.96  123.62   547.3  123.05  562.25   122.2  606.54  121.82  643.51  122.41
  708.44  124.11  740.11  124.37  749.26  124.23  782.82  125.11  804.75  125.76
  847.83  127.68  899.38  128.93 1002.85  129.78 1030.45  129.56 1097.62  129.96
#Mann= 4 ,-1 , 0
       0    .055       0  357.94     .05       0  392.23    .085       0
  740.11     .04       0
Bank Sta=357.94,392.23
XS Rating Curve= 0 ,0
Exp/Cntr=0.3,0.1

Type RM Length L Ch R = 1 ,23520   ,434.47,470.81,287.92
XS GIS Cut Line= 6
 2299261.6113792  733231.7536668 2299212.6484533   733007.507317
 2299093.0281134  732780.8582519 2298872.6748556   732571.522657
 2298767.2200823  732529.0259573 2298523.4581105  732491.0811036
#Sta/Elev= 30
       0  130.24   65.67  129.75  118.85  128.24  148.17  128.31  208.56  126.49
  258.15  122.23  272.51  119.48  277.68  119.21  281.15  118.24  282.51  117.11
     288  114.55  293.48  113.21   307.2  113.22  311.31  115.92  312.69  118.53
  322.29  119.42  346.52  119.93  512.91  119.99  635.29  120.63  666.51  120.24
  693.94  120.33  713.03  120.59  768.33  122.67  822.64  123.72  879.49  125.95
  932.21  125.99   972.5  126.65  989.55  126.72 1030.39  128.09 1153.07  129.28
#Mann= 4 ,-1 , 0
       0    .055       0  281.15     .05       0  312.69    .085       0
   972.5     .04       0
#Block Obstruct= 1 ,-1
  151.61  222.96     140
Bank Sta=281.15,312.69
XS Rating Curve= 0 ,0
Exp/Cntr=0.3,0.1

Type RM Length L Ch R = 1 ,23049   ,481.64,492.45,372.48
XS GIS Cut Line= 6
 2299656.4467713  732766.7823557 2299425.7303652  732674.4957933
 2299281.1480841  732566.8281372 2299028.8981469  732431.4745123
 2298865.8585533  732354.5690436 2298493.2265773  732360.0777931
#Sta/Elev= 30
       0  134.35   91.67  132.02  150.22  132.34  191.99  125.92  222.74  119.98
  280.99  121.33  332.08   120.1   336.8  116.47  350.39  112.68  361.56  112.68
  365.74  114.74  373.05  116.63  377.23  118.31  377.69  119.21  400.02  119.66
  441.59  121.43  465.22  121.59  505.25  123.31  536.67   123.1  569.71  121.84
  664.58  120.54  690.61  119.39  712.33  119.32  758.58  119.73   786.1  120.58
  791.69  120.31  828.78  122.51 1080.27  125.74 1147.93  127.56 1267.97  129.27
#Mann= 5 ,-1 , 0
       0     .04       0   91.67     .09       0   336.8     .05       0
  373.05    .085       0 1080.27     .04       0
Bank Sta=336.8,373.05
XS Rating Curve= 0 ,0
Exp/Cntr=0.3,0.1

Type RM Length L Ch R = 1 ,22556   ,565.8,738.4,729.09
XS GIS Cut Line= 5
 2299693.3613963  732231.5202937  2299416.501709  732176.1483563
 2299096.5749593  732080.7855751 2298890.4683033  732022.3374189
  2298410.089861  732085.4746999
#Sta/Elev= 30
       0  136.99   32.74  136.99   69.45  134.12   90.04  130.55  141.62  119.16
  155.55   120.5   188.4  119.66  212.17   120.8  238.82  120.17   240.4  116.25
  245.46  112.64  251.63   112.6  258.89  116.28  282.34  119.12  325.53  120.24
  341.02  119.58  397.86  120.49  440.45  119.66  454.77  118.42  507.58  120.71
  544.84  120.44  627.89  122.25  640.18  124.26   672.7  121.36  720.18  121.05
  784.47  118.64  925.39  122.99  959.28  121.47    1152  124.62 1314.92  129.03
#Mann= 5 ,-1 , 0
       0    .075       0  141.62     .08       0   240.4     .05       0
  258.89    .085       0    1152     .04       0
#XS Ineff= 2 , 0
       0                  640.18       0  124.26
Permanent Ineff=
       F       F
Bank Sta=240.4,258.89
XS Rating Curve= 0 ,0
Exp/Cntr=0.3,0.1

Type RM Length L Ch R = 1 ,21818   ,746.56,834.84,658.81
XS GIS Cut Line= 6
 2299853.3247711  732006.9563252 2299810.2577086  731859.2978253
 2299527.2455839  731597.8192318  2299161.175553  731453.2369507
 2298598.2275223  731068.7096073 2298330.5964913  730834.9169826
#Sta/Elev= 30
       0  139.23   60.69   137.7  100.64  137.84   144.8  137.68  197.96  133.82
   245.7  125.19  298.55   119.4  571.14   117.8  624.09  119.28  627.58  115.38
  635.55  111.32  654.14  111.31  673.25  115.32  685.09  119.79  691.04  119.92
  868.81  119.85  937.15  117.44 1011.11     119 1274.75  117.96 1305.43  120.23
 1371.91  119.24 1424.82  120.99 1485.08   125.9 1545.39   126.3 1582.24  129.58
 1613.16  127.75 1621.52  129.17 1653.45  127.97 1830.09  130.16 1970.19  132.32
#Mann= 6 ,-1 , 0
       0     .09       0   60.69    .075       0  100.64     .08       0
  627.58     .05       0  673.25    .085       0 1830.09    .045       0
#XS Ineff= 2 , 0
       0                 1338.12       0  120.65
Permanent Ineff=
       F       F
Bank Sta=627.58,673.25
XS Rating Curve= 0 ,0
Exp/Cntr=0.3,0.1