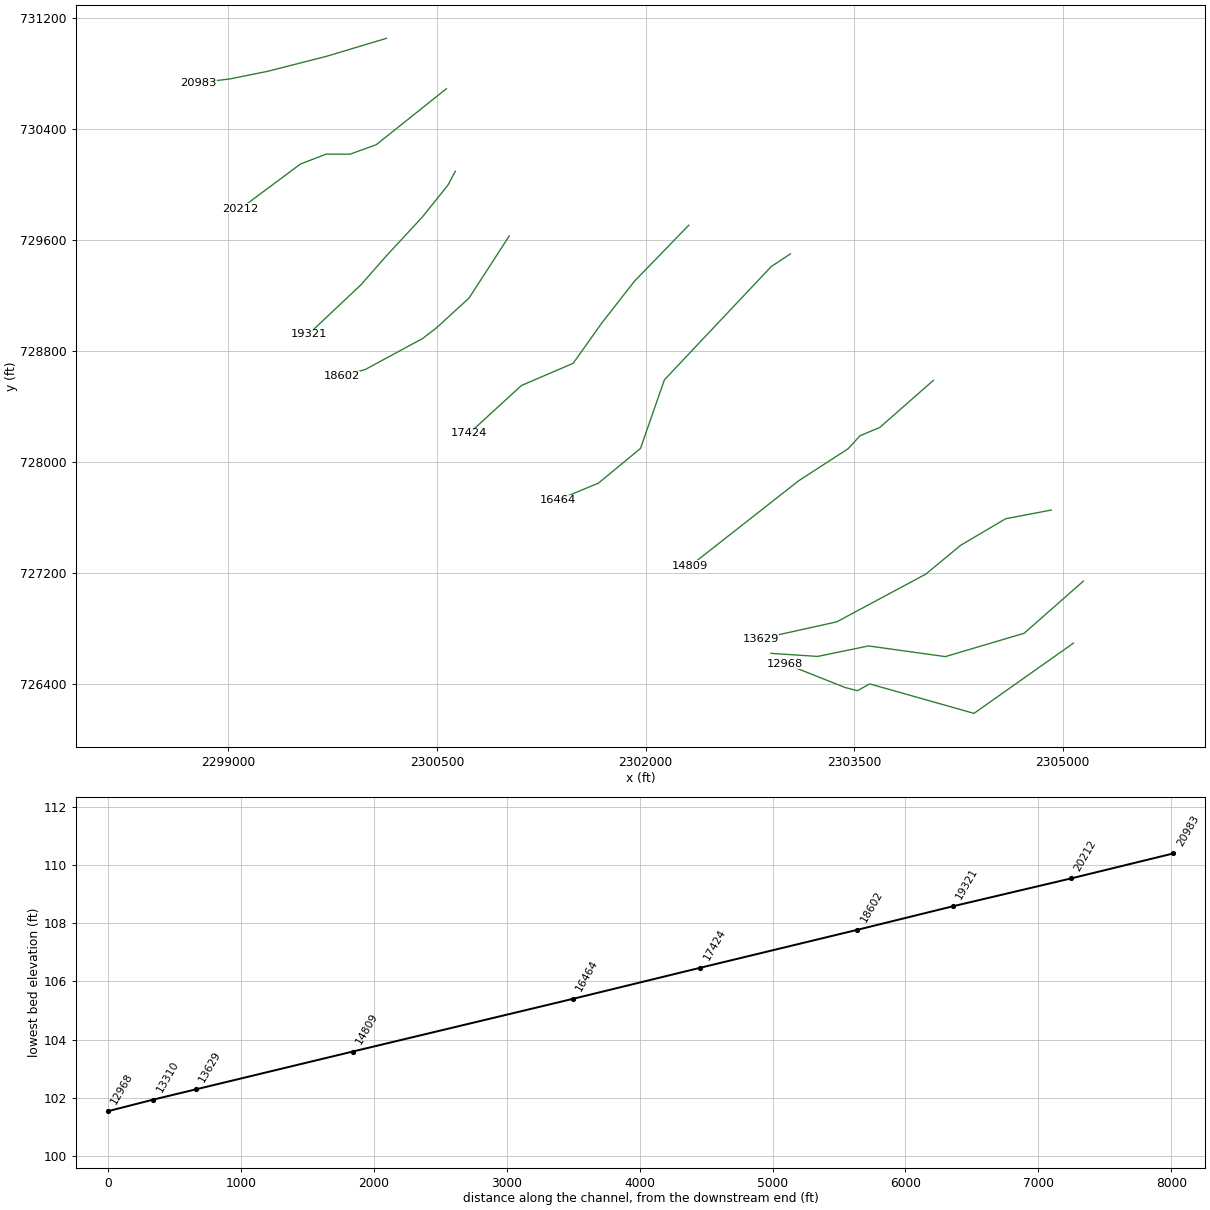
HEC-RAS study dtl_Bloomery_Swamp.prj: DTL_Bloomery_Swamp

--- dtl_Bloomery_Swamp.g01 (geometry) --- (continued)

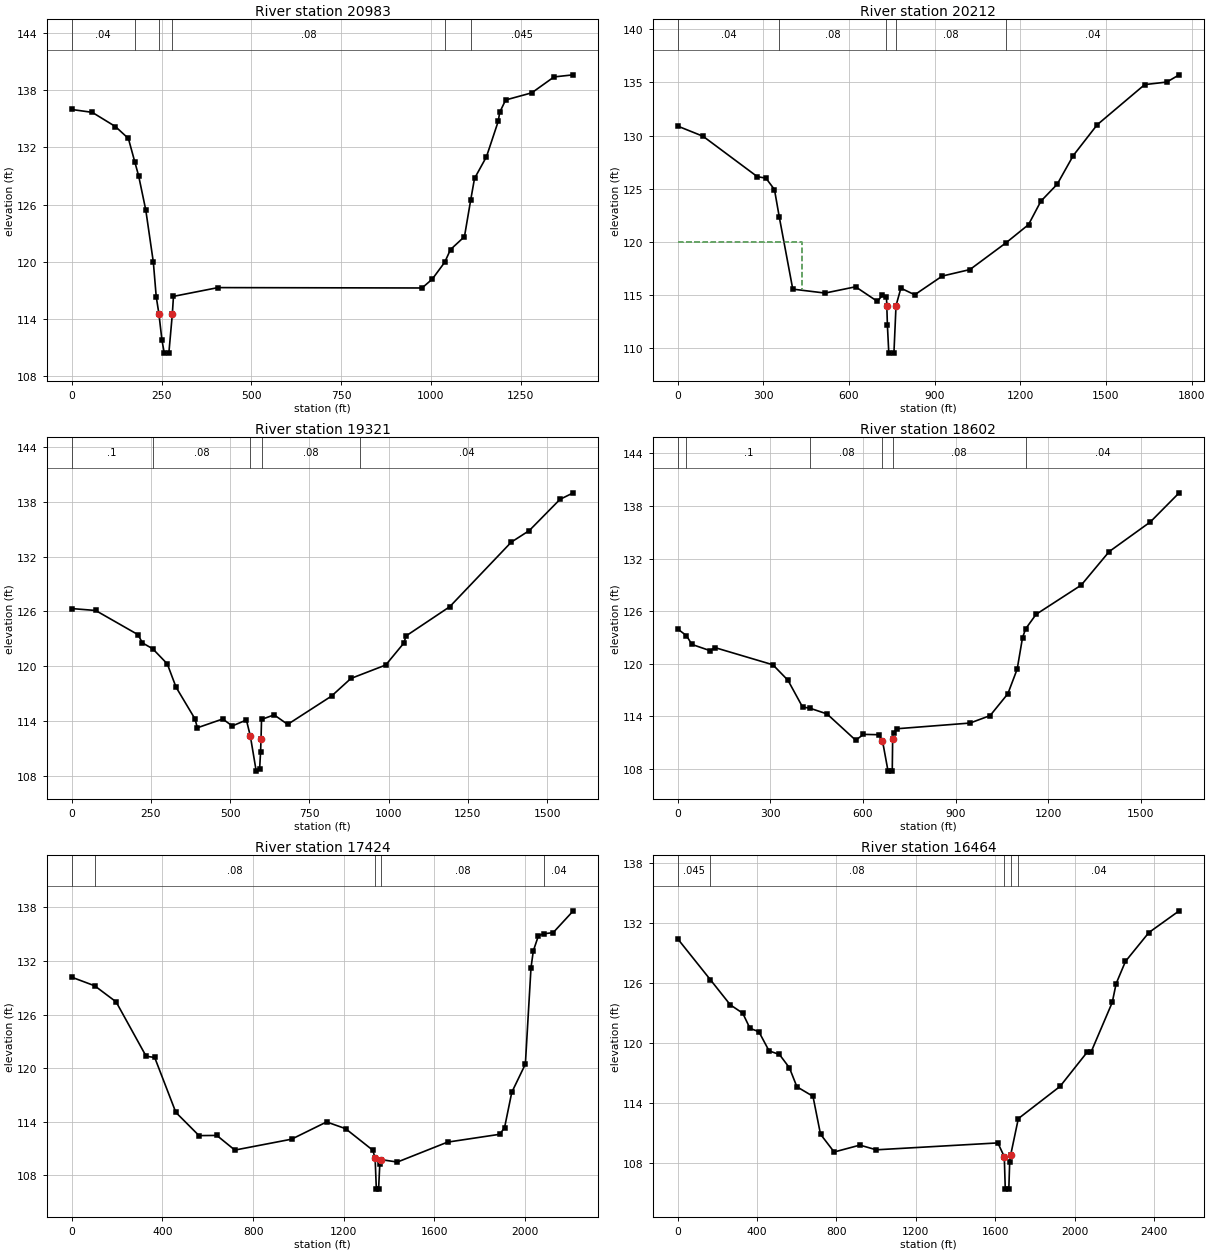
Type RM Length L Ch R = 1 ,20983   ,702.86,770.55,731.23
XS GIS Cut Line= 5
 2300136.3368959  731050.2522949 2299705.6662713  730921.0511075
 2299284.2243029  730813.3834513 2299010.4408344  730758.0115139
 2298779.7244284  730730.3255452
#Sta/Elev= 30
       0  135.98   57.09  135.68  121.55  134.19  157.67  132.94  175.38   130.5
  186.17  129.02   206.1  125.43   227.2  119.94   235.2  116.32  242.55  114.56
   251.2  111.75   257.6   110.4   270.4  110.42     280  114.48   283.2  116.36
  407.24  117.28  975.15  117.24 1003.49  118.16 1038.16  119.93 1054.58  121.28
  1093.3  122.63 1110.48  126.43  1121.3  128.74  1154.6  131.02 1187.42  134.75
 1191.38  135.68 1208.03  136.98  1280.7  137.73 1342.71   139.4 1396.31  139.62
#Mann= 6 ,-1 , 0
       0     .04       0  175.38     .08       0  242.55     .05       0
     280     .08       0 1038.16    .032       0 1110.48    .045       0
Bank Sta=242.55,280
XS Rating Curve= 0 ,0
Exp/Cntr=0.3,0.1

Type RM Length L Ch R = 1 ,20212   ,686.36,891.13,844.25
XS GIS Cut Line= 6
 2300567.0075204  730687.2584827 2300062.5076459  730284.2738269
 2299874.8583023  730216.5970144 2299702.5900525  730216.5970144
 2299518.0169276  730145.8439832 2299084.2700843  729822.8410148
#Sta/Elev= 30
       0   130.9   89.04  129.94  279.08  126.14   309.2     126  339.09  124.93
  356.02  122.34   403.2  115.56  516.29  115.19  623.17  115.78  699.45  114.41
  716.75  114.97  731.39  114.78   732.5  114.01  734.65  112.14  739.53  109.54
  757.43  109.54  764.81  114.01  781.84  115.65  830.24  115.03  926.68  116.79
 1023.53   117.4  1150.6  119.93 1228.82  121.63    1272  123.83 1329.26  125.43
 1385.57  128.13 1469.18  131.02 1635.63   134.8 1712.98  135.04 1756.37  135.72
#Mann= 5 ,-1 , 0
       0     .04       0  356.02     .08       0  731.39     .05       0
  764.81     .08       0  1150.6     .04       0
#XS Ineff= 2 , 0
       0     435     120               0
Permanent Ineff=
       F       F
Bank Sta=732.5,764.81
XS Rating Curve= 0 ,0
Exp/Cntr=0.3,0.1

Type RM Length L Ch R = 1 ,19321   ,668.3,719.81,681.12
XS GIS Cut Line= 6
 2300631.6081141  730093.5482645 2300579.3123954  729995.1092646
 2300394.7392706  729764.3928586 2300130.1844584  729478.3045151
  2299951.763771  729275.2740778 2299576.4650839  728921.5089219
#Sta/Elev= 30
       0  126.32   75.43  126.11  209.17  123.47  223.12  122.57  255.59  121.93
  301.55  120.28  329.12  117.74  389.03  114.27  396.33  113.31  476.45  114.27
  506.52  113.51  551.16  114.16  563.75  112.37  582.08  108.58  592.77  108.77
  595.83  110.66  597.36  112.14  598.88  114.22   638.6  114.72  681.36  113.68
  819.73  116.77  880.79  118.69  990.77  120.16 1047.64  122.54 1055.16  123.34
 1192.72  126.52 1386.99  133.57 1443.76  134.83 1540.75  138.24 1582.63  138.95
#Mann= 5 ,-1 , 0
       0      .1       0  255.59     .08       0  563.75     .05       0
  598.88     .08       0  910.01     .04       0
Bank Sta=563.75,597.36
XS Rating Curve= 0 ,0
Exp/Cntr=0.3,0.1

Type RM Length L Ch R = 1 ,18602   ,1043.49,1177.63,856.22
XS GIS Cut Line= 6
 2301019.3873186  729627.7893728  2300730.495514  729180.9098625
 2300493.5139554   728964.241009 2300396.4643648  728889.7610906
 2299983.4393629  728666.3213355 2299814.1668211  728618.9250237
#Sta/Elev= 30
       0  123.98   28.59  123.21   46.34  122.21   105.2   121.5  120.88  121.85
  308.57  119.89  357.25  118.13   404.6  115.08  429.47  114.93  483.81  114.29
  576.78  111.29  601.89  111.96  651.35  111.92  663.42  111.24  681.53  107.77
  695.12  107.77  696.41  111.44  699.65  112.17  710.21   112.6  947.06  113.25
 1012.11   114.1 1069.58  116.59 1099.77   119.4 1117.03  122.98 1127.35     124
 1161.01  125.64 1307.13  128.97 1397.64  132.79 1530.99  136.17 1624.42  139.49
#Mann= 6 ,-1 , 0
       0     .08       0   28.59      .1       0  429.47     .08       0
  663.42     .05       0  696.41     .08       0 1127.35     .04       0
Bank Sta=663.42,696.41
XS Rating Curve= 0 ,0
Exp/Cntr=0.3,0.1

Type RM Length L Ch R = 1 ,17424   ,628.62,959.61,889.37
XS GIS Cut Line= 6
  2302310.668899  729704.9353346 2301919.9618931  729301.7257045
 2301685.5376896   729001.662724 2301479.2443904  728710.9767116
 2301107.2913208  728551.5682532 2300732.2125952   728207.746088
#Sta/Elev= 30
       0  130.19  101.11  129.23  195.72  127.43  328.19  121.34  365.83  121.21
  459.23  115.06  561.45  112.46     640  112.48  719.46  110.84  969.72  112.06
 1124.31  113.99  1207.8  113.24 1328.31  110.82 1338.36   109.9  1343.7  106.47
 1353.58  106.47 1358.99  109.27 1364.96  109.77 1436.37   109.5 1657.74  111.73
 1888.44  112.61 1909.37  113.36  1941.2  117.31 2001.09  120.46 2026.02  131.27
 2036.22  133.14 2058.85  134.84 2082.21  135.05 2123.78  135.18 2212.52  137.62
#Mann= 5 ,-1 , 0
       0    .045       0  101.11     .08       0 1338.36     .05       0
 1364.96     .08       0 2082.21     .04       0
#XS Ineff= 2 , 0
       0    1140                       0
Permanent Ineff=
       F       F
Bank Sta=1338.36,1364.96
XS Rating Curve= 0 ,0
Exp/Cntr=0.3,0.1

Type RM Length L Ch R = 1 ,16464   ,1226.9,1655.02,1000.39
XS GIS Cut Line= 6
 2303042.0724141  729498.6420355  2302904.543548  729407.9980101
 2302135.6321604  728592.2017818 2301963.7210778  728098.3481263
 2301660.5324412  727848.2956426 2301366.7207727  727726.3950567
#Sta/Elev= 30
       0  130.43  164.71  126.34  265.46  123.82  327.94  122.99  364.68  121.47
  409.23  121.14  460.75  119.22  512.93  118.86  563.27  117.53  601.01  115.63
  681.96  114.68  719.93  110.89  788.63  109.11  918.37   109.8 1001.01  109.33
 1613.56  110.02 1645.97  108.64 1650.95   105.4 1668.81   105.4 1673.27  108.16
 1677.75  108.77 1716.74  112.45 1926.95  115.67 2062.77  119.07 2083.22   119.1
  2189.9  124.06  2209.5  125.94 2256.73  128.17 2374.65  131.05 2527.21  133.22
#Mann= 5 ,-1 , 0
       0    .045       0  164.71     .08       0 1645.97     .05       0
 1677.75    .085       0 1716.74     .04       0
#XS Ineff= 2 , 0
       0    1170                       0
Permanent Ineff=
       F       F
Bank Sta=1645.97,1677.75
XS Rating Curve= 0 ,0
Exp/Cntr=0.3,0.1

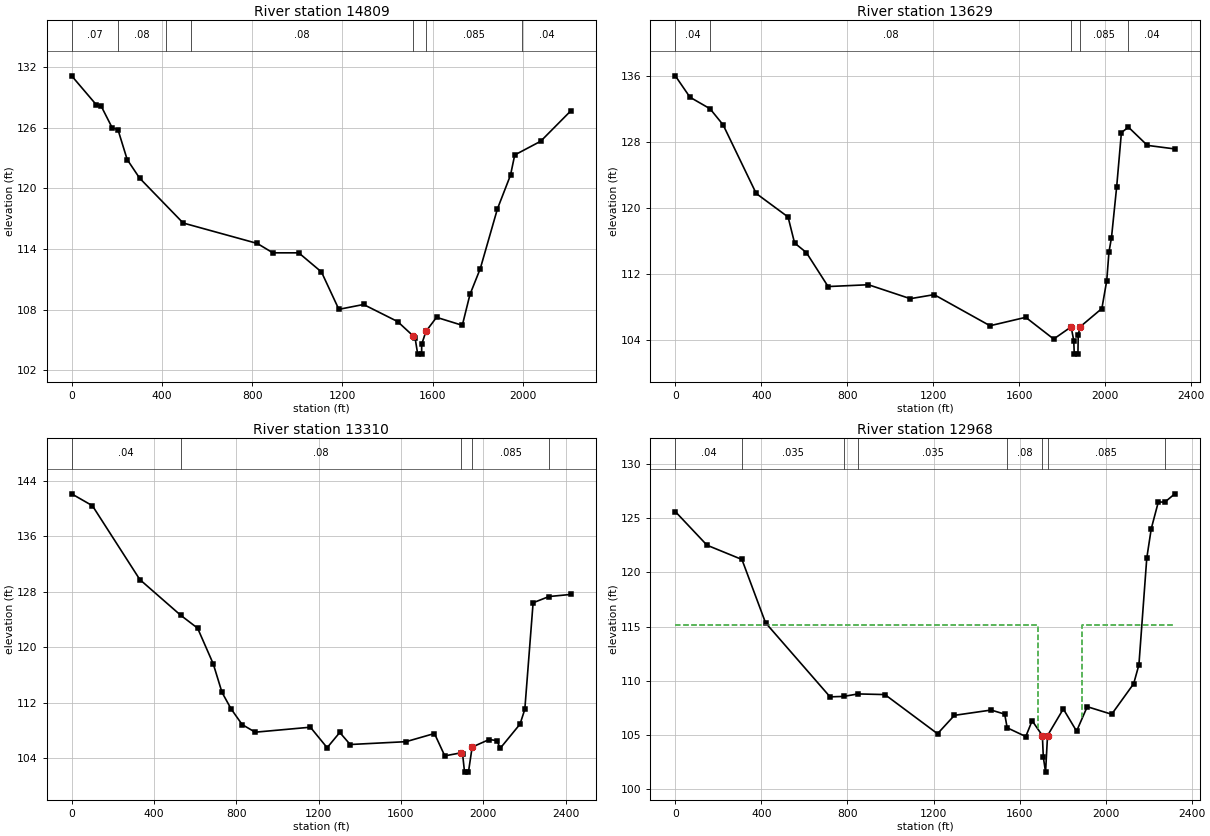
Type RM Length L Ch R = 1 ,14809   ,1084.48,1180.6,893.53
XS GIS Cut Line= 6
 2304070.8039607  728588.6854187 2303684.0040248  728248.7703236
 2303543.3495026  728190.1642727 2303457.3939613  728096.3945913
  2303101.850586  727865.8774578 2302320.4365742  727252.4674585
#Sta/Elev= 30
       0  131.12   109.9  128.24  130.98  128.12  179.63  125.98   205.2   125.8
  246.11  122.84  301.22     121  494.23  116.56  822.47  114.54   891.7  113.61
 1006.34  113.61 1106.99  111.72 1184.16  108.02  1293.6   108.5 1444.69  106.81
 1512.99   105.4 1522.17  105.16 1533.52  103.59 1551.02  103.59 1551.02  104.55
  1570.1  105.84 1617.01  107.23 1731.22  106.44 1765.12  109.49 1811.02  112.06
 1886.87  117.96 1944.89   121.3 1963.44  123.29 2078.58  124.65  2213.6  127.69
#Mann= 7 ,-1 , 0
       0     .07       0   205.2     .08       0  418.37     .07       0
  528.39     .08       0 1512.99     .05       0  1570.1    .085       0
 1993.79     .04       0
Bank Sta=1512.99,1570.1
XS Rating Curve= 0 ,0
Exp/Cntr=0.3,0.1

Type RM Length L Ch R = 1 ,13629   ,532.31,318.22,230.44
XS GIS Cut Line= 6
 2304918.6381635  727654.8956746 2304590.4442785  727592.3825537
 2304266.1574636  727400.9361208 2304016.1049798  727193.8614077
 2303375.3454901  726850.0392424 2302828.3556818  726728.9200706
#Sta/Elev= 30
       0  136.02   68.19  133.43   161.5  132.03  222.41  130.08  376.39  121.76
  524.64  118.91  554.82  115.76  609.68   114.6  710.87  110.48  898.29   110.7
 1093.31  109.01 1204.08   109.5 1464.03  105.73 1630.06  106.75 1760.18  104.12
 1841.35  105.59 1853.52  103.94 1855.96  102.29 1873.01  102.29 1874.31  104.59
 1882.76  105.59 1984.38  107.82 2007.04   111.2 2017.34  114.67 2029.09  116.41
 2053.26  122.58 2075.19  129.14  2107.9   129.8 2195.97  127.59 2323.71  127.16
#Mann= 5 ,-1 , 0
       0     .04       0   161.5     .08       0 1841.35     .05       0
 1882.76    .085       0  2107.9     .04       0
#XS Ineff= 2 , 0
       0    1219                       0
Permanent Ineff=
       F       F
Bank Sta=1841.35,1882.76
XS Rating Curve= 0 ,0
Exp/Cntr=0.3,0.1

Type RM Length L Ch R = 1 ,13310   ,417.52,342.79,224.12
XS GIS Cut Line= 6
 2305149.1552969  727143.0694969 2304723.2846605  726767.9907712
  2304156.759502  726599.9867586 2303604.1753524  726676.6971126
  2303237.838842  726601.2748899  2302902.590013   726623.429179
#Sta/Elev= 30
       0  142.15  100.94  140.43  331.38  129.76  529.71  124.61  612.07  122.74
  688.21  117.57  730.47  113.47   774.9  111.07  828.54  108.81  891.94  107.71
    1160  108.43 1241.43  105.47 1302.86  107.67 1353.42  105.93 1624.71  106.34
 1762.86  107.52  1813.1  104.29 1892.48  104.73  1899.7  104.54 1909.08  101.94
 1928.06  101.94 1946.12  105.56 2028.77  106.65 2066.72   106.5  2082.1  105.37
 2178.84  108.88 2201.97  111.02 2242.26  126.41 2319.45  127.31 2427.19  127.62
#Mann= 5 ,-1 , 0
       0     .04       0  529.71     .08       0 1892.48     .05       0
 1946.12    .085       0 2319.45     .04       0
#XS Ineff= 2 , 0
       0    1397                       0
Permanent Ineff=
       F       F
Bank Sta=1892.48,1946.12
XS Rating Curve= 0 ,0
Exp/Cntr=0.5,0.3

Type RM Length L Ch R = 1 ,12968   ,142.35,190.58,123.72
BEGIN DESCRIPTION:
Surveyed Section
END DESCRIPTION:
XS GIS Cut Line= 6
 2305078.1525993  726697.0681347 2304362.5772582  726191.3948936
    2303612.4721     726403.5896    2303524.1376     726354.6045
 2303435.8915502  726377.3859276 2303000.8703995   726550.378189
#Sta/Elev= 30
       0  125.63  147.34  122.52  309.69   121.2  419.34  115.35   719.2   108.5
  782.38  108.54   849.2  108.77  974.29  108.71 1218.71  105.09 1297.14  106.79
 1467.96  107.28 1530.88   106.9 1542.39  105.64 1628.86  104.831658.291  106.29
 1705.97  104.921710.305  102.931720.795  101.541729.953  104.92 1803.21  107.38
 1864.98  105.33  1914.4  107.59    2028  106.89 2130.15  109.71 2154.59  111.46
 2191.15  121.33 2212.01  124.05 2244.71  126.51 2275.52  126.51 2321.48  127.27
#Mann= 8 ,-1 , 0
       0     .04       0  309.69    .035       0  782.38     .08       0
   849.2    .035       0 1542.39     .08       0 1705.97     .05       0
1729.953    .085       0 2275.52     .04       0
#XS Ineff= 2 , 0
       0    1684  115.16    1892       0  115.16
Permanent Ineff=
       F       F
Bank Sta=1705.97,1729.953
XS Rating Curve= 0 ,0
Exp/Cntr=0.5,0.3