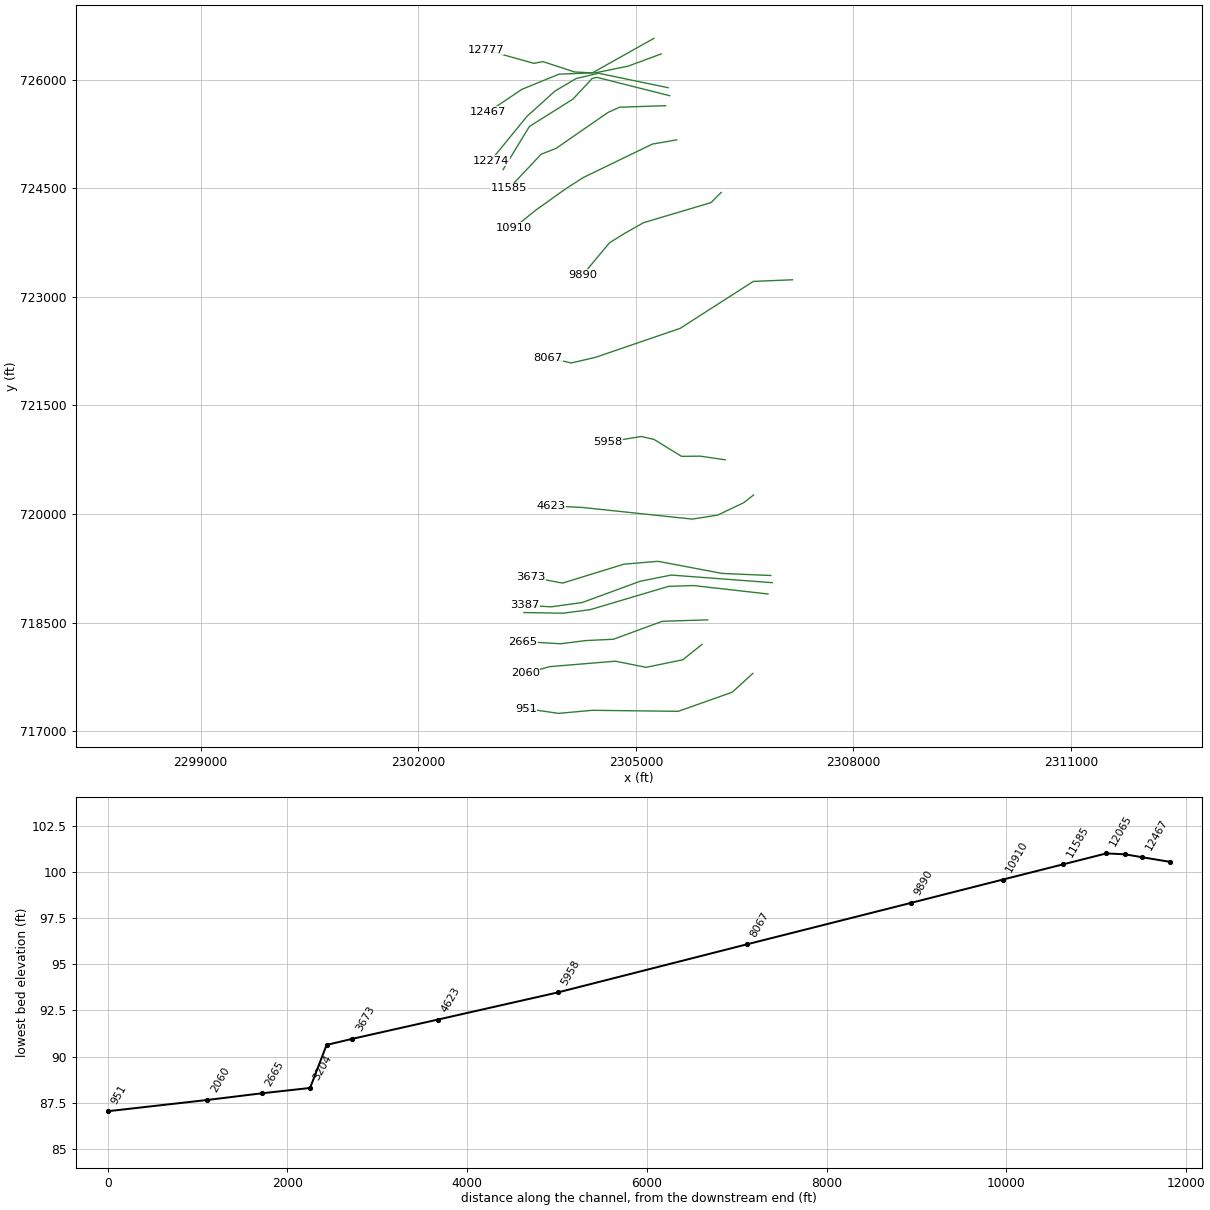
HEC-RAS study dtl_Bloomery_Swamp.prj: DTL_Bloomery_Swamp

--- dtl_Bloomery_Swamp.g01 (geometry) --- (continued)

Type RM Length L Ch R = 3 ,12833   ,,,
BEGIN DESCRIPTION:
Railroad
END DESCRIPTION:
Bridge Culvert--1,0,-1,-1, 0
Deck Dist Width WeirC Skew NumUp NumDn MinLoCord MaxHiCord MaxSubmerge Is_Ogee
133,12,2.6,0, 144, 144, , , 0.95, 0, 1,1,,
     -14  -11.62  -11.62  -10.37   -1.86    -.02   16.85   19.08   28.16   34.21
   38.14      47   51.47   59.14   66.49   69.15   77.36   77.36   78.31   79.92
   96.88    99.9    99.9     108  116.44   117.1  125.51  126.71  128.71  128.71
  140.63  145.64  146.76  147.34  156.68  157.24  158.89  170.36  179.43  184.81
  189.27  189.27  193.61     199  203.24  203.24  208.27   213.1  217.92  217.92
  225.92  230.11  233.11  240.77  243.98  248.98  254.73  262.72  263.19   264.5
  273.66  274.08  277.16  277.16  283.22  287.15  295.12   306.1  316.07  320.85
  320.85  323.48  330.38  333.29  341.77  347.88  352.94  360.42  366.09  366.09
  373.73  373.73  388.61  389.16  390.49  390.49  399.28  925.64  929.14  936.77
  936.77  942.84   958.9 1384.85 1654.36 1704.42 1704.42 1730.55 1781.78 1818.97
 1831.86 1872.42 1872.42 1922.12 2303.25 2308.34 2314.26 2318.49 2318.49 2337.25
 2338.74 2338.74 2341.22 2341.22 2349.28 2354.09 2362.61  2366.5 2377.81 2377.81
 2379.55 2379.55 2389.15 2389.15  2390.9 2408.45 2408.45 2410.81 2416.38 2424.17
 2431.88 2435.55 2435.55 2440.98  2449.1  2449.1 2454.58 2463.28 2474.33 2474.33
 2481.18 2481.18 2491.92 2498.87
  124.07  123.91  123.91  123.84  123.51  123.52  123.34  123.18  122.64   122.8
  122.82  122.39  122.18   122.1  121.99  121.93  122.02  122.02  121.95  121.93
   121.4  121.31  121.31  121.12  120.68  120.65  120.65  120.67  120.62  120.62
  120.49  120.49  120.45  120.44  120.62  120.61  120.52  119.94  119.76  119.95
  119.61  119.61  119.66  119.57  119.41  119.41  119.32  119.47  119.18  119.18
  119.01  118.92  118.95  118.94  118.87  118.73  118.77  118.49  118.47  118.41
  118.41   118.4   118.3   118.3  118.08  117.98  117.85  117.71  117.54  117.61
  117.61  117.57  117.46  117.39  117.17  117.09  117.07     117  116.78  116.78
   116.7   116.7  116.58  116.57  116.55  116.55  116.56  115.48  115.45  115.23
  115.23  115.44  115.45  114.48 115.733  115.99  115.99 116.168 116.381 116.531
 116.585 116.732 116.732 116.966  118.52  118.78  119.08  119.19  119.19  119.51
  119.47  119.47  119.56  119.56  119.52  119.51  119.49  119.45  120.16  120.16
  120.19  120.19  120.28  120.28  120.13  120.26  120.26  120.21  120.25  120.05
  120.62  120.69  120.69  120.81  120.91  120.91   120.8  120.76  120.79  120.79
  120.82  120.82   121.1   121.3
                                                                                
                                                                                
                                                                                
                                                                                
                                                                                
                                                                                
                                                                                
                                                                                
                                                                                
                                                  112.49 112.668 112.881 113.031
 113.085 113.232
                                                                                
                                                                                
                                                                                
                                
       0    2.38    2.38    3.63   12.14   13.98   30.85   33.08   42.16   48.21
   52.14      61   65.47   73.14   80.49   83.15   91.36   91.36   92.31   93.92
  110.88   113.9   113.9     122  130.44   131.1  139.51  140.71  142.71  142.71
  154.63  159.64  160.76  161.34  170.68  171.24  172.89  184.36  193.43  198.81
  203.27  203.27  207.61     213  217.24  217.24  222.27   227.1  231.92  231.92
  239.92  244.11  247.11  254.77  257.98  262.98  268.73  276.72  277.19   278.5
  287.66  288.08  291.16  291.16  297.22  301.15  309.12   320.1  330.07  334.85
  334.85  337.48  344.38  347.29  355.77  361.88  366.94  374.42  380.09  380.09
  387.73  387.73  402.61  403.16  404.49  404.49  413.28  939.64  943.14  950.77
  950.77  956.84   972.9 1398.85 1668.36 1718.42 1718.42 1744.55 1795.78 1832.97
 1845.86 1886.42 1886.42 1936.12 2317.25 2322.34 2328.26 2332.49 2332.49 2351.25
 2352.74 2352.74 2355.22 2355.22 2363.28 2368.09 2376.61  2380.5 2391.81 2391.81
 2393.55 2393.55 2403.15 2403.15  2404.9 2422.45 2422.45 2424.81 2430.38 2438.17
 2445.88 2449.55 2449.55 2454.98  2463.1  2463.1 2468.58 2477.28 2488.33 2488.33
 2495.18 2495.18 2505.92 2512.87
  124.07  123.91  123.91  123.84  123.51  123.52  123.34  123.18  122.64   122.8
  122.82  122.39  122.18   122.1  121.99  121.93  122.02  122.02  121.95  121.93
   121.4  121.31  121.31  121.12  120.68  120.65  120.65  120.67  120.62  120.62
  120.49  120.49  120.45  120.44  120.62  120.61  120.52  119.94  119.76  119.95
  119.61  119.61  119.66  119.57  119.41  119.41  119.32  119.47  119.18  119.18
  119.01  118.92  118.95  118.94  118.87  118.73  118.77  118.49  118.47  118.41
  118.41   118.4   118.3   118.3  118.08  117.98  117.85  117.71  117.54  117.61
  117.61  117.57  117.46  117.39  117.17  117.09  117.07     117  116.78  116.78
   116.7   116.7  116.58  116.57  116.55  116.55  116.56  115.48  115.45  115.23
  115.23  115.44  115.45  114.48 115.733  115.99  115.99 116.168 116.381 116.531
 116.585 116.732 116.732 116.966  118.52  118.78  119.08  119.19  119.19  119.51
  119.47  119.47  119.56  119.56  119.52  119.51  119.49  119.45  120.16  120.16
  120.19  120.19  120.28  120.28  120.13  120.26  120.26  120.21  120.25  120.05
  120.62  120.69  120.69  120.81  120.91  120.91   120.8  120.76  120.79  120.79
  120.82  120.82   121.1   121.3
                                                                                
                                                                                
                                                                                
                                                                                
                                                                                
                                                                                
                                                                                
                                                                                
                                                                                
                                                  112.49 112.668 112.881 113.031
 113.085 113.232
                                                                                
                                                                                
                                                                                
                                
Pier Skew, UpSta & Num, DnSta & Num=  ,1706.12, 2 ,1720.12, 2 , 0 , 0 , 0 ,,
       1       1
     100 113.232
       1       1
     100 113.232
Pier Skew, UpSta & Num, DnSta & Num=  ,1724.12, 2 ,1738.12, 2 , 0 , 0 , 0 ,,
       1       1
     100 113.232
       1       1
     100 113.232
Pier Skew, UpSta & Num, DnSta & Num=  ,1742.12, 2 ,1756.12, 2 , 0 , 0 , 0 ,,
       1       1
     100 113.232
       1       1
     100 113.232
Pier Skew, UpSta & Num, DnSta & Num=  ,1760.12, 2 ,1774.12, 2 , 0 , 0 , 0 ,,
       1       1
     100 113.232
       1       1
     100 113.232
Pier Skew, UpSta & Num, DnSta & Num=  ,1779.12, 2 ,1793.12, 2 , 0 , 0 , 0 ,,
       1       1
     100 113.232
       1       1
     100 113.232
Pier Skew, UpSta & Num, DnSta & Num=  ,1798.12, 2 ,1812.12, 2 , 0 , 0 , 0 ,,
       1       1
     100 113.232
       1       1
     100 113.232
Pier Skew, UpSta & Num, DnSta & Num=  ,1816.12, 2 ,1830.12, 2 , 0 , 0 , 0 ,,
       1       1
     100 113.232
       1       1
     100 113.232
Pier Skew, UpSta & Num, DnSta & Num=  ,1834.62, 2 ,1848.62, 2 , 0 , 0 , 0 ,,
       1       1
     100 113.232
       1       1
     100 113.232
Pier Skew, UpSta & Num, DnSta & Num=  ,1853.12, 2 ,1867.12, 2 , 0 , 0 , 0 ,,
       1       1
     100 113.232
       1       1
     100 113.232
Pier Skew, UpSta & Num, DnSta & Num=  ,1871.62, 2 ,1885.62, 2 , 0 , 0 , 0 ,,
       1       1
     100 113.232
       1       1
     100 113.232
Abutment Skew #Up #Dn= , 3 , 3
 1704.42 1705.12 1707.18
  112.49 108.051   104.4
 1718.42 1719.12 1720.97
  112.49 109.051   103.8
Abutment Skew #Up #Dn= , 3 , 3
 1867.98 1871.12 1872.42
  105.36 109.783  113.23
 1883.35 1885.12 1886.42
  106.02110.3434  113.23
BR Coef=-1 , 0 , 0 ,, 0 ,,,0.8,0,,0,
WSPro=,,,, 1 ,,,, 0 ,,,, 0 ,,,,-1 ,-1 ,-1 , 0 , 0 , 0 , 0 , 0
BC Design=,, 0 ,, 0 ,,,,,,
BC Use User HTab Curves=0
BC User HTab FreeFlow(D)= 0

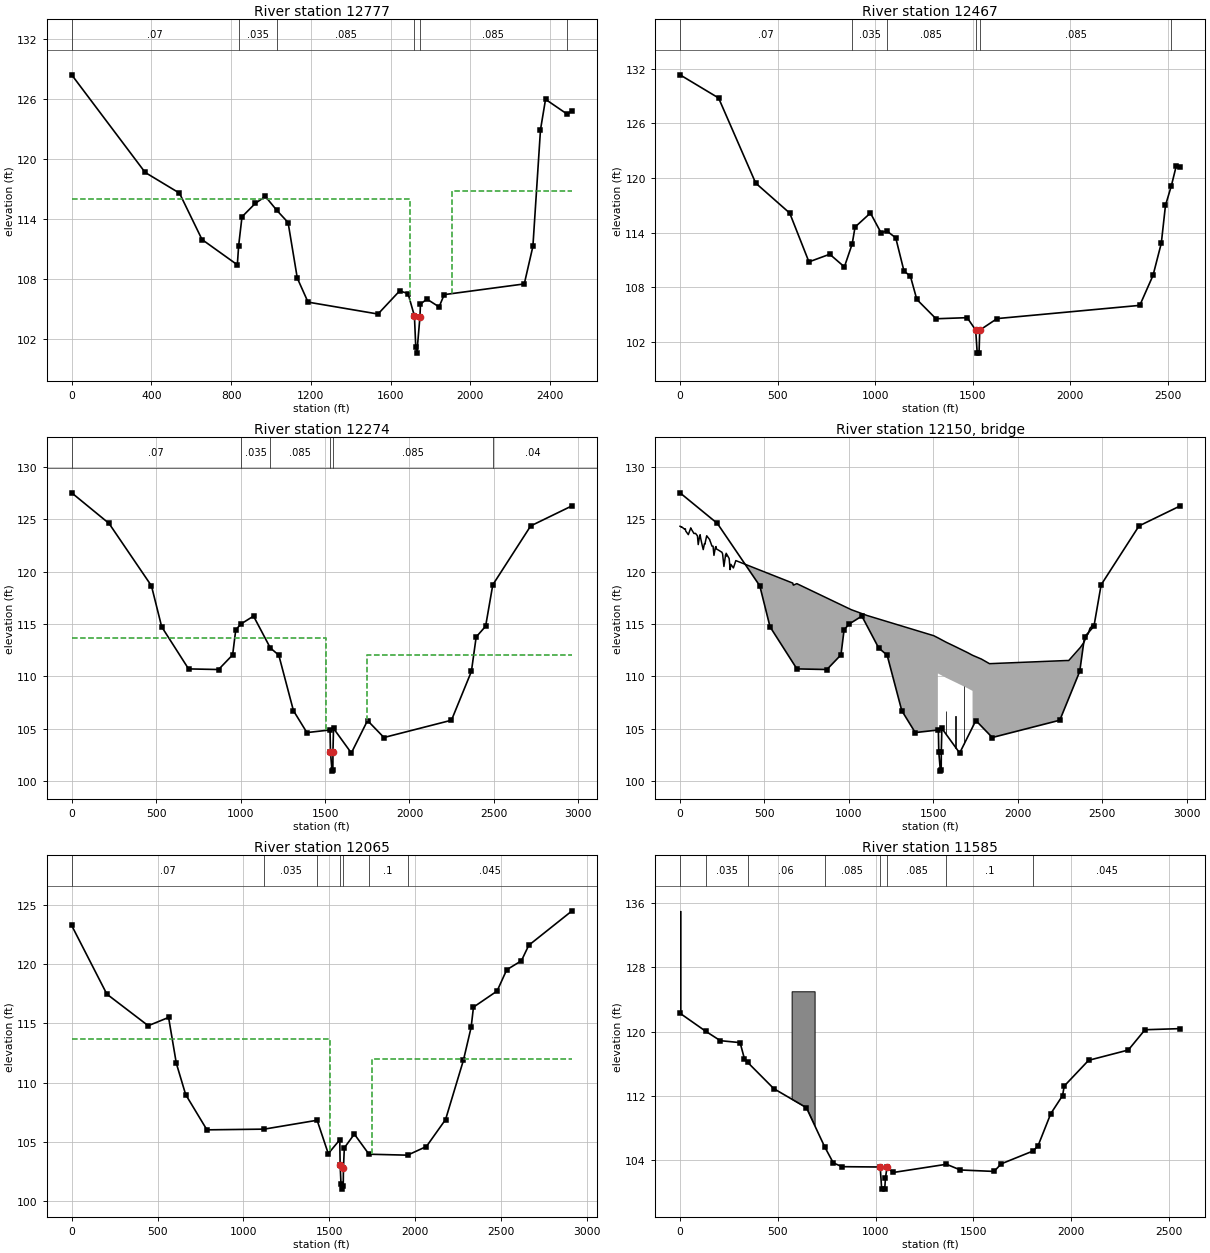
Type RM Length L Ch R = 1 ,12777   ,33.76,310.4,410.3
BEGIN DESCRIPTION:
Surveyed Section
END DESCRIPTION:
XS GIS Cut Line= 6
 2305249.8906812  726573.0350756 2304399.7768269  726095.3443171
 2304153.7175833   726108.774141    2303718.6184     726251.6098
    2303596.0996     726227.1534 2302929.1598678  726413.5765592
#Sta/Elev= 30
       0  128.37  368.55  118.61  540.73  116.54   653.9   111.9  831.13  109.37
  837.76   111.3  854.46  114.17     921  115.51   971.8  116.21 1029.56  114.81
 1085.75   113.6 1131.96  108.04 1185.83  105.64 1536.86  104.45 1645.37  106.76
1687.496   106.5 1719.66  104.251726.293  101.151731.859  100.54 1747.24  104.16
1749.979  105.451782.472  105.94 1843.38  105.16 1868.94  106.39  2270.7  107.46
 2313.99  111.21 2352.11  122.88 2377.46  125.92 2483.65  124.47 2510.51  124.74
#Mann= 6 ,-1 , 0
       0     .07       0  837.76    .035       0 1029.56    .085       0
 1719.66     .05       0 1747.24    .085       0 2483.65     .04       0
#XS Ineff= 2 , 0
       0    1698  115.99    1906       0  116.73
Permanent Ineff=
       F       F
Bank Sta=1719.66,1747.24
XS Rating Curve= 0 ,0
Exp/Cntr=0.5,0.3

Type RM Length L Ch R = 1 ,12467   ,19.9,192.69,298.63
XS GIS Cut Line= 6
 2305348.4635192  726356.9734672 2304894.6385341  726188.8048179
 2304449.3910814  726097.6680961 2303942.4380339   726077.916198
 2303432.1007398  725869.6152616 2302963.4236331  725554.5600954
#Sta/Elev= 30
       0  131.32  197.75  128.78  388.15  119.44  562.55  116.15  661.12   110.8
  767.85  111.64  842.87  110.25  882.93  112.78  897.54  114.62  976.37  116.16
 1030.82  113.99 1060.49  114.19 1106.14  113.44 1148.41   109.8 1181.38  109.23
 1214.23  106.68 1312.75  104.56 1472.42  104.68 1516.19  103.32 1523.97  100.79
 1533.36  100.79 1536.97  103.31 1626.01  104.58 2357.73  106.03 2425.56  109.32
 2468.08  112.86 2489.33  116.99 2519.71  119.16 2544.97  121.35  2565.9  121.23
#Mann= 6 ,-1 , 0
       0     .07       0  882.93    .035       0 1060.49    .085       0
 1516.19     .05       0 1536.97    .085       0 2519.71     .04       0
#XS Ineff= 2 , 0
       0                    1786       0
Permanent Ineff=
       F       F
Bank Sta=1516.19,1536.97
XS Rating Curve= 0 ,0
Exp/Cntr=0.5,0.3

Type RM Length L Ch R = 1 ,12274   ,113.89,209.05,168.31
BEGIN DESCRIPTION:
Surveyed Section
END DESCRIPTION:
XS GIS Cut Line= 6
 2305447.1254326  725890.5226663 2304486.1743552  726090.2701075
 2304179.2776638  726018.0186443    2303887.5107     725846.0582
  2303497.262248  725492.9225753 2303000.9181389  724882.5747114
#Sta/Elev= 30
       0  127.52  220.99   124.6  472.23  118.64  532.81  114.73  691.97  110.71
  869.58  110.65  952.94  112.05  971.44  114.44 1001.21  114.99 1076.61  115.75
 1176.13  112.71 1226.27  112.02 1312.99  106.72 1392.64  104.631529.528  104.88
1532.111  102.781541.525  100.951546.387  101.061546.899  102.811550.256  105.03
 1655.73  102.68  1751.6  105.78 1848.79  104.16 2248.55  105.81 2366.58  110.47
 2394.86  113.76 2450.69  114.78 2493.28  118.74 2717.61  124.36 2962.55  126.28
#Mann= 6 ,-1 , 0
       0     .07       0 1001.21    .035       0 1176.13    .085       0
1532.111     .05       01546.899    .085       0 2493.28     .04       0
#XS Ineff= 2 , 0
       0    1506  113.68    1751       0  112.01
Permanent Ineff=
       F       F
Bank Sta=1532.111,1546.899
XS Rating Curve= 0 ,0
Exp/Cntr=0.5,0.3

Type RM Length L Ch R = 3 ,12150   ,,,
BEGIN DESCRIPTION:
Airport Blvd (SR 1158)
END DESCRIPTION:
Bridge Culvert--1,0,-1,-1, 0
Deck Dist Width WeirC Skew NumUp NumDn MinLoCord MaxHiCord MaxSubmerge Is_Ogee
124,66,2.6,0, 99, 52, , , 0.95, 0, 1,1,,
       0    6.45    6.45    9.05    9.05   27.66   31.47   33.59   49.17   62.14
   62.14   63.19   63.81   64.39   75.76    82.4   91.69   91.69  103.03  107.81
  114.87  119.04  119.04  121.91  131.69  131.69  137.49  144.52  147.05  147.05
  156.93  158.25  158.39   176.2  177.09  178.76  178.76  189.12  195.58  195.58
  200.94  209.82  213.41  215.59  215.59  229.89  243.09  243.09   247.4   247.4
  251.94  259.99  269.81  269.81  271.27  271.27  273.14  273.14  290.92   296.6
  301.07   316.1   316.1  330.39  667.93   669.5   669.5   671.8  691.59 1012.95
 1110.79 1111.421502.238 1526.69 1526.691575.3541632.1911703.029 1731.88 1731.88
1784.3391832.152  2287.1 2287.27 2287.27 2301.28 2301.28 2370.67 2381.85  2389.7
 2412.46 2412.46 2416.52 2420.93 2427.72 2427.72 2432.58 2432.58 2438.17
  124.33  124.25  124.25  124.28  124.28  124.04  124.09  123.88  123.53   124.1
   124.1  124.17  124.17  124.12  123.82  123.64  123.65  123.65  123.42  122.58
  123.29  123.52  123.52  123.21  122.48  122.48   122.1  122.66  122.61  122.61
  123.35  123.42  123.41  123.04  122.93   122.9   122.9  122.43  122.43  122.43
  121.55  122.33  122.39  122.16  122.16  122.03  121.89  121.89  121.86  121.86
   121.7  120.49  121.61  121.61  121.45  121.45  121.75  121.75  121.25  120.19
  120.69  120.35  120.35  121.05   118.9  118.75  118.75  118.71  118.85  116.37
  115.79  115.79  113.88  113.68  113.68  113.26  112.82  112.26  112.01  112.01
  111.65  111.21  111.51  111.51  111.51  111.51  111.51  112.77  113.03  113.19
     114     114  114.04  114.29  114.62  114.62  114.64  114.64  114.85
                                                                                
                                                                                
                                                                                
                                                                                
                                                                                
                                                                                
                                                                                
                                  110.28  109.86  109.42  108.86  108.61
                                                                                
                                                                        
       0    6.45    6.45    9.05    9.05   27.66   31.47   33.59   49.17   247.4
  609.29   789.3 1012.95 1110.79 1111.421502.238 1526.69 1526.691575.3541632.191
1703.029 1731.88 1731.881784.3391832.152  2287.1 2287.27 2287.27 2301.28 2301.28
 2314.76 2320.66  2335.5  2335.5 2345.11 2345.11 2359.04 2361.59 2364.24 2364.24
 2370.67 2381.85  2389.7 2412.46 2412.46 2416.52 2420.93 2427.72 2427.72 2432.58
 2432.58 2438.17
  124.33  124.25  124.25  124.28  124.28  124.04  124.09  123.88  123.53  121.86
  119.03  118.35  116.37  115.79  115.79  113.88  113.68  113.68  113.26  112.82
  112.26  112.01  112.01  111.65  111.21  111.51  111.51  111.51  111.51  111.51
  110.85  111.12  111.67  111.67  111.42  111.42  112.24  112.66  112.44  112.44
  112.77  113.03  113.19     114     114  114.04  114.29  114.62  114.62  114.64
  114.64  114.85
                                                                                
                                                          110.28  109.86  109.42
  108.86  108.61
                                                                                
                                                                                
                
Pier Skew, UpSta & Num, DnSta & Num=  ,1575.4, 2 ,1575.34, 2 , 2 , 2 , 0 ,,
       3     3.7
      99  106.66
       3     3.7
      99  106.66
Pier Skew, UpSta & Num, DnSta & Num=  ,1632.191, 2 ,1632.191, 2 , 2 , 2 , 0 ,,
       3     3.7
      99  106.22
       3     3.7
      99  106.22
Pier Skew, UpSta & Num, DnSta & Num=  ,1681.51, 2 ,1681.51, 2 , 0 , 0 , 0 ,,
     3.7     3.7
      99  110.28
     3.7     3.7
      99  110.28
Abutment Skew #Up #Dn= , 2 , 2
 1526.69 1529.53
  110.28  104.88
 1526.69 1540.72
  110.28  105.26
Abutment Skew #Up #Dn= , 2 , 2
 1721.41 1731.88
   105.1  108.61
  1719.2 1731.88
  104.24  108.61
BR Coef=-1 , 0 , 0 ,, 0 ,,,0.8,0,,0,
WSPro=,,,, 1 ,,,, 0 ,,,, 0 ,,,,-1 ,-1 ,-1 , 0 , 0 , 0 , 0 , 0
BC Design=,, 0 ,, 0 ,,,,,,
BC Use User HTab Curves=0
BC User HTab FreeFlow(D)= 0

Type RM Length L Ch R = 1 ,12065   ,497.88,479.83,449.95
BEGIN DESCRIPTION:
Surveyed Section
END DESCRIPTION:
XS GIS Cut Line= 6
 2305466.5126616  725780.4270785 2304462.0342034  726034.2324643
 2304398.6848092    726018.24193    2304133.5917     725733.2346
    2303533.1898   725354.963652 2303169.7149537  724758.2591126
#Sta/Elev= 30
       0  123.28  204.79  117.48  445.55  114.81  564.09  115.51  609.16  111.63
  663.51  108.99  787.29  106.01 1120.74  106.07 1428.71  106.821493.641     104
1560.541  105.171562.659  103.051567.606  101.471573.795     1011580.649  101.24
1581.953   102.81587.171  104.491645.337  105.65 1730.47  103.95 1954.92  103.87
 2064.82   104.6 2176.39  106.88 2280.11  111.88 2325.18  114.67 2338.86  116.38
 2476.19  117.74 2532.59  119.54 2617.86   120.3  2660.8  121.61 2912.76  124.52
#Mann= 7 ,-1 , 0
       0     .07       0 1120.74    .035       0 1428.71    .085       0
1562.659     .05       01581.953    .085       0 1730.47      .1       0
 1954.92    .045       0
#XS Ineff= 2 , 0
       0    1506  113.68    1751       0  112.01
Permanent Ineff=
       F       F
Bank Sta=1562.659,1581.953
XS Rating Curve= 0 ,0
Exp/Cntr=0.5,0.3

Type RM Length L Ch R = 1 ,11585   ,667.51,675.23,570.31
XS GIS Cut Line= 6
 2305410.7171635  725642.3352009 2304774.6333916  725621.1589963
 2304616.9880576  725548.9553061 2303902.2727089  725053.3235567
 2303693.9637128  724970.7182652 2303250.8760685  724499.8298894
#Sta/Elev= 30
       0  122.27  131.35  120.03  206.26  118.86   307.1  118.62  329.45  116.61
  346.43  116.15  479.42   112.9  645.96  110.54  739.44  105.68  783.69  103.67
  828.54   103.2 1023.56  103.16 1031.25  100.41 1046.63  100.41 1050.47  101.78
 1058.24  103.11 1090.55  102.48 1362.45   103.5 1433.51  102.79 1605.85  102.61
 1642.27  103.55  1804.3  105.14 1830.09  105.76  1895.8  109.79 1956.14  112.04
 1964.57  113.22 2089.18  116.42 2292.28   117.7 2377.61  120.22  2558.6  120.36
#Mann= 8 ,-1 , 0
       0     .06       0  131.35    .035       0  346.43     .06       0
  739.44    .085       0 1023.56     .05       0 1058.24    .085       0
 1362.45      .1       0  1804.3    .045       0
#Block Obstruct= 2 ,-1
       0    3.25     135  570.63  688.16     125
Bank Sta=1023.56,1058.24
XS Rating Curve= 0 ,0
Exp/Cntr=0.3,0.1

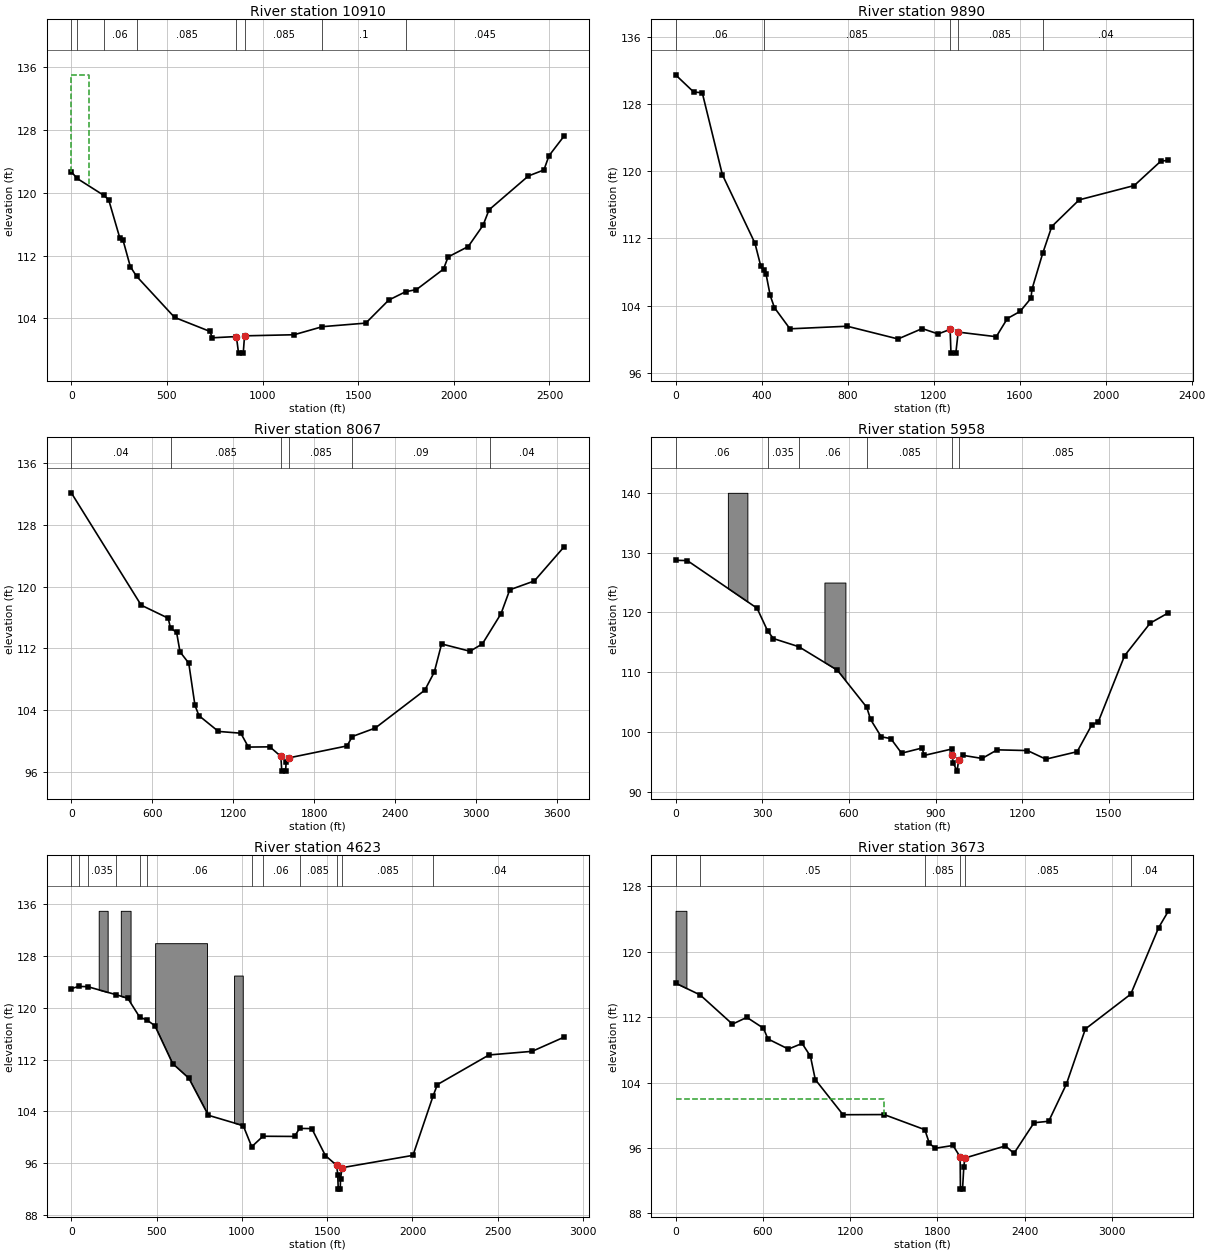
Type RM Length L Ch R = 1 ,10910   ,1008.24,1019.66,960.72
XS GIS Cut Line= 6
 2305563.3047232   725169.999117 2305227.2966981  725111.3930662
 2304277.8786738  724650.3587992 2304039.5474002  724497.9830669
 2303613.6767637  724193.2316023 2303324.5535794  723958.8073987
#Sta/Elev= 30
       0  122.68   29.36  121.83   170.4  119.65  195.43   119.1  253.46  114.25
  270.55  113.95  308.57  110.59  340.97  109.37   539.8  104.13  725.08  102.34
  736.78  101.53  863.15  101.69  874.34   99.58  898.95   99.58  905.66  101.78
  1164.8  101.92 1313.16  102.95 1539.51   103.4 1659.43  106.33 1747.33  107.39
 1804.67  107.67 1945.87  110.27 1969.84  111.82 2075.33  113.15 2152.64  115.85
    2184  117.82 2389.71  122.13 2470.73  122.89 2497.34   124.7 2575.33  127.18
#Mann= 8 ,-1 , 0
       0     .06       0   29.36    .035       0   170.4     .06       0
  340.97    .085       0  863.15     .05       0  905.66    .085       0
 1313.16      .1       0 1747.33    .045       0
#XS Ineff= 1 ,-1
       0      91     135
Permanent Ineff=
       F
Bank Sta=863.15,905.66
XS Rating Curve= 0 ,0
Exp/Cntr=0.3,0.1

Type RM Length L Ch R = 1 ,9890    ,1543.94,1823.32,1483.9
XS GIS Cut Line= 6
 2306176.7147225   724443.284086 2306036.0602004  724302.6295639
 2305106.1775263  724025.2275897 2304844.4038323  723876.7589275
 2304637.3291192  723747.8256155 2304270.0645336  723306.3266988
#Sta/Elev= 30
       0  131.53   84.09  129.48  124.06  129.39  217.61  119.61  369.04  111.44
  396.45  108.67  409.78  108.19   420.3   107.8     440   105.2  459.78  103.74
  531.82  101.22  797.82  101.53 1034.47  100.01 1146.77  101.25 1220.86  100.61
 1276.52  101.15 1280.57   98.32  1303.1   98.32 1314.08  100.83 1491.07  100.28
 1542.86  102.45 1602.13   103.3 1652.59  104.87 1657.14  105.94 1706.91  110.22
  1749.3  113.43 1876.63  116.61 2132.84  118.32 2255.88  121.22 2290.54  121.33
#Mann= 5 ,-1 , 0
       0     .06       0  409.78    .085       0 1276.52     .05       0
 1314.08    .085       0 1706.91     .04       0
#XS Ineff= 2 , 0
       0     802                       0
Permanent Ineff=
       F       F
Bank Sta=1276.52,1314.08
XS Rating Curve= 0 ,0
Exp/Cntr=0.3,0.1

Type RM Length L Ch R = 1 ,8067    ,2242.2,2108.81,1431.8
XS GIS Cut Line= 6
 2307159.1522181  723236.2987795 2306620.5952632  723214.0902453
 2305610.1069561  722564.4906193 2304444.1589093  722164.7370033
  2304111.030896  722087.0071335 2303789.0071497  722159.1848697
#Sta/Elev= 30
       0  132.18  517.61  117.61  717.69  115.92  735.42  114.61  780.11  114.09
  805.53  111.55  870.24  110.09  916.31   104.6   946.2  103.27 1090.12  101.23
 1255.92     101 1312.14    99.2  1471.4   99.23 1552.74   97.99 1559.59   96.08
 1587.57   96.08 1591.79   97.21 1612.24    97.8 2042.75   99.35 2082.16  100.57
 2252.06  101.67  2619.1  106.58  2689.3  108.92 2743.51  112.58 2954.02  111.63
 3045.54  112.58 3183.79   116.5 3248.57   119.6 3430.84  120.75 3649.71  125.15
#Mann= 6 ,-1 , 0
       0     .04       0  735.42    .085       0 1552.74     .05       0
 1612.24    .085       0 2082.16     .09       0  3098.6     .04       0
Bank Sta=1552.74,1612.24
XS Rating Curve= 0 ,0
Exp/Cntr=0.3,0.1

Type RM Length L Ch R = 1 ,5958    ,955.3,1334.66,1065.37
BEGIN DESCRIPTION:
Surveyed Section
END DESCRIPTION:
XS GIS Cut Line= 6
 2306231.9459143  720748.9429465 2305888.1737714  720799.1046495
 2305629.8303477  720796.5964609     2305250.246     721030.4792
 2305075.3980293  721071.1026345 2304617.2353161  720995.2285546
#Sta/Elev= 30
       0  128.72   40.65  128.67  282.02  120.71  318.86  116.89  338.78  115.63
  426.28  114.28  559.89  110.35  661.76  104.14  674.98  102.11  711.89   99.21
  744.95   98.91  782.35   96.47  852.73   97.33 861.037    96.1 955.504   97.16
  957.71   96.19 960.519   94.89 974.505   93.47 979.913   95.36 994.815   96.11
1061.031   95.59 1113.25   97.03  1218.1   96.91 1281.67   95.47 1390.07   96.72
 1440.32  101.17 1463.31  101.73 1554.13  112.76 1642.71  118.21 1705.14  119.92
#Mann= 6 ,-1 , 0
       0     .06       0  318.86    .035       0  426.28     .06       0
  661.76    .085       0  957.71     .05       0 979.913    .085       0
#Block Obstruct= 2 ,-1
  181.02   248.5     140  515.26  587.86     125
Bank Sta=957.71,979.913
XS Rating Curve= 0 ,0
Exp/Cntr=0.3,0.1

Type RM Length L Ch R = 1 ,4623    ,667.68,950.27,750.47
XS GIS Cut Line= 6
 2306622.9026713  720262.2541104  2306489.651466  720156.7635728
 2306128.7627849  719984.6474326 2305778.9783709   719929.126097
 2304263.2459101  720090.1379701 2303824.6273592  720112.3465044
#Sta/Elev= 30
       0  122.98   43.29  123.32   96.38  123.28  260.31  122.06  330.79   121.5
  400.28   118.6  444.46   118.1  489.84  117.26  593.86  111.41  689.09  109.14
  803.46  103.41 1007.97  101.81 1057.79   98.55  1123.7  100.17 1308.88  100.14
 1338.02  101.38 1410.17  101.35 1489.47   97.19 1556.11   95.66 1562.03   94.23
 1564.99      92 1576.84      92 1578.32   93.55 1587.21   95.31 2003.08   97.22
 2120.67  106.36 2146.07  108.15 2448.83  112.73 2701.62  113.29 2888.01  115.47
#Mann= 12 ,-1 , 0
       0    .035       0   43.29     .06       0   96.38    .035       0
  260.31     .06       0  400.28    .035       0  444.46     .06       0
 1057.79    .035       0  1123.7     .06       0 1338.02    .085       0
 1556.11     .05       0 1587.21    .085       0 2120.67     .04       0
#XS Ineff= 2 , 0
       0 1338.02  101.38               0
Permanent Ineff=
       F       F
#Block Obstruct= 4 ,-1
  160.77   213.1     135  290.27  347.49     135  491.44  795.64     130
  954.29 1005.18     125
Bank Sta=1556.11,1587.21
XS Rating Curve= 0 ,0
Exp/Cntr=0.3,0.1

Type RM Length L Ch R = 1 ,3673    ,250.18,286.03,317.66
XS GIS Cut Line= 6
 2306861.0168096  719149.7628823 2306190.9143851   719178.364815
 2305304.2544697  719345.8904212 2304834.5868405  719305.8209956
   2303990.66254  719044.8707184 2303546.4918555  719128.1527218
#Sta/Elev= 30
       0  116.16  169.25  114.71  391.09  111.14  490.08  111.97  604.52  110.64
  635.06  109.33   775.9  108.09   870.2  108.78  927.56  107.21  960.86  104.36
 1151.67  100.06  1434.3  100.08 1714.37   98.23 1745.37   96.55 1786.63   95.96
 1908.11    96.3 1957.19    94.9 1959.09   90.96 1973.51   90.96 1982.28   93.67
 1989.53   94.76 2268.67   96.25 2327.12   95.33 2465.38   99.08 2566.17   99.26
 2688.13  103.82 2818.39  110.55 3130.58  114.81 3322.46  122.95  3387.9  124.93
#Mann= 6 ,-1 , 0
       0     .04       0  169.25     .05       0 1714.37    .085       0
 1957.19     .05       0 1989.53    .085       0 3130.58     .04       0
#XS Ineff= 2 , 0
       0    1435     102               0
Permanent Ineff=
       F       F
#Block Obstruct= 1 ,-1
       0    74.5     125
Bank Sta=1957.19,1989.53
XS Rating Curve= 0 ,0
Exp/Cntr=0.5,0.3

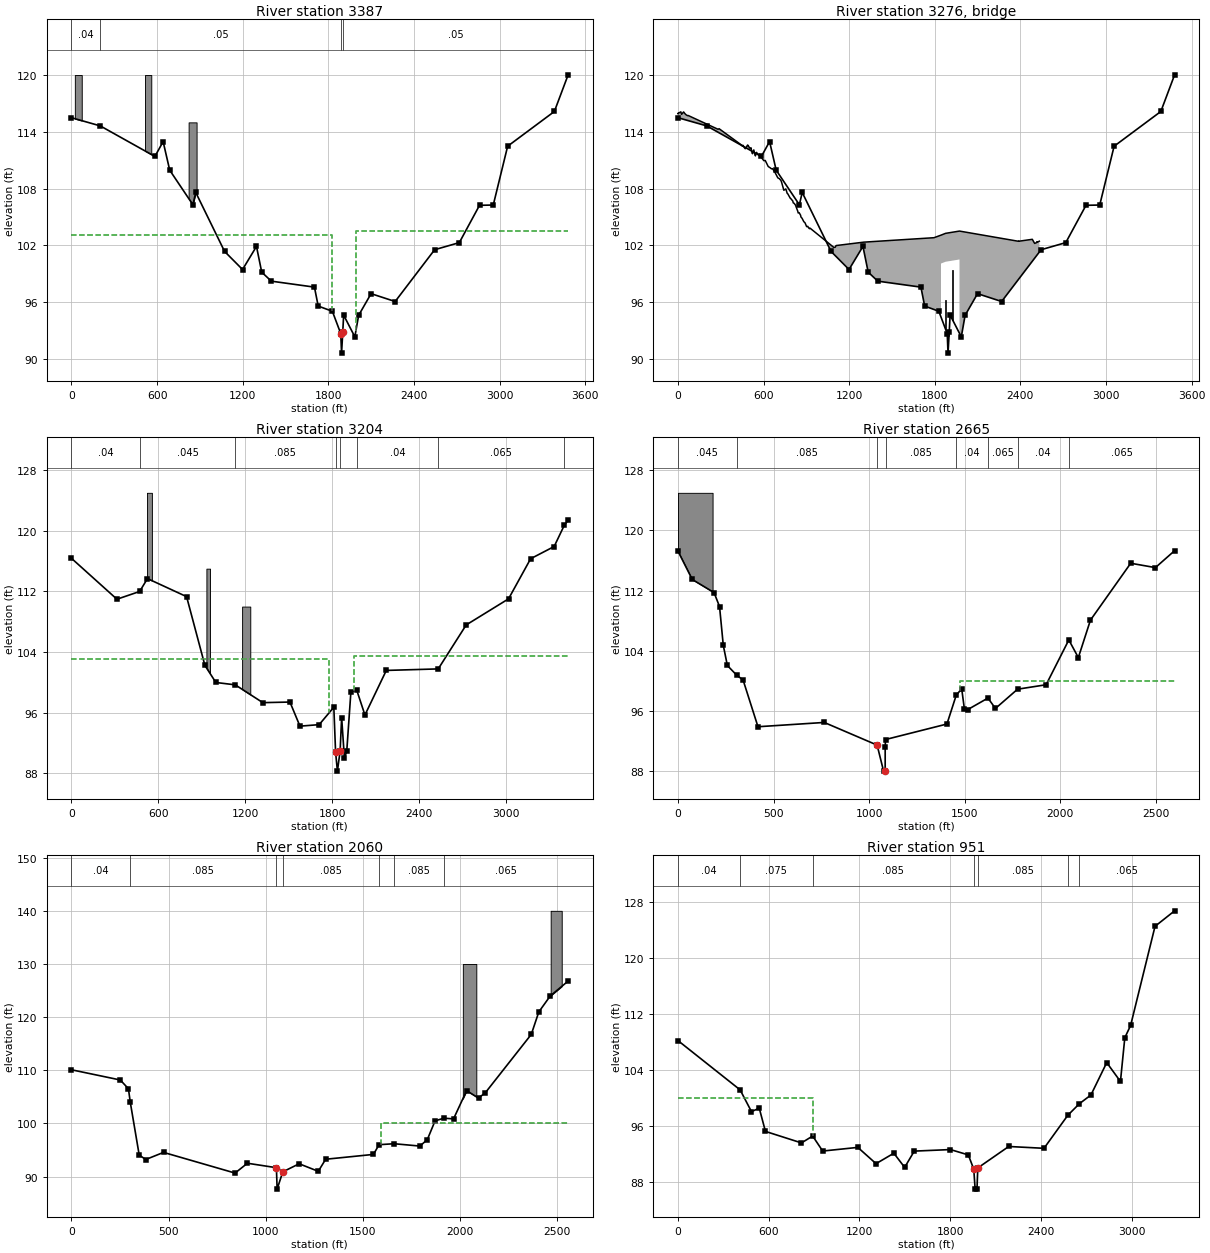
Type RM Length L Ch R = 1 ,3387    ,165.81,183.49,167.54
BEGIN DESCRIPTION:
Surveyed Section
END DESCRIPTION:
XS GIS Cut Line= 6
 2306880.4925773  719050.7562385  2305487.820757  719155.7315013
    2305061.1487     719070.5925 2304260.9280826  718776.2167382
 2303830.7170192  718716.6490525 2303475.5171156  718738.7111583
#Sta/Elev= 30
       0  115.49  201.18  114.63  584.55   111.4  642.16  112.97  688.32  109.95
  850.85   106.3  870.74   107.6 1072.83  101.37 1198.75   99.46 1296.42   101.9
 1333.12   99.18 1400.51   98.23 1702.63    97.6 1728.94    95.6 1828.16   95.05
 1887.08   92.691892.652   90.63 1901.33   92.911907.227   94.651985.706   92.35
2012.332   94.62 2099.54   96.91 2268.24   96.08  2544.9  101.55 2717.96   102.3
 2859.54  106.24 2955.85  106.27 3056.62  112.48 3384.14  116.15  3480.6  120.02
#Mann= 4 ,-1 , 0
       0     .04       0  201.18     .05       0 1887.08     .05       0
 1901.33     .05       0
#XS Ineff= 2 , 0
       0    1823  103.09    1993       0  103.52
Permanent Ineff=
       F       F
#Block Obstruct= 3 ,-1
   23.42   71.81     120  515.04  559.12     120  820.78  876.65     115
Bank Sta=1887.08,1901.33
XS Rating Curve= 0 ,0
Exp/Cntr=0.5,0.3

Type RM Length L Ch R = 3 ,3276    ,,,
BEGIN DESCRIPTION:
HWY 42
END DESCRIPTION:
Bridge Culvert--1,0,-1,-1, 0
Deck Dist Width WeirC Skew NumUp NumDn MinLoCord MaxHiCord MaxSubmerge Is_Ogee
64,60,2.6,0, 145, 145, , , 0.95, 0, 1,1,,
       0     .65    1.24    3.29   20.21   25.29   25.29   39.45   39.45   40.08
   40.08   49.34   49.34   58.65   58.65   67.73   67.73   73.11   78.09  280.99
  288.32  448.51  451.78  451.78   455.7  464.57  471.26   472.4  473.59   488.2
   488.2  492.01  492.01  496.38  496.38  505.47  511.71  519.73  522.84  531.39
  539.58  539.58   542.9   542.9  545.26  550.93  554.73  565.24  570.89  570.89
  572.82  572.82  590.98  602.22  602.22  611.52  611.52  632.14  632.14  632.22
  632.22   632.4  647.47  647.47  655.26  662.48  676.28  677.26  677.26   677.6
  693.63  699.77  709.99  721.89  726.36  739.11  742.04  743.69  756.02  765.57
  769.87  777.43  784.15  786.18  786.18  787.13  789.33  789.33  804.92  807.78
  814.36  823.78  823.78  828.67  839.54  839.54  842.62  849.31  859.46  861.77
  864.73  864.73  869.77  874.71  874.71  881.62  881.62  890.21  890.31  890.53
  890.53  901.68  901.68  907.93  907.93  909.74  914.08  914.08  921.48  921.48
  925.53 1091.83 1101.76 1101.76 1108.14 1301.591794.327 1843.42 1843.42 1875.35
1924.6791973.0251973.025 2387.24 2388.18 2388.18 2389.71 2483.18  2485.3 2499.41
 2512.14 2512.14 2515.31 2518.99 2532.67
  115.94  115.95  115.91  115.97  116.11  115.85  115.85   116.1   116.1  116.09
  116.09  115.91  115.91  115.78  115.78  115.71  115.71  115.72  115.68  114.27
  114.33  112.57  112.48  112.48  112.58  112.35  112.22  112.23  112.26  112.61
  112.61  112.55  112.55  112.43  112.43  112.25  112.32  111.75  111.69  112.09
  111.59  111.59  111.46  111.46  111.61  111.83  111.71  111.56  111.64  111.64
   111.6   111.6  111.16  110.95  110.95  110.98  110.98  110.34  110.34  110.34
  110.34  110.34  110.19  110.19  110.09  110.11  109.82  109.79  109.79  109.79
  109.31  109.14  109.06  108.86  108.67  107.97  107.83  107.85  107.97   107.5
  107.45  107.25  107.06     107     107  106.98  106.97  106.97  106.69   106.5
  106.45  106.26  106.26  106.05  105.62  105.62  105.43  105.46  105.19  105.01
  104.96  104.96  104.87  104.73  104.73  104.52  104.52   104.4   104.4  104.39
  104.39  103.99  103.99  104.02  104.02  104.02  103.89  103.89  103.77  103.77
  103.83   101.8  101.81  101.81  101.99  102.35  102.82  103.09  103.09  103.28
   103.4  103.52  103.52  102.44  102.48  102.48  102.45  102.65   102.6  102.22
  102.29  102.29   102.4  102.35  102.45
                                                                                
                                                                                
                                                                                
                                                                                
                                                                                
                                                                                
                                                                                
                                                                                
                                                                                
                                                                                
                                                                                
                                                                                
                                                                  100.09  100.28
   100.4  100.52
                                        
     -44  -43.35  -42.76  -40.71  -23.79  -18.71  -18.71   -4.55   -4.55   -3.92
   -3.92    5.34    5.34   14.65   14.65   23.73   23.73   29.11   34.09  236.99
  244.32  404.51  407.78  407.78   411.7  420.57  427.26   428.4  429.59   444.2
   444.2  448.01  448.01  452.38  452.38  461.47  467.71  475.73  478.84  487.39
  495.58  495.58   498.9   498.9  501.26  506.93  510.73  521.24  526.89  526.89
  528.82  528.82  546.98  558.22  558.22  567.52  567.52  588.14  588.14  588.22
  588.22   588.4  603.47  603.47  611.26  618.48  632.28  633.26  633.26   633.6
  649.63  655.77  665.99  677.89  682.36  695.11  698.04  699.69  712.02  721.57
  725.87  733.43  740.15  742.18  742.18  743.13  745.33  745.33  760.92  763.78
  770.36  779.78  779.78  784.67  795.54  795.54  798.62  805.31  815.46  817.77
  820.73  820.73  825.77  830.71  830.71  837.62  837.62  846.21  846.31  846.53
  846.53  857.68  857.68  863.93  863.93  865.74  870.08  870.08  877.48  877.48
  881.53 1047.83 1057.76 1057.76 1064.14 1257.591750.327 1799.42 1799.42 1831.35
1880.6791929.0251929.025 2343.24 2344.18 2344.18 2345.71 2439.18  2441.3 2455.41
 2468.14 2468.14 2471.31 2474.99 2488.67
  115.94  115.95  115.91  115.97  116.11  115.85  115.85   116.1   116.1  116.09
  116.09  115.91  115.91  115.78  115.78  115.71  115.71  115.72  115.68  114.27
  114.33  112.57  112.48  112.48  112.58  112.35  112.22  112.23  112.26  112.61
  112.61  112.55  112.55  112.43  112.43  112.25  112.32  111.75  111.69  112.09
  111.59  111.59  111.46  111.46  111.61  111.83  111.71  111.56  111.64  111.64
   111.6   111.6  111.16  110.95  110.95  110.98  110.98  110.34  110.34  110.34
  110.34  110.34  110.19  110.19  110.09  110.11  109.82  109.79  109.79  109.79
  109.31  109.14  109.06  108.86  108.67  107.97  107.83  107.85  107.97   107.5
  107.45  107.25  107.06     107     107  106.98  106.97  106.97  106.69   106.5
  106.45  106.26  106.26  106.05  105.62  105.62  105.43  105.46  105.19  105.01
  104.96  104.96  104.87  104.73  104.73  104.52  104.52   104.4   104.4  104.39
  104.39  103.99  103.99  104.02  104.02  104.02  103.89  103.89  103.77  103.77
  103.83   101.8  101.81  101.81  101.99  102.35  102.82  103.09  103.09  103.28
   103.4  103.52  103.52  102.44  102.48  102.48  102.45  102.65   102.6  102.22
  102.29  102.29   102.4  102.35  102.45
                                                                                
                                                                                
                                                                                
                                                                                
                                                                                
                                                                                
                                                                                
                                                                                
                                                                                
                                                                                
                                                                                
                                                                                
                                                                  100.09  100.28
   100.4  100.52
                                        
Pier Skew, UpSta & Num, DnSta & Num=  ,1875.35, 2 ,1831.35, 2 , 2 , 2 , 0 ,,
     3.7       4
      80   96.28
     3.7       4
      80   96.28
Pier Skew, UpSta & Num, DnSta & Num=  ,1924.679, 2 ,1880.679, 2 , 2 , 2 , 0 ,,
     3.7       4
      80    99.4
     3.7       4
      80    99.4
Abutment Skew #Up #Dn= , 2 , 2
 1843.42 1854.97
      99   94.45
 1799.42 1807.35
      99   96.68
Abutment Skew #Up #Dn= , 2 , 2
  1954.9 1973.03
   93.97      99
 1923.63 1929.03
   97.49     100
BR Coef=-1 , 0 , 0 ,, 0 ,,,0.8,0,,0,
WSPro=,,,, 1 ,,,, 0 ,,,, 0 ,,,,-1 ,-1 ,-1 , 0 , 0 , 0 , 0 , 0
BC Design=,, 0 ,, 0 ,,,,,,
BC Use User HTab Curves=0
BC User HTab FreeFlow(D)= 0

Type RM Length L Ch R = 1 ,3204    ,461.27,538.84,575.81
BEGIN DESCRIPTION:
Surveyed Section
END DESCRIPTION:
XS GIS Cut Line= 6
 2306822.1729868  718894.4597361 2305791.0826274   719011.098917
 2305450.4962191  718999.4349989 2304370.4174037  718677.5108595
 2303994.8392411  718628.5224035 2303458.2990088   718637.853538
#Sta/Elev= 30
       0  116.36  313.57  110.97  470.26  111.99  524.35  113.69   794.3  111.31
  920.69  102.24  996.33   99.99 1130.06   99.68  1320.6   97.33  1507.6   97.41
 1576.71   94.23 1709.31   94.431810.428   96.731822.601   90.811835.189    88.3
1853.837   90.961864.433   95.361883.571   89.991899.663   90.921928.331   98.78
 1968.09  99.009 2025.16    95.7 2172.55  101.58 2530.89  101.78 2724.08  107.58
 3016.21  111.02 3168.72  116.31 3331.06  117.92 3400.46   120.7 3427.54   121.4
#Mann= 8 ,-1 , 0
       0     .04       0  470.26    .045       0 1130.06    .085       0
1822.601     .05       01853.837    .085       0 1968.09     .04       0
 2530.89    .065       0 3400.46     .03       0
#XS Ineff= 2 , 0
       0    1779  103.09    1949       0  103.52
Permanent Ineff=
       F       F
#Block Obstruct= 3 ,-1
  521.18  554.89     125  931.05  956.14     115 1177.44 1233.84     110
Bank Sta=1822.601,1853.837
XS Rating Curve= 0 ,0
Exp/Cntr=0.5,0.3

Type RM Length L Ch R = 1 ,2665    ,579.02,604.98,367.96
XS GIS Cut Line= 6
 2305990.7008558  718536.8643232 2305366.7400745  718517.3379979
 2304690.8419972  718268.6152825 2304313.1056566  718250.8394546
 2303962.0330575  718206.3998851 2303442.0900944  718237.5075838
#Sta/Elev= 30
       0  117.25   74.52  113.49  188.78  111.74  217.49  109.88  237.02  104.74
  258.35  102.05   308.1  100.74  340.55  100.13  418.51   93.91  765.16   94.48
 1041.72   91.47 1075.53   88.01  1083.9   88.05  1083.9   91.18 1085.63   92.21
 1406.87   94.27 1455.29   98.08 1484.05   98.97 1498.31   96.26 1515.05   96.18
 1621.55   97.72 1660.67   96.34 1776.38    98.9 1925.68   99.49 2044.48  105.45
 2094.25   103.1 2157.59  108.08 2368.25  115.64 2497.37  115.06 2597.81  117.31
#Mann= 8 ,-1 , 0
       0    .045       0   308.1    .085       0 1041.72     .05       0
 1085.63    .085       0 1455.29     .04       0 1621.55    .065       0
 1776.38     .04       0 2044.48    .065       0
#XS Ineff= 2 , 0
       0                  1474.3       0     100
Permanent Ineff=
       F       F
#Block Obstruct= 1 ,-1
       0  181.04     125
Bank Sta=1041.72,1083.9
XS Rating Curve= 0 ,0
Exp/Cntr=0.3,0.1

Type RM Length L Ch R = 1 ,2060    ,646.41,1108.69,665.27
XS GIS Cut Line= 6
 2305913.0670383  718197.7271205 2305647.4776627  717985.2556201
 2305141.4636873  717880.7542955 2304717.2447726  717965.5980784
 2303812.2444212  717890.1813825 2303477.5828329  717795.9105125
#Sta/Elev= 30
       0   110.1  251.13  108.18  293.04  106.53  302.66  103.97  348.44   94.07
  382.09   93.22   473.7   94.56  841.94   90.67  905.41   92.52 1054.72   91.68
 1058.36   87.65 1087.52    90.9 1171.88   92.42 1270.16      91 1308.22   93.27
 1554.13   94.18  1583.1   96.01 1660.81   96.19 1793.04   95.75 1831.28   96.95
 1871.35  100.49 1916.18  100.99 1966.49  100.87 2033.79  106.18 2094.91  104.77
 2130.91  105.82 2366.59  116.76 2405.26  120.98 2463.84  123.97 2556.27  126.79
#Mann= 7 ,-1 , 0
       0     .04       0  302.66    .085       0 1054.72     .05       0
 1087.52    .085       0  1583.1     .04       0 1660.81    .085       0
 1916.18    .065       0
#XS Ineff= 2 , 0
       0                 1591.68       0     100
Permanent Ineff=
       F       F
#Block Obstruct= 2 ,-1
  2014.3 2083.62     130 2466.41 2523.26     140
Bank Sta=1054.72,1087.52
XS Rating Curve= 0 ,0
Exp/Cntr=0.3,0.1

Type RM Length L Ch R = 1 ,951     ,684.63,951.11,849.37
XS GIS Cut Line= 6
 2306612.0892583  717795.9105125 2306329.2766485  717536.6656202
  2305584.536776  717272.7071844 2304401.4373583  717286.8478149
 2303934.7965521  717244.4259234 2303482.2963764  717310.4155323
#Sta/Elev= 30
       0  108.22  411.22  101.19   486.1   98.09  537.63   98.58  578.49   95.27
  816.69   93.63  890.88   94.61  957.14   92.47  1189.5   92.99 1310.06   90.67
 1427.77   92.16 1499.17   90.14 1562.85   92.46 1801.88   92.68 1920.23   91.92
 1956.41   89.87 1965.23   87.04 1977.58   87.04 1982.88   90.06 2187.56   93.12
 2420.75   92.86 2578.67   97.58 2654.87   99.22 2731.07  100.46 2835.63  105.08
 2926.32  102.39 2955.16  108.62 2993.54  110.38 3155.06  124.51 3284.51  126.72
#Mann= 7 ,-1 , 0
       0     .04       0  411.22    .075       0  890.88    .085       0
 1956.41     .05       0 1982.88    .085       0 2578.67     .04       0
 2654.87    .065       0
#XS Ineff= 2 , 0
       0  890.88     100               0
Permanent Ineff=
       F       F
Bank Sta=1956.41,1982.88
XS Rating Curve= 0 ,0
Exp/Cntr=0.3,0.1

Chan Stop Cuts=-1
Use User Specified Reach Order=0
User Specified Reach Order=Bloomery Swamp  ,Bloomery Swamp