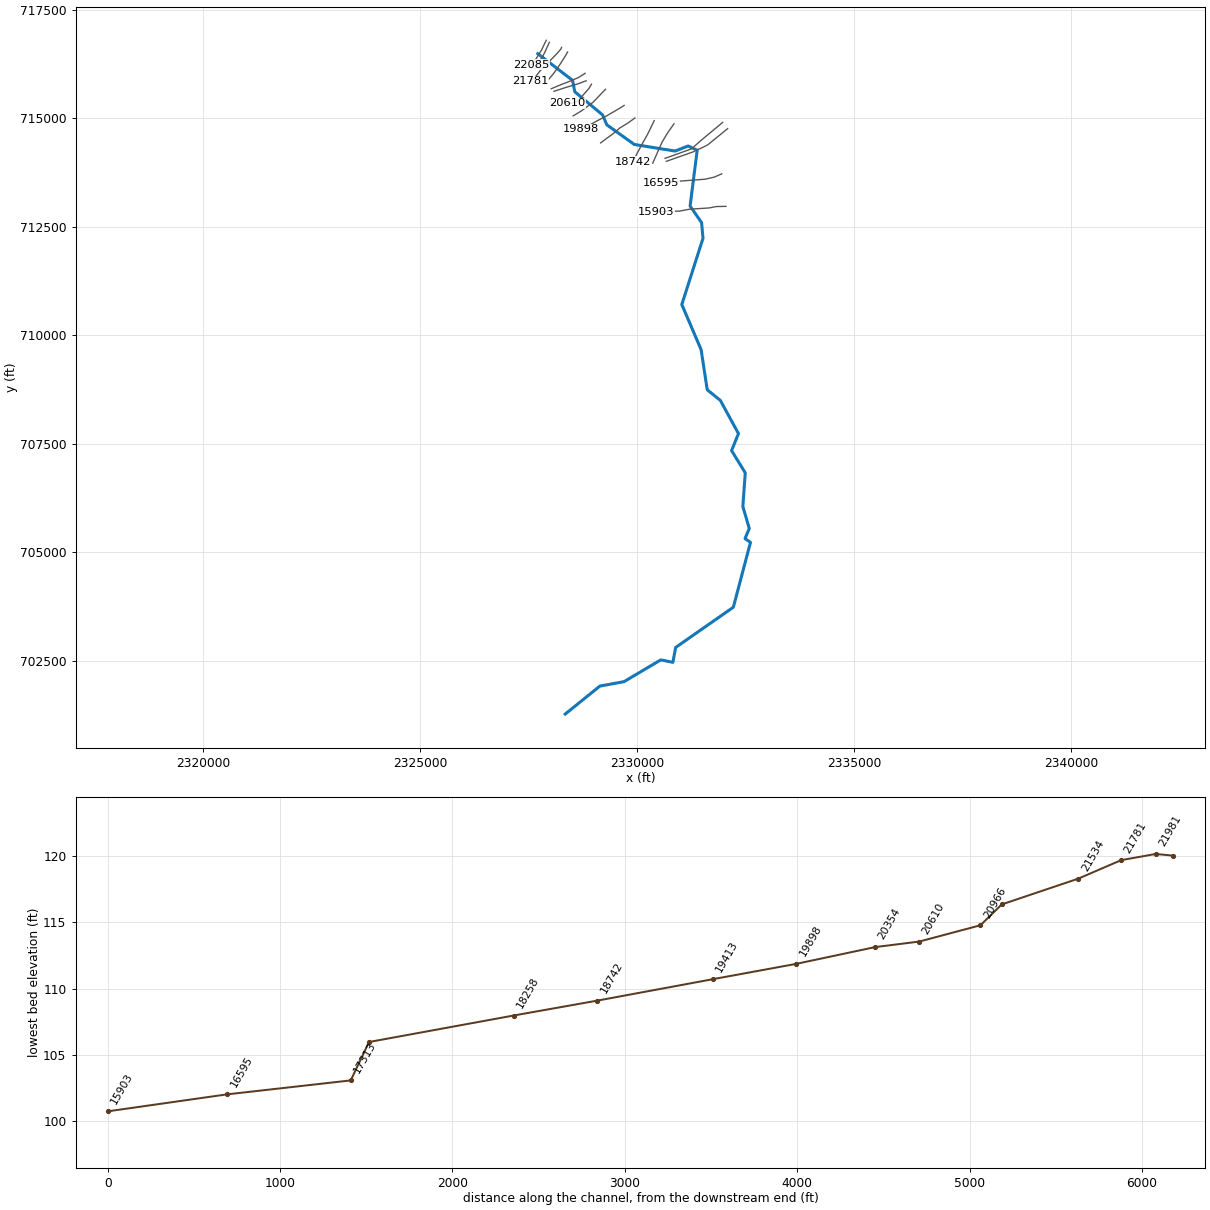
--- dtl_Hominy_Swamp_Trib1.prj (project) ---

Proj Title=DTL_Hominy_Swamp_Trib1
Current Plan=p01
Default Exp/Contr=0.3,0.1
English Units
Geom File=g01
Flow File=f01
Flow File=f02
Plan File=p01
Plan File=p02
Y Axis Title=Elevation
X Axis Title(PF)=Main Channel Distance
X Axis Title(XS)=Station
BEGIN DESCRIPTION:
END DESCRIPTION:
DSS Export Rating Curves= 0
DSS Export Rating Curve Sorted= 0
DSS Export Volume Flow Curves= 0
DXF Filename=\scott\dtl_Hominy_Swamp_Trib1.
DXF OffsetX= 0
DXF OffsetY= 0
DXF ScaleX= 1
DXF ScaleY= 10

--- dtl_Hominy_Swamp_Trib1.p01 (plan) ---

Plan Title=DTL_Hominy_Swamp_Trib1
Program Version=4.00
Short Identifier=DTL_Hominy_S
Geom File=g01
Flow File=f01
Subcritical Flow
K Sum by GR= 0
Std Step Tol= 0.01
Critical Tol= 0.01
Num of Std Step Trials= 20
Max Error Tol= 0.3
Flow Tol Ratio= 0.001
Split Flow NTrial= 30
Split Flow Tol= 0.02
Split Flow Ratio= 0.02
Log Output Level= 0
Friction Slope Method= 1
Unsteady Friction Slope Method= 2
Unsteady Bridges Friction Slope Method= 1
Parabolic Critical Depth
Global Vel Dist= 0 , 0 , 0
Global Log Level= 0
CheckData=True
Encroach Param=-1 ,10,10, 2
Encroach River=Hominy Swamp
Encroach Reach=Trib 1
Encroach Node=22085
       1     356     430
Encroach Node=21981
       1   381.4   415.6
Encroach Node=21781
       1     421     470
Encroach Node=21534
       1     421     455
Encroach Node=21089
       1  313.52     348
Encroach Node=20966
       1     298     329
Encroach Node=20610
       1     355     387
Encroach Node=20354
       1     520     548
Encroach Node=19898
       1     501     557
Encroach Node=19413
       1     447     500
Encroach Node=18742
       1     667     715
Encroach Node=18258
       1  626.72     695
Encroach Node=17419
       1     820     885
Encroach Node=17313
       1     843  887.64
Encroach Node=16595
       1     645     715
Encroach Node=15903
       1     740     850
Encroach Node=15471
       1     545     645
Encroach Node=14807
       1     600     675
Encroach Node=14268
       1   475.5  545.54
Encroach Node=14123
       1     598     650
Encroach Node=13497
       1  623.83  714.96
Encroach Node=12816
       1     420     520
Encroach Node=12240
       1     780     890
Encroach Node=11901
       1  852.99  945.11
Encroach Node=11820
       1  826.01  918.14
Encroach Node=11370
       1     700  808.87
Encroach Node=10822
       1  721.27  840.76
Encroach Node=10350
       1     405  613.95
Encroach Node=9596
       1  722.81  927.47
Encroach Node=8809
       1  517.31  755.84
Encroach Node=8117
       1  705.82  921.77
Encroach Node=7834
       1  415.48   661.3
Encroach Node=7478
       1  298.38  573.72
Encroach Node=7392
       1  317.68  593.02
Encroach Node=6972
       1     770 1028.42
Encroach Node=6636
       1     450     650
Encroach Node=6416
       1     775     900
Encroach Node=6338
       1     800     900
Encroach Node=6048
       1     660     740
Encroach Node=5754
       1     755     830
Encroach Node=5676
       1     820     880
Encroach Node=5395
       1     615     665
Encroach Node=5182
       1  527.33  567.92
Encroach Node=4983
       1  576.11  628.35
Encroach Node=4579
       1     495  580.45
Encroach Node=4173
       1     640     715
Encroach Node=4076
       1     632     677
Encroach Node=3845
       1     411     530
Encroach Node=2902
       1    1055    1190
Encroach Node=2296
       1    1430    1625
Encroach Node=1377
       1  924.06 1243.26
Computation Interval=1HOUR
Output Interval=1HOUR
Run HTab= 0
Run UNet= 0
Run PostProcess= 0
Run WQNet= 0
UNET Theta= 1
UNET Theta Warmup= 1
UNET ZTol= 0.02
UNET ZSATol= 0.05
UNET MxIter= 20
UNET MaxInSteps= 0
UNET DtIC= 0
UNET DtMin= 0
UNET MaxCRTS= 20
UNET WFStab= 2
UNET SFStab= 1
UNET WFX= 1
UNET SFX= 1
UNET DSS MLevel= 4
UNET DZMax Abort= 100
UNET Convert EG Bridges= 0
UNET Use Existing IB Tables=-1
UNET Froude Reduction=False
UNET Froude Limit= 1
UNET Froude Power= 10
UNET Time Slicing=0,0, 5
Instantaneous Interval=1HOUR
DSS File=dss
Write IC File= 0
Echo Input=False
Echo Output=False
Write Detailed= 0
Detailed Automatic Start=False, 10
WQ ULTIMATE=-1
WQ Max Comp Step=1HOUR
WQ Output Interval=15MIN
WQ Output Selected Increments= 0
WQ Output face flow=0
WQ Output face velocity=0
WQ Output face area=0
WQ Output face dispersion=0
WQ Output cell volume=0
WQ Output cell surface area=0
WQ Output cell continuity=0
WQ Output face conc=0
WQ Output face dconc_dx=0
WQ Output face courant=0
WQ Output face peclet=0
WQ Output face adv mass=0
WQ Output face disp mass=0
WQ Output cell mass=0
WQ Output cell source sink temp=0
WQ Output cell source sink nsm=0
WQ Output MaxMinRange=-1
WQ Daily Max Min Mean=-1
WQ Daily Range=0
WQ Daily Time=0
WQ Create Restart=0
WQ Fixed Restart=0
WQ System Summary=False
Sorting and Armoring Iterations= 10
XS Update Threshold= 0.02
Hydraulics Update Threshold= 0.02
Energy Slope Method= 1
Volume Change Method= 0
XS Weighting Method= 0
Number of US Weighted Cross Sections= 1
Number of DS Weighted Cross Sections= 1
Upstream XS Weight=0.25
Main XS Weight=0.5
Downstream XS Weight=0.25
Number of DS XS's Weighted with US Boundary= 1
Upstream Boundary Weight= 1
Weight of XSs Associated with US Boundary= 0
Number of US XS's Weighted with DS Boundary= 1
Downstream Boundary Weight= 0.5
Weight of XSs Associated with DS Boundary= 0.5
Sediment Output Level= 4
Mass or Volume Output= 0
Output Increment Type= 1
Profile and TS Output Increment= 10
XS Output Flag= 0
XS Output Increment= 10
Disregard all LS=0
Disregard all Conn=0
Disregard all Breaches=0
Disregard all Pumps=0

--- dtl_Hominy_Swamp_Trib1.p02 (plan) ---

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Plan Title=DTL_Hominy_Swamp_Trib1_Future
Short Identifier=Future
Geom File=g01
Flow File=f02
Encroach Param=-1 ,0,0, 0

--- dtl_Hominy_Swamp_Trib1.f01 (steady flow) ---

Flow Title=DTL_Hominy_Swamp_Trib1
Program Version=4.00
Number of Profiles= 6
Profile Names=100-yr,FW,10-yr,25-yr,50-yr,500-yr
River Rch & RM=Hominy Swamp,Trib 1          ,22085
     960     960     440     680     820    1370
River Rch & RM=Hominy Swamp,Trib 1          ,14807
    1250    1250     580     880    1060    1810
River Rch & RM=Hominy Swamp,Trib 1          ,8117
    1270    1270     570     880    1070    1880
River Rch & RM=Hominy Swamp,Trib 1          ,2902
    1350    1350     590     920    1130    2030
Boundary for River Rch & Prof#=Hominy Swamp,Trib 1          , 1
Up Type= 0
Dn Type= 3
Dn Slope=0.001306
Boundary for River Rch & Prof#=Hominy Swamp,Trib 1          , 2
Up Type= 0
Dn Type= 3
Dn Slope=0.001306
Boundary for River Rch & Prof#=Hominy Swamp,Trib 1          , 3
Up Type= 0
Dn Type= 3
Dn Slope=0.001306
Boundary for River Rch & Prof#=Hominy Swamp,Trib 1          , 4
Up Type= 0
Dn Type= 3
Dn Slope=0.001306
Boundary for River Rch & Prof#=Hominy Swamp,Trib 1          , 5
Up Type= 0
Dn Type= 3
Dn Slope=0.001306
Boundary for River Rch & Prof#=Hominy Swamp,Trib 1          , 6
Up Type= 0
Dn Type= 3
Dn Slope=0.001306
DSS Import GetInterval= 0
DSS Import GetPeak= 0
DSS Import FillOption= 0

--- dtl_Hominy_Swamp_Trib1.f02 (steady flow) ---

Flow Title=DTL_Hominy_Swamp_Trib1_Future
Program Version=4.00
Number of Profiles= 3
Profile Names=100-yr-10%,100-yr-20%,100-yr-35%
River Rch & RM=Hominy Swamp,Trib 1          ,22085
     830    1060    1300
River Rch & RM=Hominy Swamp,Trib 1          ,14807
    1210    1550    1890
River Rch & RM=Hominy Swamp,Trib 1          ,8117
    1380    1770    2160
River Rch & RM=Hominy Swamp,Trib 1          ,2902
    1620    2080    2540
Boundary for River Rch & Prof#=Hominy Swamp,Trib 1          , 1
Up Type= 0
Dn Type= 3
Dn Slope=0.001306
Boundary for River Rch & Prof#=Hominy Swamp,Trib 1          , 2
Up Type= 0
Dn Type= 3
Dn Slope=0.001306
Boundary for River Rch & Prof#=Hominy Swamp,Trib 1          , 3
Up Type= 0
Dn Type= 3
Dn Slope=0.001306
DSS Import GetInterval= 0
DSS Import GetPeak= 0
DSS Import FillOption= 0

--- dtl_Hominy_Swamp_Trib1.g01 (geometry) ---

Geom Title=DTL_Hominy_Swamp_Trib1
Program Version=4.00

River Reach=Hominy Swamp    ,Trib 1
Reach XY= 30
2327715.23146352716484.2200616152328515.13758396715870.964703098
2328567.38728561715606.9280606362329208.01228562715073.941949502
2329304.36645226714847.3794495172329939.78311893714393.386393949
2330879.01923004714242.3447272782331180.23450786714359.532227293
2331387.69978562714260.5738939492331224.50534119 712975.85167174
2331488.39423004712595.6433383972331522.24839669 712235.40028283
2331033.53311893710707.6225050542331477.97756337709669.428060636
2331619.47061895708744.0808383972331920.68589671 708501.02528283
2332339.08867446 707735.400282832332180.23450784707343.907227278
2332495.33867449706832.6225050692332439.78311892 706055.71278283
2332588.22061892705551.3725050542332490.13034116705316.129449502
2332615.99839674705231.0600050692332221.03311892703737.136393964
 2330892.0400634702810.9211162032330826.93589672702468.039171726
2330549.15811895 702524.462782832329702.80395228702023.594727293
2329144.64423008701920.2961161882328345.84461796701275.481943741

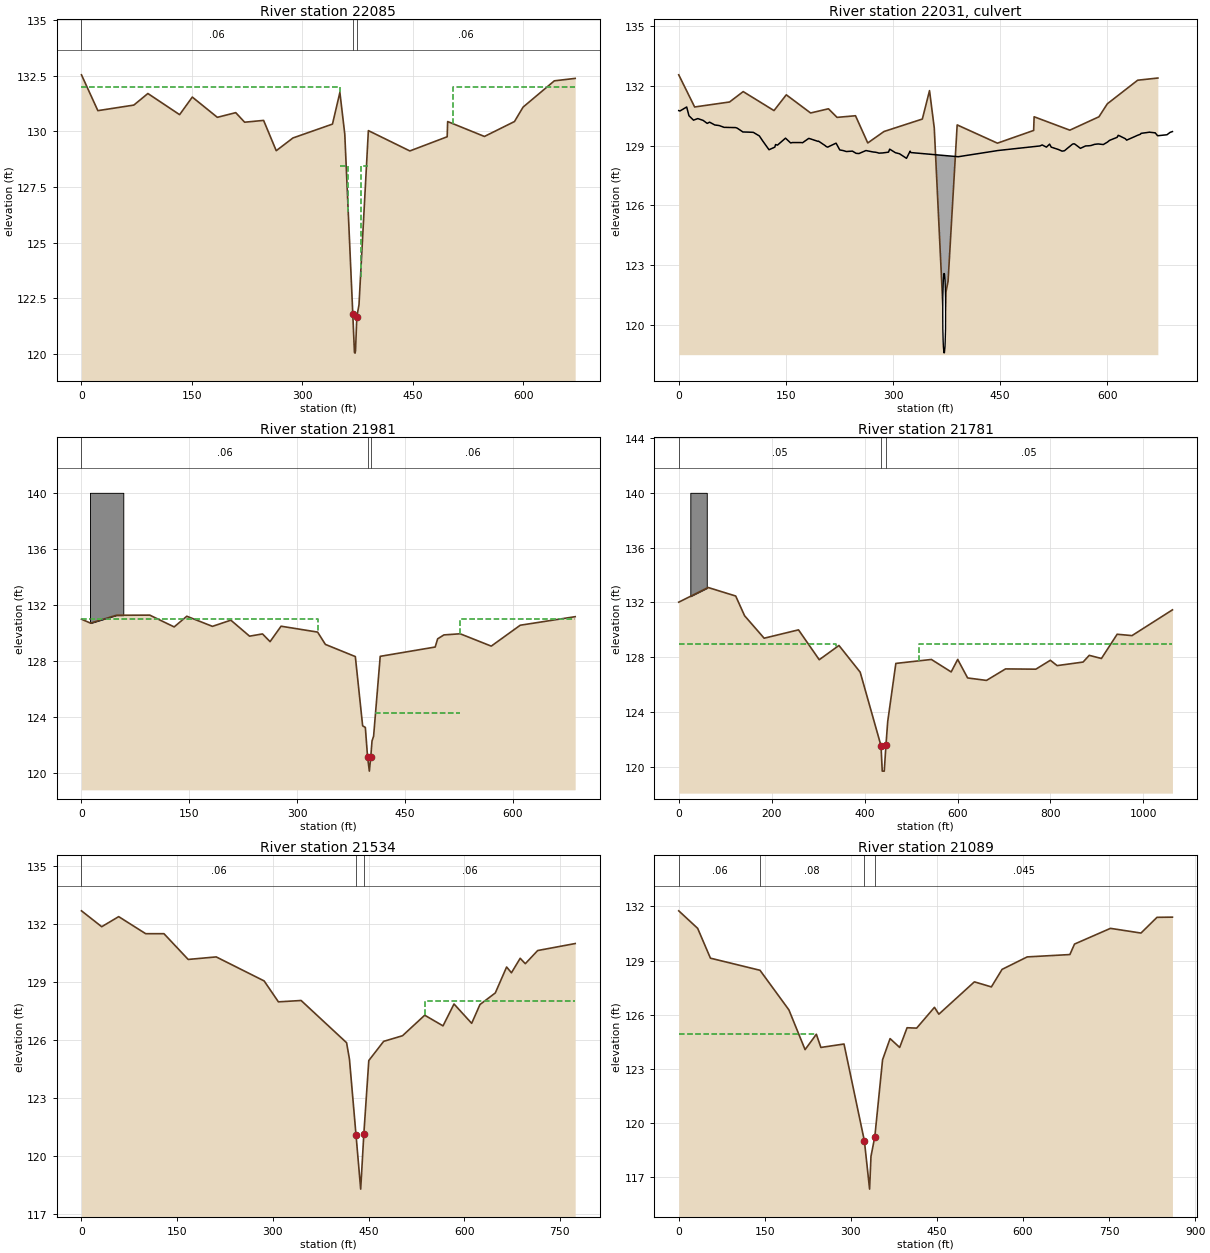
Type RM Length L Ch R = 1 ,22085   ,117.6,103.58,99.51
BEGIN DESCRIPTION:
Surveyed Section
END DESCRIPTION:
XS GIS Cut Line= 6
 2327910.2014676   716792.635257 2327866.6639239  716706.9646065
 2327803.0013001     716569.6741     2327734.908  716463.3888001
 2327627.9096517  716288.4424117 2327560.4966807  716226.6471883
#Sta/Elev= 30
       0  132.54   22.26  130.93   71.13  131.18   90.23   131.7  133.34  130.75
  150.57  131.54   184.6  130.63  209.59  130.84  221.67  130.41 247.448 130.492
 264.619  129.13 287.358 129.703  341.02 130.326 351.082 131.749 357.722 129.879
  368.64  121.78  370.87 120.059 371.742 120.032 372.345 120.151 374.089 121.668
 377.041 122.202 389.785 130.033  446.13 129.119  496.84 129.756  497.51  130.44
  547.48  129.77  588.26  130.44  600.01  131.09  642.46  132.27  670.77  132.38
#Mann= 3 ,-1 , 0
       0     .06       0  368.64    .045       0 374.089     .06       0
#XS Ineff= 4 ,-1
       0  351.08     132  351.08  362.64  128.45  379.09 389.785  128.45
  504.75     670     132
Permanent Ineff=
       F       F       F       F
Bank Sta=368.64,374.089
XS Rating Curve= 0 ,0
Exp/Cntr=0.5,0.3

Type RM Length L Ch R = 2 ,22031   ,,,
BEGIN DESCRIPTION:
Tuskegee St
END DESCRIPTION:
Bridge Culvert--1,0,-1,-1, 0
Deck Dist Width WeirC Skew NumUp NumDn MinLoCord MaxHiCord MaxSubmerge Is_Ogee
39,30,2.6,0, 97, 97, , , 0.95, 0, 1,1,,
       0    1.68   11.12   14.33   20.66   26.68   34.06   39.82   43.16   50.48
    56.7   63.57   65.34   76.81   79.42   81.89   89.82    98.9  104.43  112.86
  117.76  126.36  134.48  135.57  138.19  149.46  156.61  159.12  171.44   173.3
  182.06   194.9  195.39  195.68  204.82   206.5   208.4  220.25  225.43  230.09
  234.63  243.13  248.31  252.35  262.06  270.32  273.58  274.71   277.7  280.29
  285.64  293.66  295.29   303.4     309  318.84  323.93 324.913 391.264 447.248
 505.512  508.82  514.72  519.17  521.46  531.63  536.66  539.97  551.18  553.39
  555.01  562.31  567.68  569.52  574.54  576.99  582.11  587.27  594.34  600.01
  603.13  613.66  615.18  616.27   625.3  627.04  642.16  646.54   647.1  657.33
  658.52   665.9  666.92  670.37  683.47   687.9  691.16
  130.75  130.73  130.93  130.49  130.27  130.35  130.26  130.11  130.17  130.03
     130  129.91  129.91   129.9   129.9  129.87  129.68  129.67  129.66  129.48
  129.22  128.79  128.92  129.05  129.02  129.37  129.13  129.15  129.15  129.14
  129.36  129.21  129.21  129.22     129  128.95  128.92  129.12  128.78  128.75
   128.7  128.72  128.61   128.6  128.75  128.69  128.67  128.67  128.65  128.62
  128.63  128.67  128.82  128.64  128.59  128.36  128.72 128.649  128.44 128.753
 128.979  129.03  128.92  129.07  128.92   128.8  128.72  128.74  129.07  129.09
  129.06  128.86  128.95  128.98  128.99     129  129.06  129.08  129.05  129.17
  129.26  129.41  129.51   129.5  129.34  129.27  129.51  129.57  129.61  129.66
  129.67  129.64  129.64  129.49  129.54  129.66   129.7
                                                                                
                                                                                
                                                                                
                                                                                
                                                                                
                                                                                
                                                                                
                                                                                
                                                                                
                                                        
       0    1.68   11.12   14.33   20.66   26.68   34.06   39.82   43.16   50.48
    56.7   63.57   65.34   76.81   79.42   81.89   89.82    98.9  104.43  112.86
  117.76  126.36  134.48  135.57  138.19  149.46  156.61  159.12  171.44   173.3
  182.06   194.9  195.39  195.68  204.82   206.5   208.4  220.25  225.43  230.09
  234.63  243.13  248.31  252.35  262.06  270.32  273.58  274.71   277.7  280.29
  285.64  293.66  295.29   303.4     309  318.84  323.93 324.913 391.264 447.248
 505.512  508.82  514.72  519.17  521.46  531.63  536.66  539.97  551.18  553.39
  555.01  562.31  567.68  569.52  574.54  576.99  582.11  587.27  594.34  600.01
  603.13  613.66  615.18  616.27   625.3  627.04  642.16  646.54   647.1  657.33
  658.52   665.9  666.92  670.37  683.47   687.9  691.16
  130.75  130.73  130.93  130.49  130.27  130.35  130.26  130.11  130.17  130.03
     130  129.91  129.91   129.9   129.9  129.87  129.68  129.67  129.66  129.48
  129.22  128.79  128.92  129.05  129.02  129.37  129.13  129.15  129.15  129.14
  129.36  129.21  129.21  129.22     129  128.95  128.92  129.12  128.78  128.75
   128.7  128.72  128.61   128.6  128.75  128.69  128.67  128.67  128.65  128.62
  128.63  128.67  128.82  128.64  128.59  128.36  128.72 128.649  128.44 128.753
 128.979  129.03  128.92  129.07  128.92   128.8  128.72  128.74  129.07  129.09
  129.06  128.86  128.95  128.98  128.99     129  129.06  129.08  129.05  129.17
  129.26  129.41  129.51   129.5  129.34  129.27  129.51  129.57  129.61  129.66
  129.67  129.64  129.64  129.49  129.54  129.66   129.7
                                                                                
                                                                                
                                                                                
                                                                                
                                                                                
                                                                                
                                                                                
                                                                                
                                                                                
                                                        
BR Coef=-1 , 0 , 0 ,, 0 ,,,0.8,0,,0,
WSPro=,,,, 1 ,,,, 0 ,,,, 0 ,,,,-1 ,-1 ,-1 , 0 , 0 , 0 , 0 , 0
Culvert=1,4,,50,0.011,0.5,1,1,1,118.6089,371.6,118.8778,400.7,Culvert #1  , 0 ,28
Culvert Bottom n=0.011
BC Design=,, 0 ,, 0 ,,,,,,
BC Use User HTab Curves=0
BC User HTab FreeFlow(D)= 0

Type RM Length L Ch R = 1 ,21981   ,203.78,200.13,184.45
BEGIN DESCRIPTION:
Surveyed Section
END DESCRIPTION:
XS GIS Cut Line= 6
 2327980.4233124  716746.2888395 2327875.0905452  716513.1523149
 2327811.0595001     716393.6972    2327794.6162     716375.8898
 2327713.5803023   716230.860499 2327658.8072633  716140.9765377
#Sta/Elev= 30
       0  130.99   12.66  130.71   48.55  131.27   95.09  131.28  129.03  130.44
   146.6   131.2   182.3  130.48  207.95  130.92  233.99  129.78  251.99  129.94
  262.52  129.39  277.83  130.49  328.72  130.07 339.501 129.193 381.217 128.325
 391.389  123.39 395.169 123.271 398.261 121.156 400.735 120.158  402.73   121.2
 404.446 122.312 406.646 122.647 415.855 128.342 492.346 129.006  495.81  129.59
   504.5  129.87  527.18  129.95  570.41  129.07  610.74  130.56  687.25  131.17
#Mann= 3 , 0 , 0
       0     .06       0 398.261    .045       0  402.73     .06       0
#XS Ineff= 4 ,-1
       0  328.72     131  328.72  389.59  124.26  409.27  527.18  124.27
  527.18  687.25     131
Permanent Ineff=
       F       F       F       F
#Block Obstruct= 1 ,-1
   11.87    58.2     140
Bank Sta=398.261,402.73
XS Rating Curve= 0 ,0
Exp/Cntr=0.5,0.3

Type RM Length L Ch R = 1 ,21781   ,243.09,247.65,248.13
XS GIS Cut Line= 6
2328262.24931248716629.9881942722328249.23818468716594.207592815
2328159.78668101716490.1185704022327772.70562896716094.905563444
2327624.87770818715905.5940526282327548.77658618715851.236108333
#Sta/Elev= 30
       0  132.02   63.28  133.09  122.57  132.47  141.72  131.03  183.81  129.39
  257.76     130  302.39  127.82  344.83  128.86  390.54  126.91  435.33  121.54
  437.99  119.69  442.31  119.69  445.94  121.57  449.76  123.31  467.25  127.55
  543.71  127.84  586.34  126.93  600.38  127.84  621.73  126.49   662.3  126.31
   703.4  127.15  768.62  127.13  799.74  127.78  814.38  127.39  870.24  127.65
  883.46  128.14  909.73  127.91  943.56  129.68  975.51  129.58 1062.57  131.46
#Mann= 3 ,-1 , 0
       0     .05       0  435.33    .045       0  445.94     .05       0
#XS Ineff= 2 , 0
       0  338.49     129  516.04       0     129
Permanent Ineff=
       F       F
#Block Obstruct= 1 ,-1
    24.9    60.3     140
Bank Sta=435.33,445.94
XS Rating Curve= 0 ,0
Exp/Cntr=0.3,0.1

Type RM Length L Ch R = 1 ,21534   ,464.96,444.85,432.44
XS GIS Cut Line= 5
 2328401.5155571   716523.646708 2328350.3291656  716434.0705228
 2328228.7614857  716242.1215546 2328081.6006101  716030.9776895
 2327962.1656965  715888.0823465
#Sta/Elev= 30
       0  132.67   31.72  131.85   58.34  132.37  100.61  131.49  129.29  131.49
  167.27  130.16  211.27  130.29  286.34  129.05  308.75  127.97  344.32  128.04
   415.6  125.86  420.11  125.01  430.41  121.09  437.72   118.3  442.69  121.17
  450.44  124.94  473.71  125.93  503.26  126.22   538.1  127.28  566.79  126.73
  584.02  127.86  611.71  126.86  624.68  127.83  648.75  128.43  666.49  129.77
  674.03  129.47  687.76  130.22  695.77  129.94  715.19  130.62  773.98  130.98
#Mann= 3 , 0 , 0
       0     .06       0  430.41    .045       0  442.69     .06       0
#XS Ineff= 2 , 0
       0                   538.1       0     128
Permanent Ineff=
       F       F
Bank Sta=430.41,442.69
XS Rating Curve= 0 ,0
Exp/Cntr=0.3,0.1

Type RM Length L Ch R = 1 ,21089   ,129.29,123.1,116.26
XS GIS Cut Line= 6
 2328804.6083905  716033.1104558 2328751.2892326  715996.8534285
 2328651.0492159  715935.0032054 2328399.3827909  715828.3648897
 2328284.2134099  715785.7095634 2328024.0159196  715676.9384814
#Sta/Elev= 30
       0  131.75   32.99  130.78   55.23  129.13  141.63  128.46  191.97  126.27
  220.17  124.07  239.82  124.92  247.72  124.19  288.03  124.38  323.52  119.02
  332.61  116.35  335.02  118.16  341.71  119.25  355.23  123.51  368.31  124.68
  385.04  124.19  397.93  125.28  414.62  125.26  445.67  126.41   453.3  126.03
  515.25  127.82  544.85  127.54  563.49  128.51  607.25   129.2  681.65  129.33
  689.74  129.91  752.39  130.78  805.59  130.52  833.49  131.39  860.42   131.4
#Mann= 4 ,-1 , 0
       0     .06       0  141.63     .08       0  323.52    .045       0
  341.71    .045       0
#XS Ineff= 2 , 0
       0  238.19  124.95  366.73       0   124.5
Permanent Ineff=
       F       F
Bank Sta=323.52,341.71
XS Rating Curve= 0 ,0
Exp/Cntr=0.3,0.1

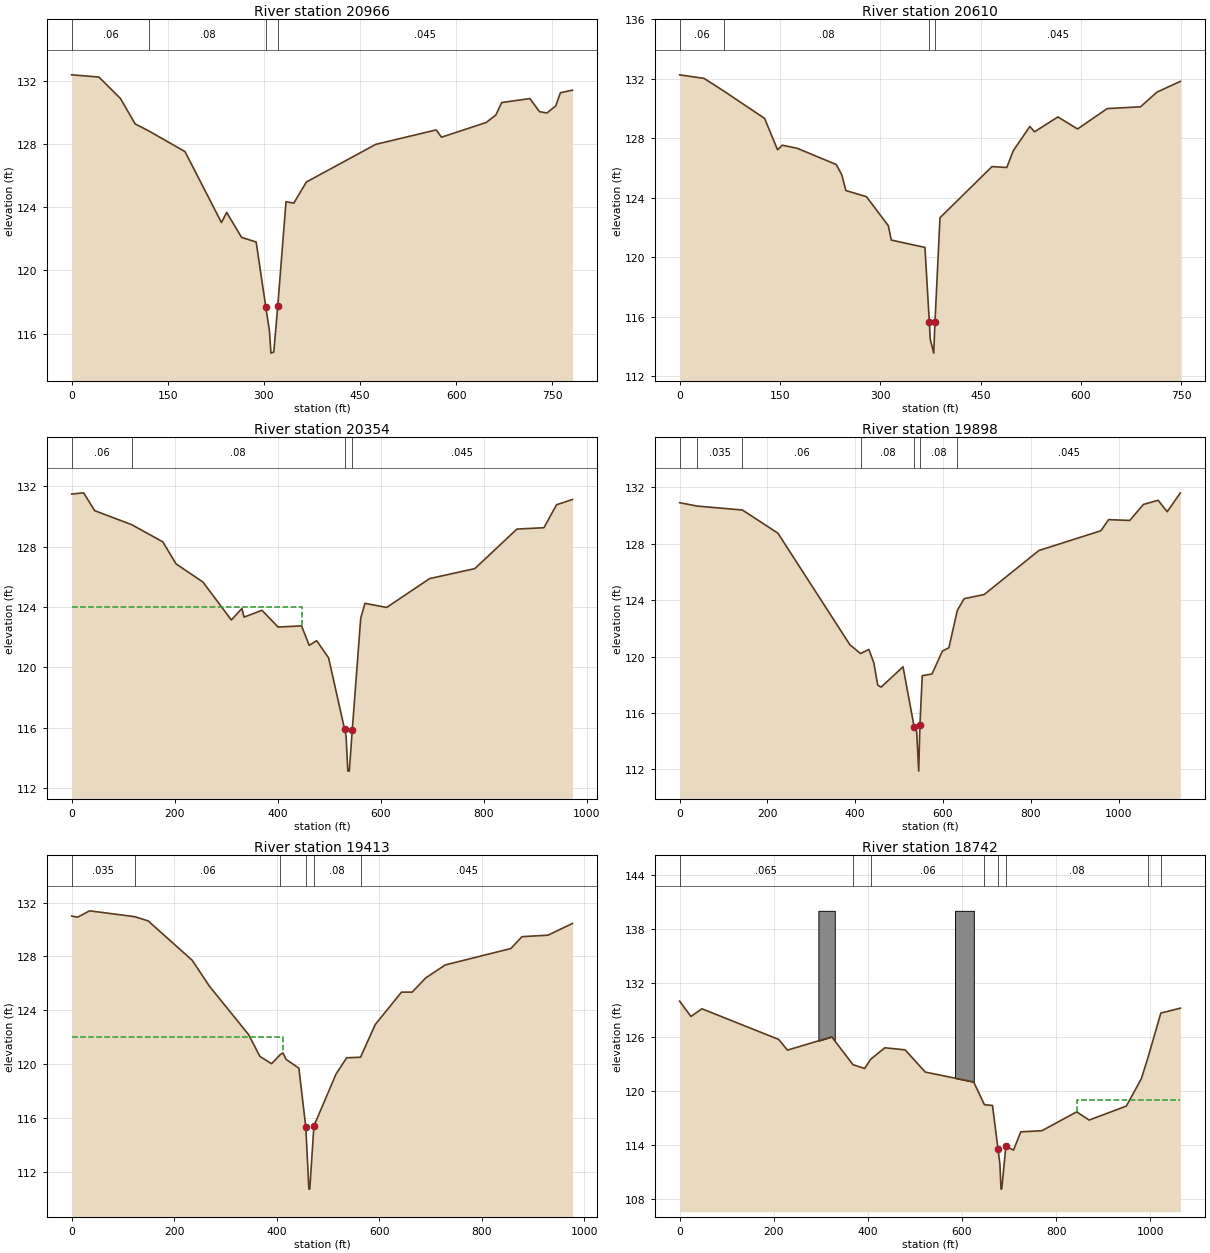
Type RM Length L Ch R = 1 ,20966   ,338.59,355.17,360.78
XS GIS Cut Line= 4
 2328828.0688199  715860.3563844 2328633.9870853  715787.8423297
 2328360.9929972  715706.7972098 2328085.8661427  715617.2210246
#Sta/Elev= 30
       0  132.36   42.48  132.22   76.17  130.86   99.01  129.26  120.55  128.81
  176.79  127.51  233.66  123.03  241.77  123.67   265.1  122.09  287.81   121.8
  302.91  117.68  308.56  116.18  310.84  114.78  315.28  114.85   321.5  117.75
  334.38  124.35  346.48  124.25  366.14  125.59  474.58  127.97  568.71  128.88
     577  128.42  646.82  129.35  661.75  129.82  670.88  130.61  714.92  130.86
  729.97  130.03  741.55  129.95  755.31   130.4  762.45  131.23   781.3  131.39
#Mann= 4 ,-1 , 0
       0     .06       0  120.55     .08       0  302.91    .045       0
   321.5    .045       0
Bank Sta=302.91,321.5
XS Rating Curve= 0 ,0
Exp/Cntr=0.3,0.1

Type RM Length L Ch R = 1 ,20610   ,261.86,256.56,255.34
BEGIN DESCRIPTION:
Surveyed Section
END DESCRIPTION:
XS GIS Cut Line= 6
 2328950.8892068  715781.4406925 2328893.3072942  715683.1301099
     2328671.064     715432.9344 2328598.3755461  715375.5584298
 2328508.4915849  715346.0652551 2328397.5410702  715340.4475075
#Sta/Elev= 30
       0  132.26   36.46  132.02   65.72  131.18  127.04  129.33  146.36  127.22
  153.52  127.53  175.76  127.32  234.14  126.23  242.44  125.53  248.49  124.48
  279.21  124.07  311.89  122.12 316.462 121.149 366.685 120.657  373.25  115.63
 374.545 114.501 379.784  113.55  381.73  115.67  389.14 122.651   466.9  126.09
  489.01  126.03  498.71  127.16  523.52  128.79  530.44  128.43  565.42  129.43
  594.85  128.62  639.08  129.99  688.92  130.11  713.57   131.1  748.49  131.82
#Mann= 4 ,-1 , 0
       0     .06       0   65.72     .08       0  373.25    .045       0
  381.73    .045       0
Bank Sta=373.25,381.73
XS Rating Curve= 0 ,0
Exp/Cntr=0.3,0.1

Type RM Length L Ch R = 1 ,20354   ,462.06,455.62,447.67
XS GIS Cut Line= 4
 2329275.9497458  715666.2746498 2328985.8935272  715363.4218333
 2328723.5632705  715169.3400987  2328529.481536  715052.0379514
#Sta/Elev= 30
       0  131.48   23.15  131.56   44.63  130.38   116.6  129.45  177.04  128.31
  202.51  126.86  254.91  125.65  310.03  123.14  330.51   123.9  334.66  123.33
  369.57  123.78  400.82  122.67  446.33  122.75  461.22  121.46  475.66  121.77
  498.92  120.63  529.88  115.91  532.79  115.47  536.22  113.14  539.08  113.13
  544.91  115.88  561.27  123.26  569.52  124.24  611.67  123.97  695.09  125.88
  782.82  126.54  864.61  129.16  917.07  129.25  941.55  130.77  972.44  131.12
#Mann= 4 ,-1 , 0
       0     .06       0   116.6     .08       0  529.88    .045       0
  544.91    .045       0
#XS Ineff= 2 , 0
       0  446.33     124               0
Permanent Ineff=
       F       F
Bank Sta=529.88,544.91
XS Rating Curve= 0 ,0
Exp/Cntr=0.3,0.1

Type RM Length L Ch R = 1 ,19898   ,469.77,485.06,478.45
XS GIS Cut Line= 6
 2329704.6357749  715293.0405449 2329610.7940571  715233.3230881
 2329307.9412405  715056.3034841 2329066.9386471  714930.4702716
 2328881.3879778  714823.8319559 2328708.6339064  714738.5213033
#Sta/Elev= 30
       0  130.91   40.15  130.67  143.03  130.39  223.81  128.75  387.69  120.84
  411.98  120.21  431.06   120.5  442.36  119.55  451.22  117.97  459.05  117.83
  508.86  119.27  534.36  114.98  539.93  114.67  544.56  111.87  547.35  115.16
  552.65  118.64  574.82  118.76   598.6  120.39   613.3  120.62  632.57  123.28
     648   124.1  693.83   124.4  818.38  127.52  959.48  128.92  977.17  129.71
 1025.21  129.65 1056.49  130.79 1089.95  131.08 1110.55  130.27 1140.58  131.61
#Mann= 7 ,-1 , 0
       0     .06       0   40.15    .035       0  143.03     .06       0
  411.98     .08       0  534.36    .045       0  547.35     .08       0
  632.57    .045       0
Bank Sta=534.36,547.35
XS Rating Curve= 0 ,0
Exp/Cntr=0.3,0.1

Type RM Length L Ch R = 1 ,19413   ,643.21,671.44,676.74
XS GIS Cut Line= 6
 2329952.0366673  715002.9843262 2329785.6808948  714883.5494127
 2329606.5285245  714774.7783307  2329446.571051  714638.2812866
 2329310.0740069  714540.1740361 2329162.9131312  714429.2701878
#Sta/Elev= 30
       0     131   11.63  130.92   34.97  131.39  123.79  130.95  149.22  130.64
  235.24  127.71  268.51   125.8  345.22  122.19  367.28  120.57  389.98  120.03
  407.03  120.71  412.25  120.83  418.28  120.35  443.27   119.7  456.79  115.31
  462.75  110.71  464.52  110.72  472.59   115.4  515.56  119.25  536.49  120.47
  563.55  120.51  592.25  122.94  643.51  125.35  664.28  125.35  690.93  126.41
  728.87  127.37  856.86  128.59  878.54  129.47  929.33  129.58  977.03  130.45
#Mann= 6 ,-1 , 0
       0    .035       0  123.79     .06       0  407.03     .08       0
  456.79    .045       0  472.59     .08       0  563.55    .045       0
#XS Ineff= 2 , 0
       0  412.25     122               0
Permanent Ineff=
       F       F
Bank Sta=456.79,472.59
XS Rating Curve= 0 ,0
Exp/Cntr=0.3,0.1

Type RM Length L Ch R = 1 ,18742   ,443.9,483.67,454.45
XS GIS Cut Line= 5
 2330397.7848269  714943.2668694 2330252.7567176  714644.6795855
 2330135.4545703  714433.5357204 2330005.3558252   714192.533127
  2329909.381341  713998.4513924
#Sta/Elev= 30
       0  129.97   23.99  128.27   47.32  129.12  210.32  125.72  229.12  124.53
  323.15     126  368.42  122.91  393.05  122.49  405.87  123.51  435.96  124.79
  479.01  124.56  521.94  122.09  624.81  120.99  647.47  118.47  664.73  118.38
  676.42  113.54  680.45  111.86  682.81  109.09   684.4  109.11  693.11  113.89
  709.28  113.42   724.8  115.45   769.7  115.58  843.65  117.67  869.96  116.76
     949  118.31     981  121.36   994.4  123.59 1022.38  128.64 1063.88  129.19
#Mann= 8 ,-1 , 0
       0    .065       0  368.42    .035       0  405.87     .06       0
  647.47     .08       0  676.42    .045       0  693.11     .08       0
   994.4    .045       0 1022.38    .035       0
#XS Ineff= 2 , 0
       0                  843.65       0     119
Permanent Ineff=
       F       F
#Block Obstruct= 2 ,-1
   294.8   329.6     140     585     625     140
Bank Sta=676.42,693.11
XS Rating Curve= 0 ,0
Exp/Cntr=0.3,0.1

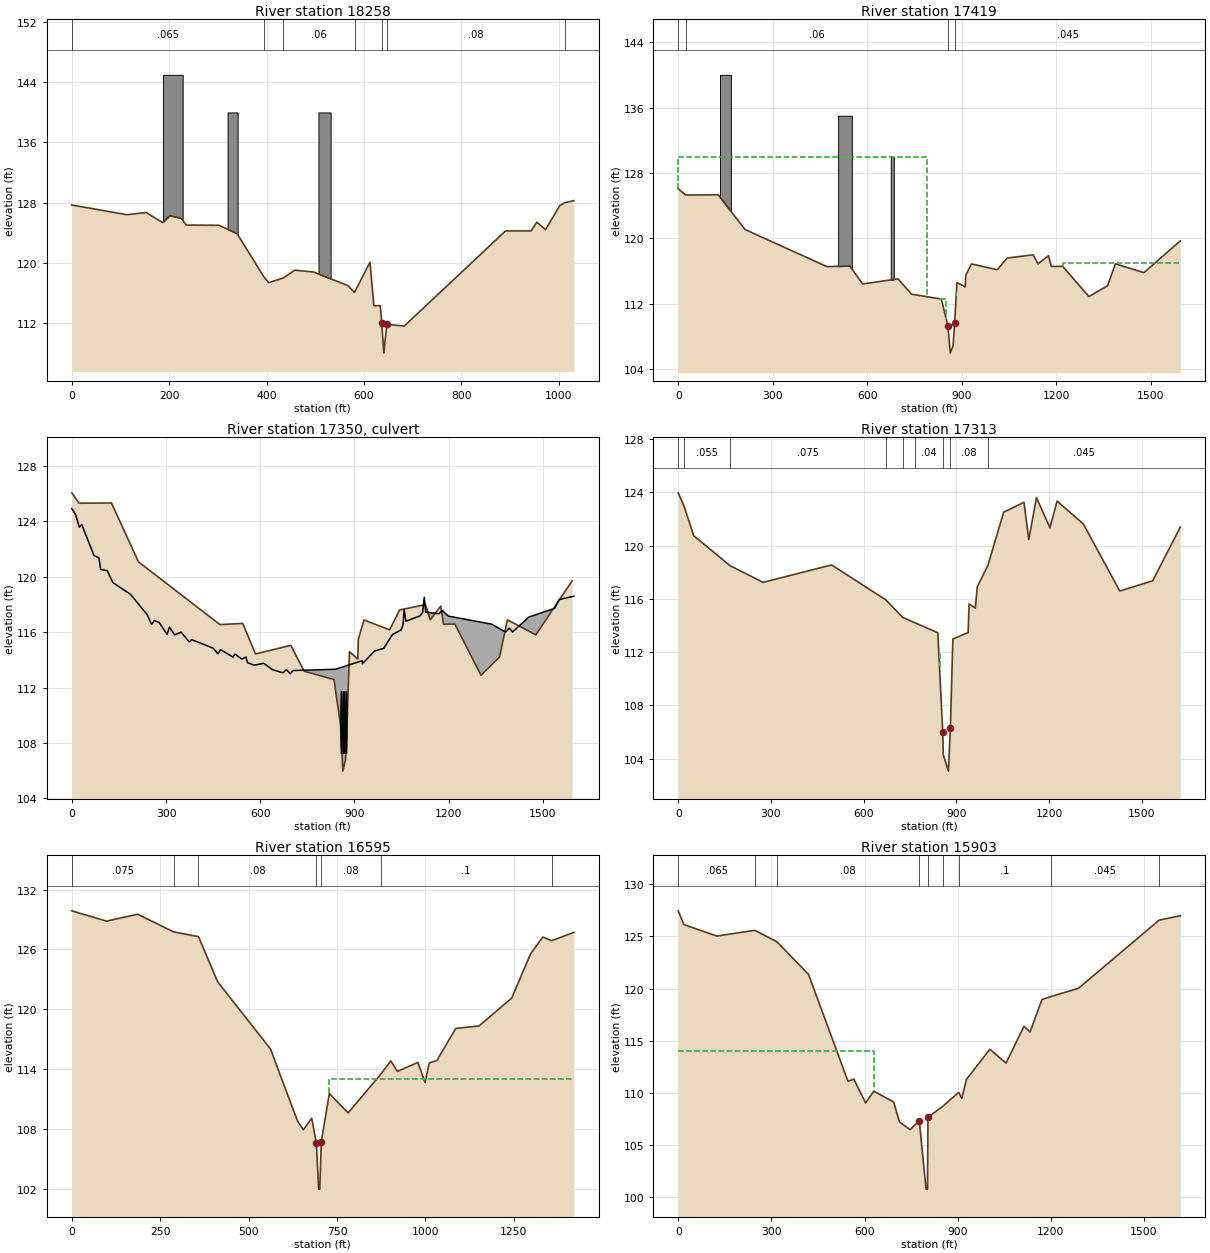
Type RM Length L Ch R = 1 ,18258   ,845.16,838.83,839.6
XS GIS Cut Line= 5
 2330852.0640518  714868.6200484 2330707.0359424   714661.741716
 2330579.0699636  714448.4650846 2330455.3695174  714171.2054638
 2330363.6605659  713964.3271314
#Sta/Elev= 30
       0  127.68  113.06  126.39  152.88  126.68  186.31  125.35  201.26  126.28
  224.87  125.91  235.26  125.01  302.71  124.98  339.53  123.87  394.77  118.11
  404.33  117.34  434.68  117.97  458.04  119.01  496.97  118.76  567.17  116.96
  580.81  116.04  612.52  120.07  620.53  114.27  633.77  114.28  636.72  111.93
  641.01  107.97  647.11   111.8  682.87  111.57  890.96  124.23  943.29  124.23
  955.39   125.4  972.98  124.39 1002.04  127.57 1012.29  127.98 1031.27  128.26
#Mann= 7 ,-1 , 0
       0    .065       0  394.77    .035       0  434.68     .06       0
  580.81     .08       0  636.72    .045       0  647.11     .08       0
 1012.29    .045       0
#XS Ineff= 2 , 0
       0     612     120               0
Permanent Ineff=
       F       F
#Block Obstruct= 3 ,-1
   187.4   227.8     145     320   340.7     140   506.7   531.7     140
Bank Sta=636.72,647.11
XS Rating Curve= 0 ,0
Exp/Cntr=0.5,0.3

Type RM Length L Ch R = 1 ,17419   ,117.97,106.11,85.6
BEGIN DESCRIPTION:
Surveyed Section
END DESCRIPTION:
XS GIS Cut Line= 6
  2331974.214739  714901.4089433 2331510.4001858  714515.5152351
 2331335.8770001     714363.6839    2331309.4143      714337.624
    2331289.8354     714304.2625  2330647.705117  714073.9637805
#Sta/Elev= 30
       0  126.06   23.26  125.31  126.39  125.33  212.26  121.08  471.79  116.55
  544.41  116.63  585.01  114.43  697.33  115.05  740.16  113.18  834.74 112.583
 855.768  109.31 863.095 105.971 872.016  106.85  876.93  109.67 884.283  114.59
 910.727 114.067  912.28  115.48  930.37  116.88 1012.14  116.17 1043.76   117.6
 1126.06  117.99 1141.66  116.89 1174.86  117.89 1183.69  116.57  1219.7  116.59
 1302.96  112.89 1362.15  114.21 1387.08  116.89 1477.56  115.81 1593.02   119.7
#Mann= 4 ,-1 , 0
       0    .035       0   23.26     .06       0 855.768    .045       0
  876.93    .045       0
#XS Ineff= 4 ,-1
       0     788     130     832  850.77  112.61  881.93   882.7   113.5
  1219.7 1593.02     117
Permanent Ineff=
       F       F       F       F
#Block Obstruct= 3 ,-1
   132.4     167     140   507.2   550.8     135   674.2     684     130
Bank Sta=855.768,876.93
XS Rating Curve= 0 ,0
Exp/Cntr=0.5,0.3

Type RM Length L Ch R = 2 ,17350   ,,,
BEGIN DESCRIPTION:
Lane Street
END DESCRIPTION:
Bridge Culvert--1,0,-1,-1, 0
Deck Dist Width WeirC Skew NumUp NumDn MinLoCord MaxHiCord MaxSubmerge Is_Ogee
57,28,2.6,0, 60, 60, , , 0.95, 0, 1,1,,
       0   11.73   24.29   31.71   70.74    86.4   92.08  112.95  130.85  187.56
  240.79   254.1  262.72  278.31   303.5  311.07  327.31  348.23  373.97  382.19
   449.9  465.67  474.03  513.03  519.62  541.42  554.89  559.31  580.48  611.48
  639.17  672.69  683.18   695.8  704.23 839.758 924.645  925.43   964.8  992.92
 1021.09 1048.76 1055.03 1058.23 1063.94 1108.08 1117.44 1122.44  1126.8 1169.52
 1179.35 1199.39 1336.86  1381.5  1392.9 1403.71 1454.86 1537.51 1551.64 1598.63
  124.92  124.51  123.58  123.77  121.54  121.36  120.53  120.44  119.58  118.72
  117.24  116.56  116.84   116.7  115.83  116.37  115.81     116   115.3  115.46
  114.85  114.44  114.74   114.2  114.42  114.06   114.2   113.8  113.62  113.75
  113.29  113.07   113.3     113  113.23 113.325  113.94  113.73  114.65  114.83
  115.83  116.17  116.56  117.66  116.79  117.17  117.45  118.52  117.45  117.33
  117.57  117.16  116.58     116  116.29  116.02  117.09  117.72  118.35   118.6
                                                                                
                                                                                
                                                                                
                                                                                
                                                                                
                                                                                
       0   11.73   24.29   31.71   70.74    86.4   92.08  112.95  130.85  187.56
  240.79   254.1  278.31   303.5  311.07  327.31  348.23  373.97   449.9  465.67
  474.03  513.03  554.89  559.31  580.48  611.48   695.8  925.43   964.8  992.92
 1021.09 1048.76 1055.03 1058.23 1063.94 1108.08 1117.44 1122.44  1126.8 1179.35
 1232.06 1243.09 1258.39 1268.93 1283.35 1294.41 1313.17 1336.86  1381.5  1392.9
 1403.71 1414.93 1430.71 1445.04 1454.86 1466.39 1492.77 1537.51 1551.64 1598.63
  124.92  124.51  123.58  123.77  121.54  121.36  120.53  120.44  119.58  118.72
  117.24  116.56   116.7  115.83  116.37  115.81     116   115.3  114.85  114.44
  114.74   114.2   114.2   113.8  113.62  113.75     113  113.73  114.65  114.83
  115.83  116.17  116.56  117.66  116.79  117.17  117.45  118.52  117.45  117.57
  117.07  117.35  116.53   116.8  115.88  116.17  115.62  116.58     116  116.29
  116.02  116.39  115.18  116.61  117.09  116.76  117.41  117.72  118.35   118.6
                                                                                
                                                                                
                                                                                
                                                                                
                                                                                
                                                                                
BR Coef=-1 , 0 , 0 ,, 0 ,,,0.8,0,,0,
WSPro=,,,, 1 ,,,, 0 ,,,, 0 ,,,,-1 ,-1 ,-1 , 0 , 0 , 0 , 0 , 0
Multiple Barrel Culv=1,4.5,,41,0.023,0.5,1,2,1,107.22,107.52, 3,Culvert #1  , 0 ,48
  858.95  860.39  866.65  868.09  874.35  875.79
Culvert Bottom n=0.023
BC Design=,, 0 ,, 0 ,,,,,,
BC Use User HTab Curves=0
BC User HTab FreeFlow(D)= 0

Type RM Length L Ch R = 1 ,17313   ,736.51,718.11,706.14
BEGIN DESCRIPTION:
Surveyed Section
END DESCRIPTION:
XS GIS Cut Line= 6
 2332089.2407482  714758.5540609 2331629.1367114   714383.791902
    2331449.6247     714294.3605 2331369.9714999     714268.1416
    2331323.7264     714233.8808 2330676.4787614  714004.9258055
#Sta/Elev= 30
       0  123.96   18.85  122.95    50.2  120.74  167.99  118.49  274.45  117.24
   496.2  118.55  671.64  115.93  726.88   114.6  765.87  114.21 839.953 113.459
 855.874 106.042 857.661 104.301 874.233 103.074 880.569 106.298 888.693  112.99
 938.082 113.478  941.13  115.62  961.69  115.31   967.4  116.89 1001.93  118.51
 1053.13  122.51 1118.77  123.25 1134.32  120.45 1159.17   123.6 1202.76  121.34
 1225.96  123.34 1311.02  121.62 1428.85  116.59  1535.3  117.36 1624.67  121.39
#Mann= 9 ,-1 , 0
       0    .035       0   18.85    .055       0  167.99    .075       0
  671.64     .04       0  726.88     .08       0  765.87     .04       0
 855.874    .045       0 880.569     .08       0 1001.93    .045       0
#XS Ineff= 3 ,-1
                           843.1  845.87   111.9  887.39  887.64   111.9
Permanent Ineff=
       F       F       F
Bank Sta=855.874,880.569
XS Rating Curve= 0 ,0
Exp/Cntr=0.5,0.3

Type RM Length L Ch R = 1 ,16595   ,674.9,691.85,683.35
XS GIS Cut Line= 6
 2331952.5714697   713716.926239 2331781.9501646   713642.279418
 2331568.6735332  713593.2257928  2331193.306662  713565.4998307
 2330945.9057696  713546.3049339 2330557.7423005  713510.0479065
#Sta/Elev= 30
       0  129.87   98.39  128.84  186.24  129.53  288.15  127.76  358.27  127.29
  412.47  122.77   561.8  116.05  638.12  108.84  654.97  107.96  678.48  109.11
  691.42  106.66  698.05  102.02  701.27  102.02   705.4  106.74  728.11  111.59
  781.31  109.65  873.11   113.5   902.1  114.85  920.68   113.8  978.48   114.7
  998.94  112.69 1010.64  114.65 1032.12  114.89 1085.62   118.1 1151.47  118.35
 1243.84  121.14 1297.29  125.58 1331.84  127.25 1356.59  126.88 1419.47  127.71
#Mann= 7 ,-1 , 0
       0    .075       0  288.15     .04       0  358.27     .08       0
  691.42    .045       0   705.4     .08       0  873.11      .1       0
 1356.59    .045       0
#XS Ineff= 2 , 0
       0                  728.11       0     113
Permanent Ineff=
       F       F
Bank Sta=691.42,705.4
XS Rating Curve= 0 ,0
Exp/Cntr=0.3,0.1

Type RM Length L Ch R = 1 ,15903   ,329.77,432.23,353.64
XS GIS Cut Line= 6
 2332050.6787201  712968.3252628 2331826.7382572  712964.0597302
  2331662.515251  712932.0682355 2331203.9704935  712902.2095071
 2330988.5610959  712859.5541808 2330442.5729195  712846.7575829
#Sta/Elev= 30
       0  127.46   18.03  126.14  124.33  125.04  246.58  125.59  317.89  124.49
  419.72  121.35  546.75  111.09  565.27  111.31  603.44  109.01  629.88  110.14
  693.72  109.11  712.37   107.2  746.79  106.45  776.32   107.3  798.13  100.74
   802.8  100.74  804.26  107.64  852.29   108.7  903.06  110.03  913.31  109.46
  928.15  111.27 1003.51  114.17 1055.64  112.84 1113.46  116.38 1132.96  115.83
 1171.33  118.94 1198.96  119.22 1288.79  120.02 1549.02  126.57 1616.93  126.99
#Mann= 9 ,-1 , 0
       0    .065       0  246.58     .04       0  317.89     .08       0
  776.32    .045       0  804.26     .08       0  852.29    .035       0
  903.06      .1       0 1198.96    .045       0 1549.02     .09       0
#XS Ineff= 2 , 0
       0   629.5     114               0
Permanent Ineff=
       F       F
Bank Sta=776.32,804.26
XS Rating Curve= 0 ,0
Exp/Cntr=0.3,0.1