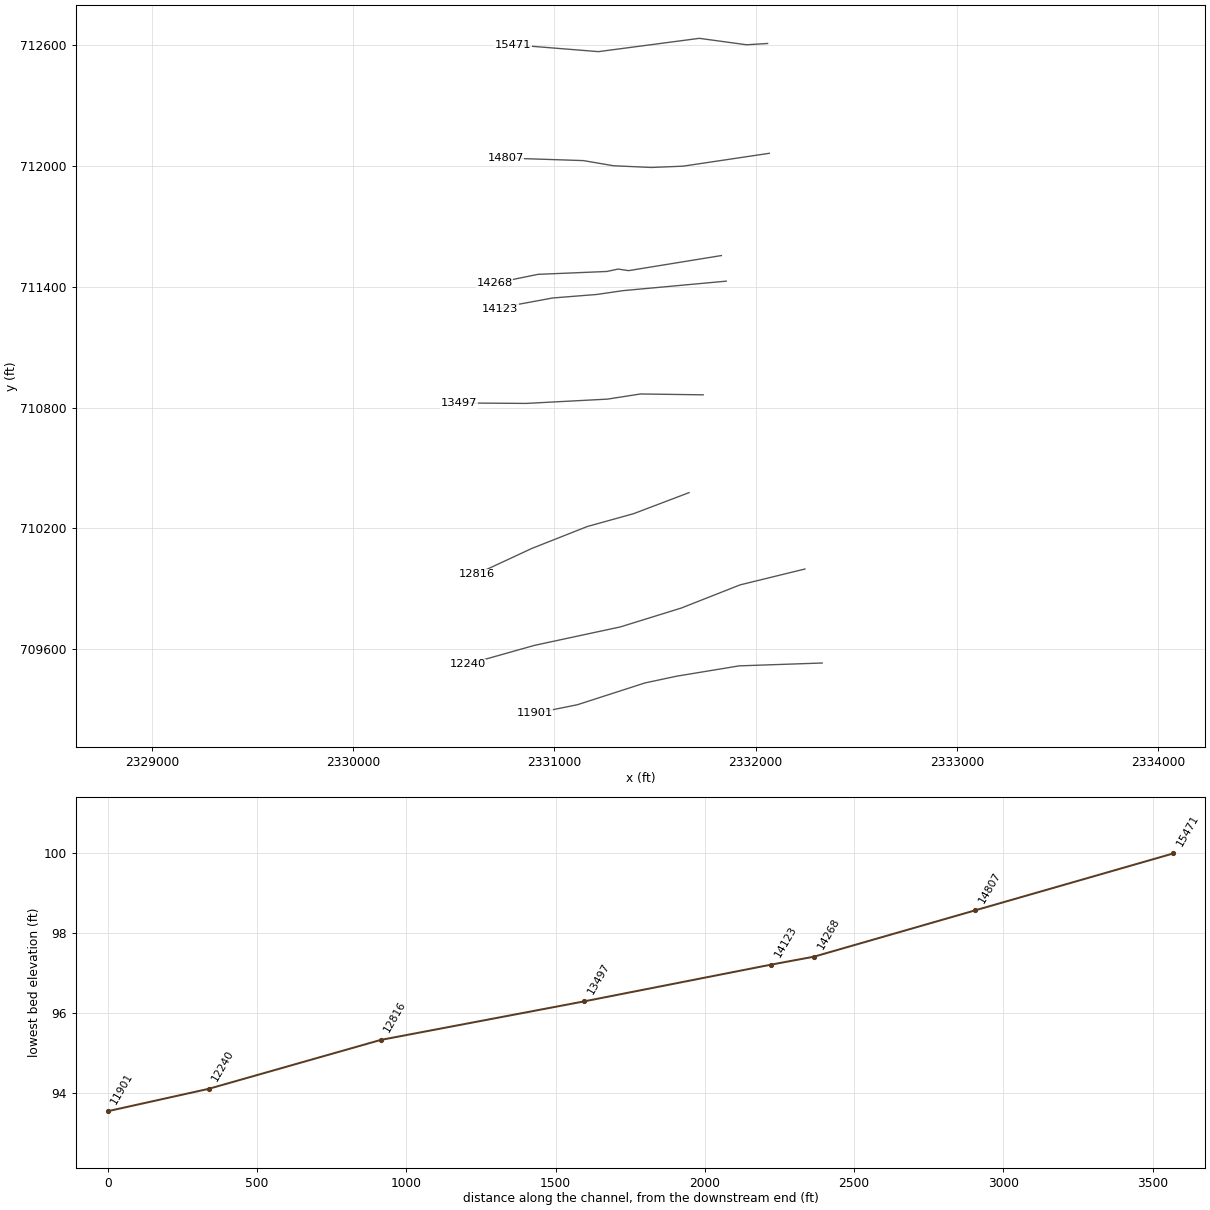
HEC-RAS study dtl_Hominy_Swamp_Trib1.prj: DTL_Hominy_Swamp_Trib1

--- dtl_Hominy_Swamp_Trib1.g01 (geometry) --- (continued)

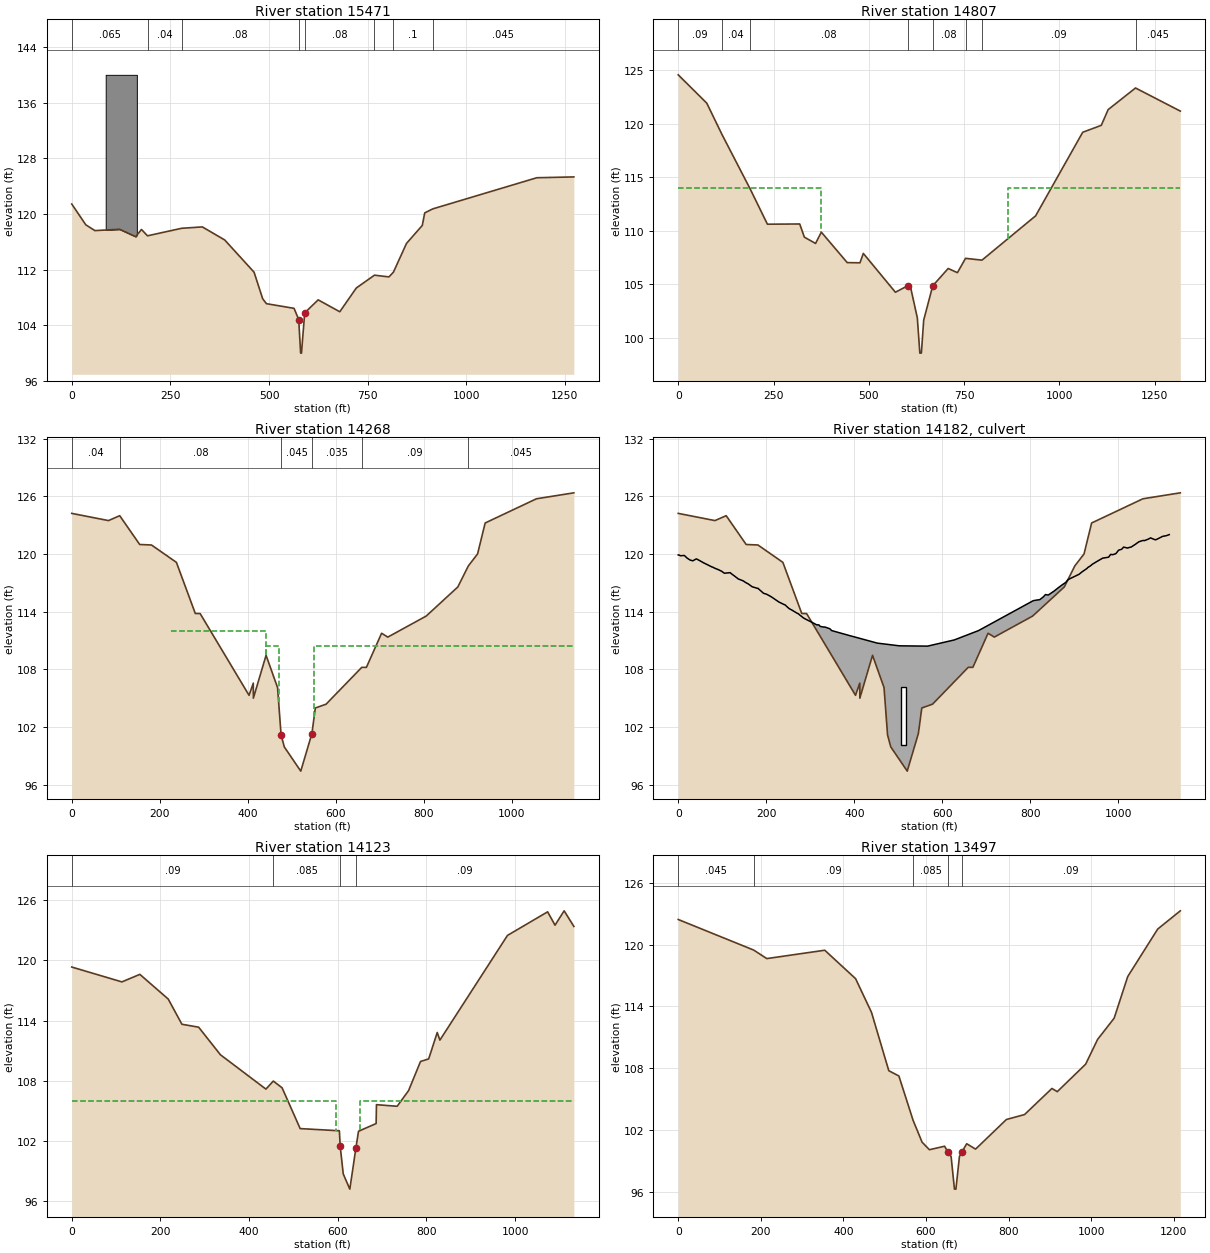
Type RM Length L Ch R = 1 ,15471   ,618.96,664.25,612.1
XS GIS Cut Line= 5
 2332059.2097854  712610.0205221  2331954.704236  712603.6222232
 2331720.0999415  712635.6137179 2331218.8998578  712569.4979621
 2330794.4793613  712603.6222232
#Sta/Elev= 30
       0  121.42   35.61  118.43   58.65   117.6  121.26  117.79  162.05  116.73
  176.71  117.76  192.07  116.85  278.36  117.93  330.99  118.13  387.78  116.25
  462.15  111.62  483.92  107.81   493.5  107.09  563.55  106.42  575.34  104.81
  580.19   99.99  582.31   99.98  590.51  105.77  624.61  107.64  679.45  105.93
   721.4  109.35  767.38  111.19  804.09  110.94  815.49  111.63  848.51  115.75
  888.56  118.34  894.84  120.15  915.02  120.72 1178.84   125.2 1272.81  125.32
#Mann= 8 ,-1 , 0
       0    .065       0  192.07     .04       0  278.36     .08       0
  575.34    .045       0  590.51     .08       0  767.38    .035       0
  815.49      .1       0  915.02    .045       0
#Block Obstruct= 1 ,-1
      86     165     140
Bank Sta=575.34,590.51
XS Rating Curve= 0 ,0
Exp/Cntr=0.3,0.1

Type RM Length L Ch R = 1 ,14807   ,528.98,539.18,534.37
XS GIS Cut Line= 6
 2332067.7408507  712064.0323458 2331639.0548216  712000.0493563
 2331481.2301143  711993.6510574 2331293.5466787  712002.1821227
 2331144.2530368  712027.7753184 2330758.2223339  712040.5719163
#Sta/Elev= 30
       0  124.57   74.93  121.92     115  118.98  188.24  113.94  233.98  110.61
  318.79  110.63   330.9   109.4  360.34  108.81   375.4  109.87  443.36  107.02
  476.77     107  485.62  107.88   569.8  104.25   601.8  104.85  609.16  104.78
   627.3  101.86  633.88   98.56  637.92   98.56     644  101.64  667.75  104.85
  708.27  106.47  732.49  106.08  753.75  107.42  796.95  107.25  937.64  111.39
 1061.19   119.2 1109.98  119.85 1127.96  121.32 1199.78  123.34 1317.28  121.18
#Mann= 8 ,-1 , 0
       0     .09       0     115     .04       0  188.24     .08       0
   601.8    .045       0  667.75     .08       0  753.75    .035       0
  796.95     .09       0 1199.78    .045       0
#XS Ineff= 2 , 0
       0     375     114     865       0     114
Permanent Ineff=
       F       F
Bank Sta=601.8,667.75
XS Rating Curve= 0 ,0
Exp/Cntr=0.5,0.3

Type RM Length L Ch R = 1 ,14268   ,126.49,144.74,128.73
BEGIN DESCRIPTION:
Surveyed Section
END DESCRIPTION:
XS GIS Cut Line= 6
 2331829.6660711  711555.7470907 2331368.5720001     711480.6882
    2331316.5845     711488.5703    2331260.6702     711476.5496
 2330918.4070549  711462.2336109 2330703.5250161  711418.4613438
#Sta/Elev= 30
       0  124.24   83.42  123.49  108.93     124  154.32     121 181.091  120.95
  237.73  119.14  280.61  113.82  291.62  113.81  402.72   105.3 412.411  106.57
 412.546 105.001 441.403 109.465 467.522 106.101 475.506 101.178 482.806  99.927
 520.217  97.406 545.537 101.318 553.293 103.978 577.702 104.375 658.801  108.21
  669.35  108.21  703.85  111.76  718.01  111.36  805.18  113.55  877.04  116.58
  900.94  118.77 921.879  120.02  939.12  123.241055.599  125.76 1140.58  126.38
#Mann= 6 ,-1 , 0
       0     .04       0  108.93     .08       0 475.506    .045       0
 545.537    .035       0 658.801     .09       0  900.94    .045       0
#XS Ineff= 3 ,-1
     225   441.4     112   441.4  470.51  110.45  550.54 1140.58  110.45
Permanent Ineff=
       F       F       F
Bank Sta=475.506,545.537
XS Rating Curve= 0 ,0
Exp/Cntr=0.5,0.3

Type RM Length L Ch R = 2 ,14182   ,,,
BEGIN DESCRIPTION:
Charleston Road
END DESCRIPTION:
Bridge Culvert--1,0,-1,-1, 0
Deck Dist Width WeirC Skew NumUp NumDn MinLoCord MaxHiCord MaxSubmerge Is_Ogee
70,22,2.6,0, 118, 118, , , 0.95, 0, 1,1,,
       0     .99    5.09   13.84  20.501   27.08   32.91   41.03   43.56   51.62
  58.441    59.1   67.34   77.05   78.71   81.06   91.61   98.49  104.67  109.54
  117.59  117.98  120.17  134.36  135.61  147.74   152.8  159.36  167.53  168.83
  180.33  180.97  181.46  182.23  193.78 200.929  208.88  213.19  228.44  239.45
  243.35  244.31  251.81  258.66  270.99  272.71  275.99   284.6  288.99  290.99
 301.651  314.43  319.59 322.609  330.23  333.18 344.419  348.56  388.08 452.221
 502.083 566.446 627.131 682.236  806.38  813.44  821.41  828.69  834.29  840.61
  850.87  851.38  851.78  852.91   864.3  872.51 880.201 884.499  886.45  894.51
  895.01  895.72  910.61 917.849  928.13  930.57 935.919  938.11  940.55  951.41
  963.14 963.911  964.65  965.88  977.68  982.32 987.369  994.26 1000.39 1007.29
 1011.81 1020.88    1025 1029.23 1032.38 1037.22 1046.35 1055.02 1057.47 1058.96
 1068.48 1072.86 1083.46 1084.87 1085.39 1100.57  1108.2 1115.49
  119.91  119.92  119.83  119.86  119.57  119.38   119.3   119.5  119.45  119.25
  119.07  119.06  118.87  118.65  118.64  118.57  118.37  118.22  118.01  118.03
  118.07  118.07  117.98  117.49  117.43  117.21  117.05  116.89  116.61  116.59
  116.43  116.44  116.43  116.39  115.92  115.82  115.62   115.5  115.02  114.77
   114.7  114.64  114.33  114.16  113.82   113.8  113.66  113.35  113.24  113.19
  112.95  112.64  112.63  112.47  112.41  112.41  112.23  112.04 111.532 110.733
 110.453  110.42 111.065 112.038  115.15  115.21  115.26  115.52  115.79  115.74
  116.06  116.09  116.09  116.12  116.53  116.81  117.05  117.29  117.36  117.55
  117.55  117.57   117.9  118.17  118.49  118.61  118.76  118.84  118.94  119.24
  119.55  119.57  119.59  119.59  119.68  119.97  119.94  120.05  120.41   120.5
  120.73  120.63   120.7  120.74  120.84  120.98  121.28  121.41  121.42   121.4
  121.57  121.69  121.49  121.51   121.5  121.85  121.91  122.03
                                                                                
                                                                                
                                                                                
                                                                                
                                                                                
                                                                                
                                                                                
                                                                                
                                                                                
                                                                                
                                                                                
                                                                
       0     .99    5.09   13.84  20.501   27.08   32.91   41.03   43.56   51.62
  58.441    59.1   67.34   77.05   78.71   81.06   91.61   98.49  104.67  109.54
  117.59  117.98  120.17  134.36  135.61  147.74   152.8  159.36  167.53  168.83
  180.33  180.97  181.46  182.23  193.78 200.929  208.88  213.19  228.44  239.45
  243.35  244.31  251.81  258.66  270.99  272.71  275.99   284.6  288.99  290.99
 301.651  314.43  319.59 322.609  330.23  333.18 344.419  348.56  388.08 452.221
 502.083 566.446 627.131 682.236  806.38  813.44  821.41  828.69  834.29  840.61
  850.87  851.38  851.78  852.91   864.3  872.51 880.201 884.499  886.45  894.51
  895.01  895.72  910.61 917.849  928.13  930.57 935.919  938.11  940.55  951.41
  963.14 963.911  964.65  965.88  977.68  982.32 987.369  994.26 1000.39 1007.29
 1011.81 1020.88    1025 1029.23 1032.38 1037.22 1046.35 1055.02 1057.47 1058.96
 1068.48 1072.86 1083.46 1084.87 1085.39 1100.57  1108.2 1115.49
  119.91  119.92  119.83  119.86  119.57  119.38   119.3   119.5  119.45  119.25
  119.07  119.06  118.87  118.65  118.64  118.57  118.37  118.22  118.01  118.03
  118.07  118.07  117.98  117.49  117.43  117.21  117.05  116.89  116.61  116.59
  116.43  116.44  116.43  116.39  115.92  115.82  115.62   115.5  115.02  114.77
   114.7  114.64  114.33  114.16  113.82   113.8  113.66  113.35  113.24  113.19
  112.95  112.64  112.63  112.47  112.41  112.41  112.23  112.04 111.532 110.733
 110.453  110.42 111.065 112.038  115.15  115.21  115.26  115.52  115.79  115.74
  116.06  116.09  116.09  116.12  116.53  116.81  117.05  117.29  117.36  117.55
  117.55  117.57   117.9  118.17  118.49  118.61  118.76  118.84  118.94  119.24
  119.55  119.57  119.59  119.59  119.68  119.97  119.94  120.05  120.41   120.5
  120.73  120.63   120.7  120.74  120.84  120.98  121.28  121.41  121.42   121.4
  121.57  121.69  121.49  121.51   121.5  121.85  121.91  122.03
                                                                                
                                                                                
                                                                                
                                                                                
                                                                                
                                                                                
                                                                                
                                                                                
                                                                                
                                                                                
                                                                                
                                                                
BR Coef=-1 , 0 , 0 ,, 0 ,,,0.8,0,,0,
WSPro=,,,, 1 ,,,, 0 ,,,, 0 ,,,,-1 ,-1 ,-1 , 0 , 0 , 0 , 0 , 0
Culvert=2,6,12,67,0.011,0.4,1,8,1,100.1128,511.1,99.9979,621.82,Culvert #1  , 0 ,43
Culvert Bottom n=0.011
BC Design=,, 0 ,, 0 ,,,,,,
BC Use User HTab Curves=0
BC User HTab FreeFlow(D)= 0

Type RM Length L Ch R = 1 ,14123   ,565.66,626.11,593.8
BEGIN DESCRIPTION:
Surveyed Section
END DESCRIPTION:
XS GIS Cut Line= 6
 2331853.5418531  711428.4095863 2331340.4775001      711381.183
 2331210.7171001     711362.2554 2330992.0240497   711344.844349
 2330787.0902534  711307.0410273 2330731.3800952  711291.1238393
#Sta/Elev= 30
       0  119.33 113.129  117.85  153.61   118.6  217.61  116.14  248.47  113.63
 286.169  113.34  335.39  110.59 437.959  107.17 454.619  107.97  474.45   107.3
 515.215 103.236 603.671 103.019 605.569 101.471 612.392   98.72 627.229  97.206
 641.046 101.332 646.822 102.971 686.576 103.738  687.32  105.62  734.02  105.46
 759.789  107.02 786.691  109.92  805.13  110.18  824.43  112.81 830.429  112.05
  982.88  122.48 1073.46  124.83 1090.16   123.51110.699  124.93 1132.59  123.38
#Mann= 4 ,-1 , 0
       0     .09       0 454.619    .085       0 605.569    .045       0
 641.046     .09       0
#XS Ineff= 2 , 0
       0  595.57     106  651.05       0     106
Permanent Ineff=
       F       F
Bank Sta=605.569,641.046
XS Rating Curve= 0 ,0
Exp/Cntr=0.5,0.3

Type RM Length L Ch R = 1 ,13497   ,621.27,680.51,689.45
XS GIS Cut Line= 5
 2331739.2948383  710863.2849111 2331427.9109565  710867.5504437
 2331263.6879503  710841.9572479  2330860.595117  710820.6295848
 2330525.7508057  710822.7623511
#Sta/Elev= 30
       0  122.43  182.54  119.47  214.58  118.64  354.92  119.45  429.67  116.69
  468.19  113.42  510.03  107.77  534.45  107.26   568.9  102.96  590.69  100.84
  608.43  100.11  645.18  100.45  653.18   99.89  660.98   99.45  669.04   96.29
  672.57   96.29  681.14   99.45  686.87   99.88  698.73  100.69  720.25  100.17
  794.89  103.04  838.89  103.52  905.18  106.05  918.14  105.74  986.81   108.4
 1015.73   110.8 1055.87  112.86 1088.79   116.9 1161.32   121.5 1216.13  123.27
#Mann= 5 ,-1 , 0
       0    .045       0  182.54     .09       0   568.9    .085       0
  653.18    .045       0  686.87     .09       0
Bank Sta=653.18,686.87
XS Rating Curve= 0 ,0
Exp/Cntr=0.3,0.1

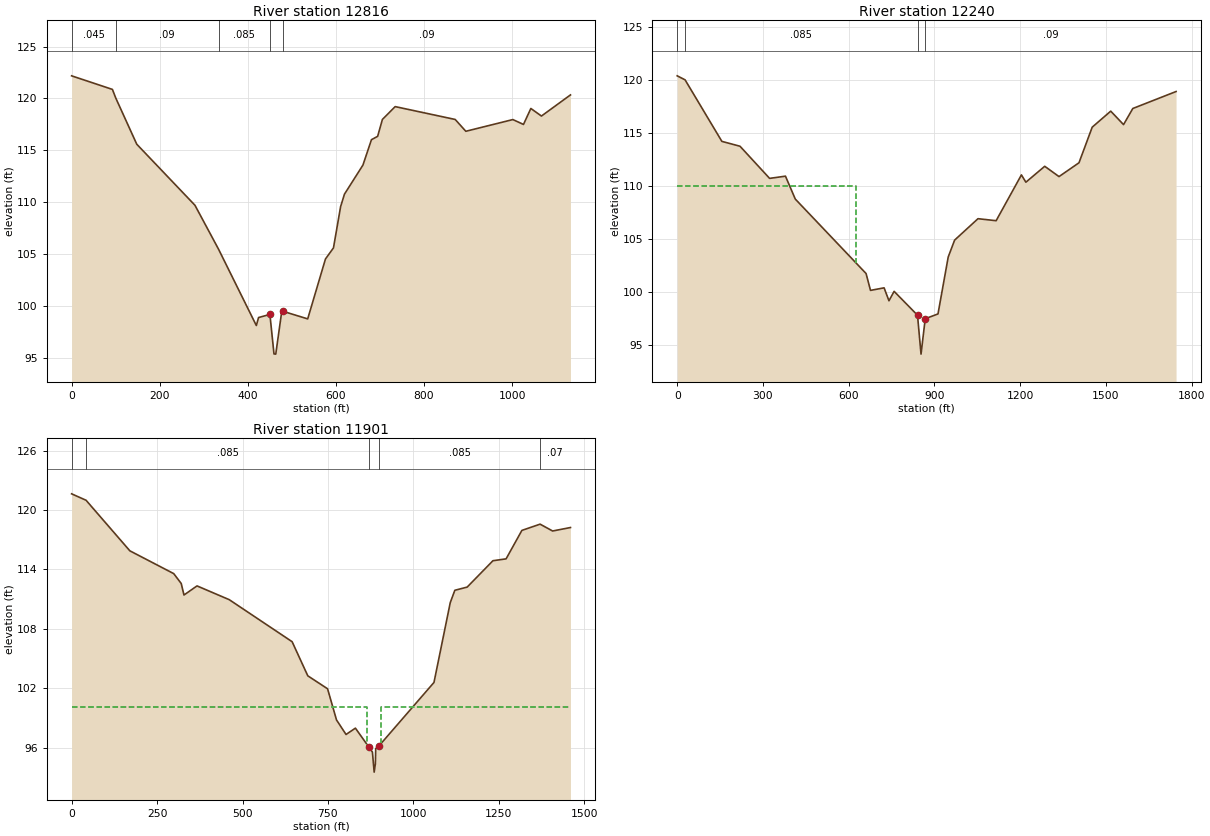
Type RM Length L Ch R = 1 ,12816   ,527.35,576.62,529.34
XS GIS Cut Line= 5
 2331668.9135499  710377.0141915 2331393.7866955  710272.5086422
 2331163.4479336  710208.5256527 2330888.3210791  710099.7545707
 2330613.1942246  709971.7885919
#Sta/Elev= 30
       0  122.18   92.65  120.87  100.24  120.04  147.97  115.58   280.1  109.69
  333.79  105.44  419.42   98.09  424.48   98.86  450.23   99.16   459.5   95.35
  463.52   95.33   476.6   99.29  480.02   99.46  536.05   98.73  576.38  104.51
  594.56  105.58  610.72  109.55  619.46  110.76  661.47  113.57  680.81  116.02
  694.84  116.34  705.63  117.97  734.65  119.21  870.92  117.97  895.08  116.83
 1001.87  117.96 1025.97  117.49 1042.71  119.03 1066.81   118.3 1132.65  120.34
#Mann= 5 ,-1 , 0
       0    .045       0  100.24     .09       0  333.79    .085       0
  450.23    .045       0  480.02     .09       0
Bank Sta=450.23,480.02
XS Rating Curve= 0 ,0
Exp/Cntr=0.3,0.1

Type RM Length L Ch R = 1 ,12240   ,335.29,338.14,310.53
XS GIS Cut Line= 6
 2332244.7604547  709997.3817877 2331922.7127413   709918.469434
 2331630.5237563  709803.3000531 2331327.6709398  709709.4583353
  2330901.117677  709617.7493838  2330568.406132   709523.907666
#Sta/Elev= 30
       0  120.35   27.58  119.97  156.26  114.17  219.79  113.71  323.33  110.68
  378.84  110.89  413.19  108.73  660.85  101.71  676.39  100.12  723.95  100.36
  740.96   99.14  758.98  100.03  840.83   97.78  853.16   94.11  867.89   97.45
  912.53    97.9  948.32  103.27   970.7  104.86 1052.54  106.88 1115.95  106.69
 1204.48  111.01 1220.03  110.32 1286.01  111.82 1335.98  110.85 1405.85  112.15
 1452.15  115.51 1516.97  117.02 1561.78  115.75 1594.23  117.27 1745.55  118.87
#Mann= 4 ,-1 , 0
       0    .045       0   27.58    .085       0  840.83    .045       0
  867.89     .09       0
#XS Ineff= 2 , 0
       0     625     110               0
Permanent Ineff=
       F       F
Bank Sta=840.83,867.89
XS Rating Curve= 0 ,0
Exp/Cntr=0.5,0.3

Type RM Length L Ch R = 1 ,11901   ,64.78,81.08,85.92
BEGIN DESCRIPTION:
Surveyed Section
END DESCRIPTION:
XS GIS Cut Line= 6
 2332330.3379284  709530.0204535 2331918.0030192  709515.8020083
 2331608.0409151  709464.6156058    2331449.9707     709430.9089
 2331114.6647079  709322.7177448 2330901.8305182  709279.6223208
#Sta/Elev= 30
       0  121.63   42.33  120.98  170.42  115.88  298.78  113.58  320.75  112.58
  328.78  111.42  366.93  112.34  461.28  110.95  645.21  106.71  691.03  103.27
  748.92  101.96  775.02   98.82  802.94   97.35 830.355  97.989  870.15   96.06
 880.126  95.578 885.235  93.552 888.738  94.378  889.76  95.927  898.89   96.18
 1060.24   102.6 1107.84  110.65 1121.31   111.9 1157.37  112.22  1232.7  114.88
 1271.26  115.07 1317.45  117.94 1370.69  118.57 1407.37  117.88 1459.58  118.23
#Mann= 5 ,-1 , 0
       0    .045       0   42.33    .085       0  870.15    .045       0
  898.89    .085       0 1370.69     .07       0
#XS Ineff= 2 , 0
       0  865.15  100.13  903.89       0  100.13
Permanent Ineff=
       F       F
Bank Sta=870.15,898.89
XS Rating Curve= 0 ,0
Exp/Cntr=0.5,0.3