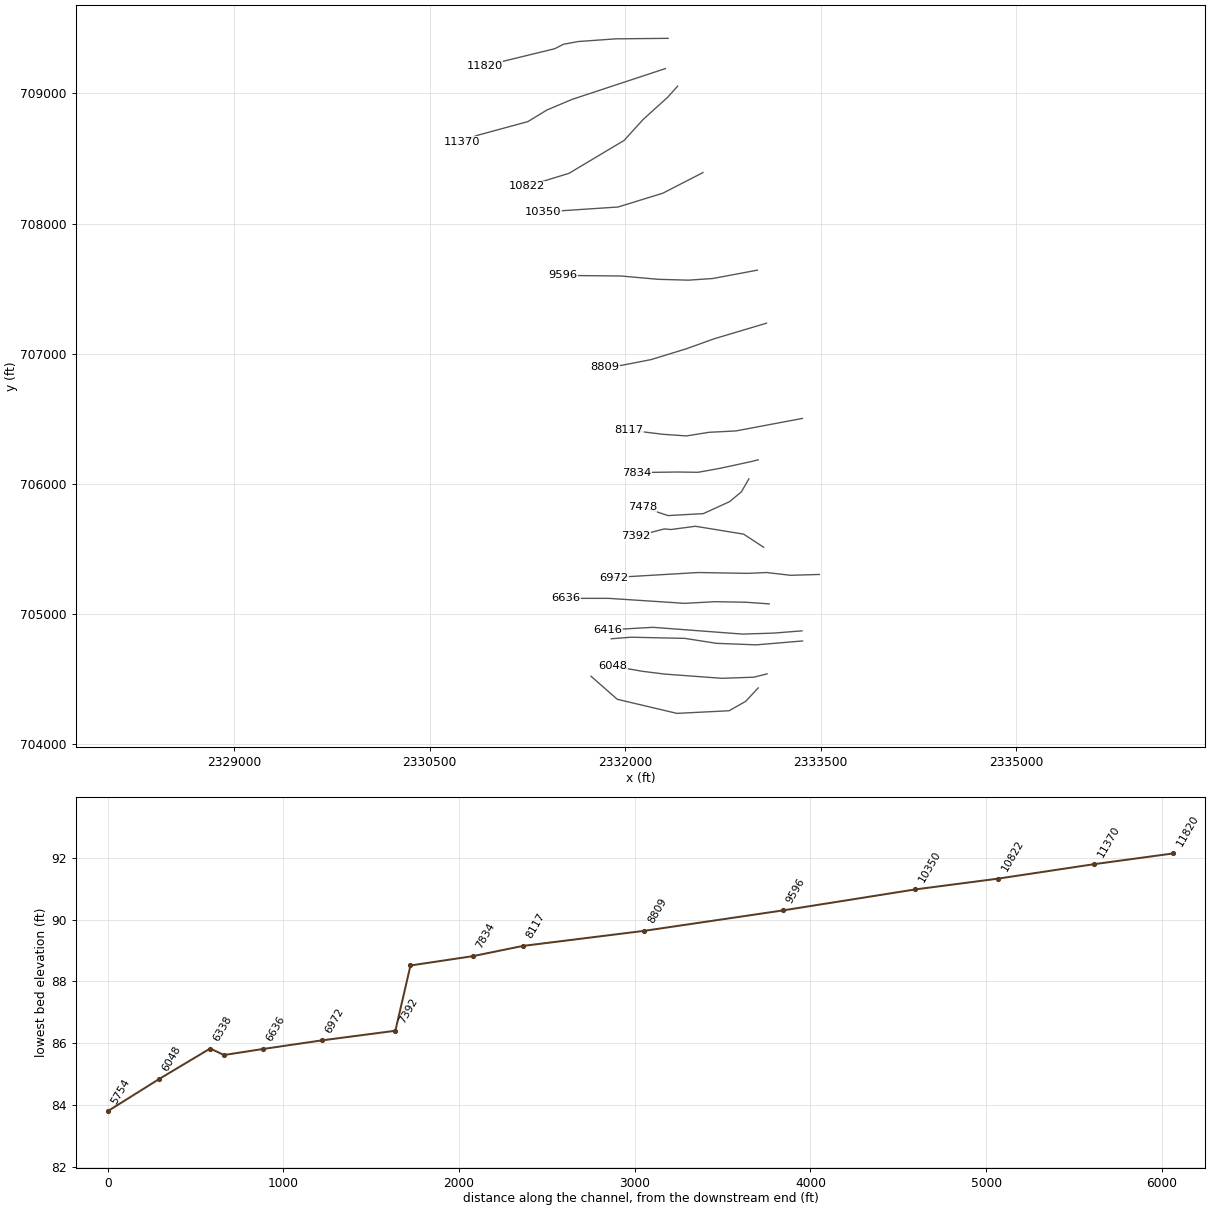
HEC-RAS study dtl_Hominy_Swamp_Trib1.prj: DTL_Hominy_Swamp_Trib1

--- dtl_Hominy_Swamp_Trib1.g01 (geometry) --- (continued)

Type RM Length L Ch R = 2 ,11866   ,,,
BEGIN DESCRIPTION:
Sewer Easement
END DESCRIPTION:
Bridge Culvert--1,0,-1,-1, 0
Deck Dist Width WeirC Skew NumUp NumDn MinLoCord MaxHiCord MaxSubmerge Is_Ogee
26,15,2.6,0, 121, 121, , , 0.95, 0, 1,1,,
       0     1.3   13.37   24.34   26.99   38.46   41.35   44.82   50.78   57.36
   63.27   68.38   70.13   78.17   89.67   99.29  116.96  131.94  136.12  149.66
  156.63  178.69  187.99  200.63  205.69  231.79  232.19  235.21  248.48  251.64
   274.8  279.77     287  296.56  322.04  322.67  322.94  336.06  344.63  353.16
  363.76  364.87  373.54  393.42  395.67     408  422.76  428.23   437.4  442.44
  449.93  457.84  462.87  467.17  472.81  602.56 820.037 856.954 881.663 912.331
 1047.19 1048.58 1050.71 1061.59 1069.75  1076.1 1085.92 1095.86 1106.16 1110.92
 1119.75 1123.96 1131.61 1134.89 1138.35 1147.23 1154.81  1159.3 1159.37 1167.75
 1173.11 1180.05  1191.4 1197.55 1206.44 1211.25 1216.75 1222.87 1225.19 1234.84
 1241.49 1247.74 1254.23 1254.55 1257.39 1263.16 1269.97 1278.48 1286.02  1292.7
 1301.16 1303.37 1316.11 1322.44 1327.79  1333.5 1336.58 1341.85 1351.46 1370.76
 1375.79 1390.13 1404.65 1414.96 1416.03 1424.85  1427.3 1434.97  1439.4 1447.57
 1453.45
  121.43  121.43  121.12  121.02  120.96  120.89  120.84   120.8  120.76  120.67
  120.79  120.83  120.76  120.32  120.29   120.2  120.17  119.97  119.78  119.21
  118.93  118.24  117.39  116.58  116.09  116.15  116.18   116.1  115.57  115.38
  114.87  114.66   114.5  114.05  113.52   113.5  113.49  113.28  112.86  112.43
  111.86   111.8   111.6   111.6  111.58  111.08  110.94  110.76  110.57  110.45
  110.45   110.3  110.26  110.25  109.86  105.87 100.332 100.125 100.538 100.253
  103.65  103.72  104.24  106.13  107.49  107.97   108.7  109.52  110.14  110.58
  111.21  111.16  111.29  111.57  111.55  111.95  112.25  112.26  112.26  112.46
  112.84  112.95  113.07  113.17  113.63  114.04  114.12  114.37  114.53  115.31
  115.47  115.81  116.04  116.06   116.2  116.57  116.96  116.95   117.2  117.31
  117.46  117.55  118.01  117.86  118.07  118.31  118.52  118.32  118.43  118.53
  118.73  118.37  118.29  118.34  118.32  118.52  118.57  118.41  118.45  118.45
  118.46
                                                                                
                                                                                
                                                                                
                                                                                
                                                                                
                                                                                
                                                                                
                                                                                
                                                                                
                                                                                
                                                                                
                                                                                
        
       0     1.3   13.37   24.34   26.99   38.46   41.35   44.82   50.78   57.36
   63.27   68.38   70.13   78.17   89.67   99.29  116.96  131.94  136.12  149.66
  156.63  178.69  187.99  200.63  205.69  231.79  232.19  235.21  248.48  251.64
   274.8  279.77     287  296.56  322.04  322.67  322.94  336.06  344.63  353.16
  363.76  364.87  373.54  393.42  395.67     408  422.76  428.23   437.4  442.44
  449.93  457.84  462.87  467.17  472.81  602.56 820.037 856.954 881.663 912.331
 1047.19 1048.58 1050.71 1061.59 1069.75  1076.1 1085.92 1095.86 1106.16 1110.92
 1119.75 1123.96 1131.61 1134.89 1138.35 1147.23 1154.81  1159.3 1159.37 1167.75
 1173.11 1180.05  1191.4 1197.55 1206.44 1211.25 1216.75 1222.87 1225.19 1234.84
 1241.49 1247.74 1254.23 1254.55 1257.39 1263.16 1269.97 1278.48 1286.02  1292.7
 1301.16 1303.37 1316.11 1322.44 1327.79  1333.5 1336.58 1341.85 1351.46 1370.76
 1375.79 1390.13 1404.65 1414.96 1416.03 1424.85  1427.3 1434.97  1439.4 1447.57
 1453.45
  121.43  121.43  121.12  121.02  120.96  120.89  120.84   120.8  120.76  120.67
  120.79  120.83  120.76  120.32  120.29   120.2  120.17  119.97  119.78  119.21
  118.93  118.24  117.39  116.58  116.09  116.15  116.18   116.1  115.57  115.38
  114.87  114.66   114.5  114.05  113.52   113.5  113.49  113.28  112.86  112.43
  111.86   111.8   111.6   111.6  111.58  111.08  110.94  110.76  110.57  110.45
  110.45   110.3  110.26  110.25  109.86  105.87 100.332 100.125 100.538 100.253
  103.65  103.72  104.24  106.13  107.49  107.97   108.7  109.52  110.14  110.58
  111.21  111.16  111.29  111.57  111.55  111.95  112.25  112.26  112.26  112.46
  112.84  112.95  113.07  113.17  113.63  114.04  114.12  114.37  114.53  115.31
  115.47  115.81  116.04  116.06   116.2  116.57  116.96  116.95   117.2  117.31
  117.46  117.55  118.01  117.86  118.07  118.31  118.52  118.32  118.43  118.53
  118.73  118.37  118.29  118.34  118.32  118.52  118.57  118.41  118.45  118.45
  118.46
                                                                                
                                                                                
                                                                                
                                                                                
                                                                                
                                                                                
                                                                                
                                                                                
                                                                                
                                                                                
                                                                                
                                                                                
        
BR Coef=-1 , 0 , 0 ,, 0 ,,,0.8,0,,0,
WSPro=,,,, 1 ,,,, 0 ,,,, 0 ,,,,-1 ,-1 ,-1 , 0 , 0 , 0 , 0 , 0
Culvert=1,3,,24,0.011,0.2,1,1,3,94.3713,873.62,94.4543,846.4,Culvert #1  , 0 ,25
Culvert Bottom n=0.011
Culvert=1,3,,24,0.011,0.2,1,1,3,94.8652,896.62,94.8156,869.4,Culvert #2  , 0 ,18
Culvert Bottom n=0.011
BC Design=,, 0 ,, 0 ,,,,,,
BC Use User HTab Curves=0
BC User HTab FreeFlow(D)= 0

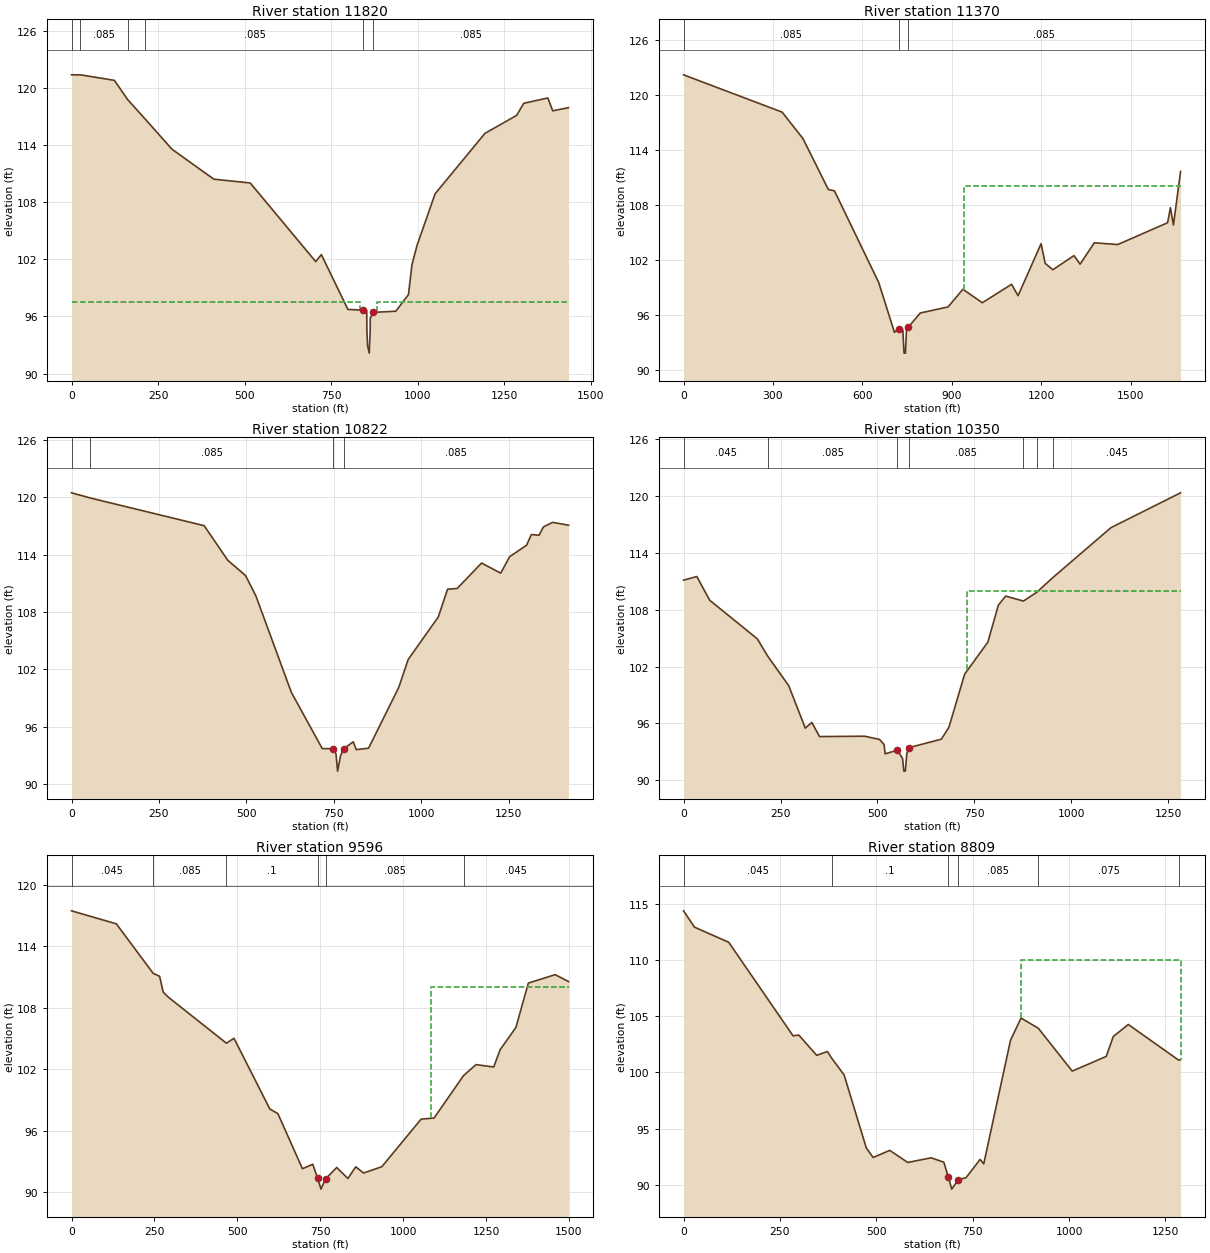
Type RM Length L Ch R = 1 ,11820   ,428.48,450.86,423.45
BEGIN DESCRIPTION:
Surveyed Section
END DESCRIPTION:
XS GIS Cut Line= 6
 2332329.9576935  709423.6225833 2331929.0575015  709419.7113619
 2331641.5827297  709399.1774496    2331527.1348     709378.3622
    2331459.9323     709343.9964 2330921.8781563  709212.7968604
#Sta/Elev= 30
       0  121.38   25.84  121.38  123.91   120.8   162.1  118.78  213.64   116.7
  290.17  113.57  411.09  110.42  516.24  110.02  705.46  101.76  721.75   102.5
   798.4   96.74  843.21   96.66 852.834  96.604 853.265  94.507 855.275  92.922
 860.013  92.148 862.741  94.467 863.028  95.826  871.88   96.43  936.77   96.55
  973.33   98.29  983.43  101.43  998.25  103.48 1050.41  108.89 1194.29  115.23
  1285.9  117.12 1306.38  118.39 1376.06  118.95 1390.05   117.6 1435.75  117.93
#Mann= 6 ,-1 , 0
       0    .045       0   25.84    .085       0   162.1    .045       0
  213.64    .085       0  843.21    .045       0  871.88    .085       0
#XS Ineff= 2 , 0
       0  833.21    97.5  881.88       0    97.5
Permanent Ineff=
       F       F
Bank Sta=843.21,871.88
XS Rating Curve= 0 ,0
Exp/Cntr=0.5,0.3

Type RM Length L Ch R = 1 ,11370   ,470.06,547.99,497.54
XS GIS Cut Line= 6
 2332308.7434441709191.1961210222331592.13396269708954.459060177
2331400.18499443708873.4139402662331253.02411874708783.837755084
2330860.59511703708677.1994393912330745.83532898708627.771130174
#Sta/Elev= 30
       0  122.17  330.72   118.1  400.71  115.21  485.74  109.66  506.33  109.51
  654.88    99.5  707.57   94.07   722.1   94.48  735.69    94.3  739.84    91.8
   744.5    91.8   748.1   94.44  753.72   94.61  794.11   96.18  887.47   96.84
  937.18   98.77 1002.39    97.3 1100.55   99.31 1122.39   98.07 1199.56  103.74
 1213.51  101.59 1239.21   100.9 1309.97  102.44 1330.53  101.51 1378.19  103.84
    1457  103.65 1624.04  106.03 1633.55  107.67 1643.71  105.78 1667.57  111.63
#Mann= 3 ,-1 , 0
       0    .085       0   722.1    .045       0  753.72    .085       0
#XS Ineff= 2 , 0
       0                     940       0     110
Permanent Ineff=
       F       F
Bank Sta=722.1,753.72
XS Rating Curve= 0 ,0
Exp/Cntr=0.3,0.1

Type RM Length L Ch R = 1 ,10822   ,496.39,471.55,428.79
XS GIS Cut Line= 6
2332403.11297081709056.433254018 2332326.7098514708971.214390039
2332138.64063433708800.7766620812331991.71155849708639.154678673
2331568.55582008708386.4366682322331242.37327173708286.524896666
#Sta/Elev= 30
       0  120.46   54.13 119.917   379.2  117.02  446.88  113.39  497.54   111.8
  526.91  109.68  628.48   99.57  716.69   93.69  748.87   93.67  756.09   93.12
  760.57   91.33     769   92.93  778.26   93.67  805.22    94.4  813.99   93.58
  849.16   93.73  935.51   100.1  962.29  103.01 1048.47  107.47  1074.9  110.37
 1102.36  110.45  1172.2  113.11 1226.88  112.05 1252.44  113.78 1300.68  114.97
 1314.36  116.09 1336.47  116.02 1348.88  116.89 1375.29  117.37 1420.71  117.07
#Mann= 4 ,-1 , 0
       0    .045       0   54.13    .085       0  748.87    .045       0
  778.26    .085       0
Bank Sta=748.87,778.26
XS Rating Curve= 0 ,0
Exp/Cntr=0.3,0.1

Type RM Length L Ch R = 1 ,10350   ,727.31,753.57,627.71
XS GIS Cut Line= 4
2332597.05935097708392.3138312552332288.50829165708233.630429342
2331944.69425423708127.8414947542331368.73227695708089.639935046
#Sta/Elev= 30
       0   111.1    34.3  111.48   67.27  108.99  190.37  104.91  217.11103.0844
  271.09   99.99  313.85   95.51  330.74   96.11  350.65   94.62  466.48   94.66
  505.25   94.32  517.06   93.78   519.8    92.8  551.44   93.19  564.71    92.3
  567.91   90.98  571.75   90.98  575.84   92.87  580.16   93.44  664.85   94.35
  684.27   95.61  724.85   101.2   784.6  104.57  811.73  108.47   830.4  109.42
   876.4108.8985  910.94109.8309  953.18111.4047 1102.02  116.63 1281.48   120.3
#Mann= 7 ,-1 , 0
       0    .045       0  217.11    .085       0  551.44    .045       0
  580.16    .085       0   876.4    .045       0  910.94    .085       0
  953.18    .045       0
#XS Ineff= 2 , 0
       0                     732       0     110
Permanent Ineff=
       F       F
Bank Sta=551.44,580.16
XS Rating Curve= 0 ,0
Exp/Cntr=0.3,0.1

Type RM Length L Ch R = 1 ,9596    ,650.48,787.29,687.24
XS GIS Cut Line= 6
  2333014.689094  707642.8077772 2332673.4464838  707578.8247878
 2332485.7630482  707566.0281899 2332255.4242863  707572.4264888
 2331967.5008339  707598.0196846 2331523.8854406  707602.2852172
#Sta/Elev= 30
       0  117.46  135.21  116.19  246.24  111.36  265.63  111.07  276.54  109.52
   292.4  109.02  467.15  104.54  489.97  105.02     598   98.12  622.23   97.67
  696.37   92.29   727.4   92.73   741.9   91.39  752.28    90.3  765.91   91.29
  799.65   92.41  833.47   91.34  857.17   92.48  880.67   91.87  935.82   92.49
 1054.17   97.13  1093.3   97.24 1182.33  101.39 1219.79  102.45 1273.24  102.22
 1292.32   103.9 1339.91  106.07 1377.63  110.41 1458.47  111.23  1498.7  110.56
#Mann= 6 ,-1 , 0
       0    .045       0  246.24    .085       0  467.15      .1       0
   741.9    .045       0  765.91    .085       0 1182.33    .045       0
#XS Ineff= 2 , 0
       0                 1084.72       0     110
Permanent Ineff=
       F       F
Bank Sta=741.9,765.91
XS Rating Curve= 0 ,0
Exp/Cntr=0.3,0.1

Type RM Length L Ch R = 1 ,8809    ,679.36,692.12,659.89
XS GIS Cut Line= 6
 2333085.0703824  707235.4494112 2332684.1103154  707116.0144977
  2332470.833684  707039.2349103 2332199.9723621  706956.0570241
 2331971.7663665  706911.2689315 2331843.8003877  706900.6050999
#Sta/Elev= 30
       0  114.35   28.41   112.9  117.14  111.56  284.14  103.25  298.97  103.32
  345.47  101.52  373.19  101.86  383.85  101.29  416.52   99.78  474.01   93.31
  491.72   92.45  534.97   93.08  581.54   92.01  642.47   92.42  675.25   92.03
  686.85   90.72  695.67   89.64  713.03   90.48  732.67   90.65  769.53   92.28
  778.74   91.88  848.28  102.86  875.55  104.83  920.49  103.92  1008.3  100.12
 1096.42  101.42 1114.87  103.19 1153.75  104.26 1284.48  101.09 1289.38  101.13
#Mann= 6 ,-1 , 0
       0    .045       0  383.85      .1       0  686.85    .045       0
  713.03    .085       0  920.49    .075       0 1284.48    .085       0
#XS Ineff= 2 , 0
       0                  875.55       0     110
Permanent Ineff=
       F       F
Bank Sta=686.85,713.03
XS Rating Curve= 0 ,0
Exp/Cntr=0.3,0.1

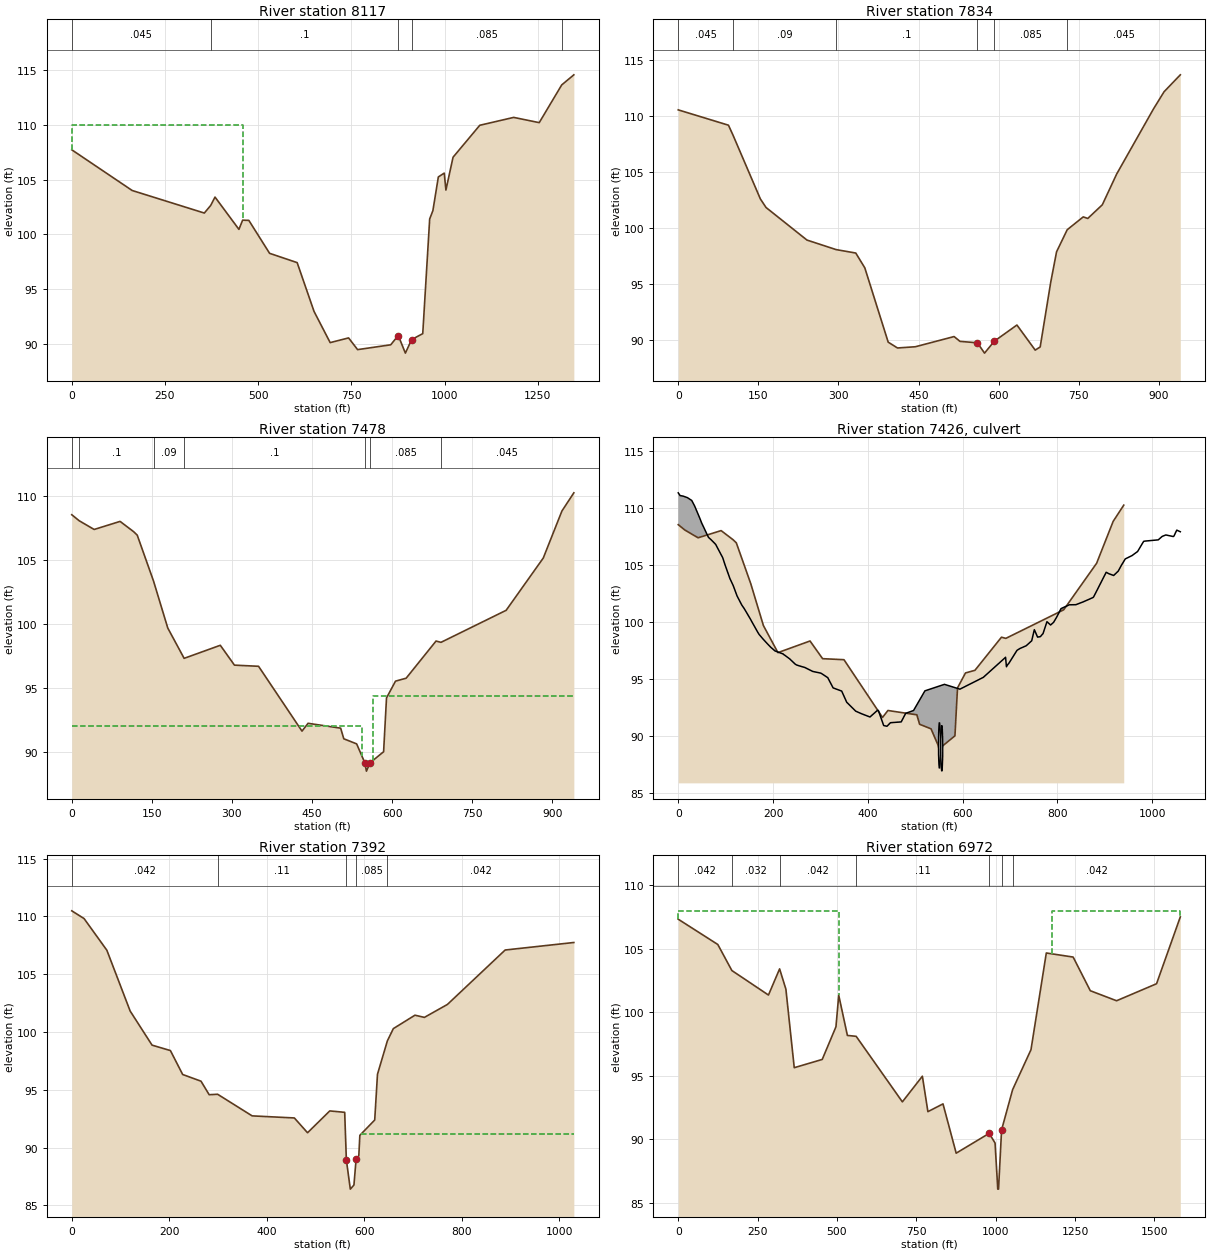
Type RM Length L Ch R = 1 ,8117    ,295.17,283.43,283.73
XS GIS Cut Line= 6
 2333360.1972369  706503.9105656 2332850.4660878  706407.9360815
 2332643.5877554  706397.2722499  2332470.833684  706369.5462878
  2332287.415781  706382.3428857 2332027.2182907  706414.3343804
#Sta/Elev= 30
       0  107.73   162.1  104.01  355.62  101.95  372.84  102.65  384.28  103.41
  448.45  100.46  458.42   101.3  475.05  101.28  530.74   98.27  604.68   97.42
     650   92.96  693.26   90.11  742.67   90.54  766.84   89.47  855.66   89.91
  875.94   90.76  895.01   89.15  911.77   90.39  941.63   90.93  960.22  101.41
  968.84  102.17  983.48  105.25  999.33   105.6 1003.76  104.05 1022.92  107.05
 1094.65  109.97 1185.58  110.69 1254.08  110.21 1314.51  113.66 1346.98  114.58
#Mann= 5 ,-1 , 0
       0    .045       0  372.84      .1       0  875.94    .045       0
  911.77    .085       0 1314.51    .075       0
#XS Ineff= 2 , 0
       0  458.42     110               0
Permanent Ineff=
       F       F
Bank Sta=875.94,911.77
XS Rating Curve= 0 ,0
Exp/Cntr=0.3,0.1

Type RM Length L Ch R = 1 ,7834    ,328.16,355.76,361.16
XS GIS Cut Line= 6
  2333021.087393  706186.1283848 2332972.0337677  706173.3317869
 2332724.6328753  706120.0126291 2332560.4098691  706090.1539007
 2332402.5851619   706092.286667 2332091.2012801  706088.0211344
#Sta/Elev= 30
       0  110.55   94.04  109.18  102.55  108.29  153.72   102.6  164.36  101.83
  240.97   98.92  295.42   98.07  332.39   97.76  349.28   96.44  393.06    89.8
  410.45   89.28  443.94   89.39  516.41    90.3  527.52   89.87  560.11   89.74
  573.43   88.82   591.6   89.88  634.08   91.33   668.3   89.09  677.61   89.37
  697.45   95.18  708.27   97.87  728.17   99.84  758.21  100.99  766.71  100.85
  793.91  102.07  820.82  104.82  889.67  110.63  909.58  112.17  939.94  113.68
#Mann= 6 ,-1 , 0
       0    .045       0  102.55     .09       0  295.42      .1       0
  560.11    .045       0   591.6    .085       0  728.17    .045       0
Bank Sta=560.11,591.6
XS Rating Curve= 0 ,0
Exp/Cntr=0.5,0.3

Type RM Length L Ch R = 1 ,7478    ,126.32,85.97,73.9
BEGIN DESCRIPTION:
Surveyed Section
END DESCRIPTION:
XS GIS Cut Line= 6
 2332950.0943388  706039.9112483 2332892.0964813  705939.7331307
  2332800.705918  705864.1601649 2332600.3496829  705772.7696015
 2332328.9022466  705757.5931219     2332130.539   705823.714204
#Sta/Elev= 30
       0  108.53   13.92  108.06   41.94  107.38    90.5  108.01  115.76  107.21
  122.57  106.94  153.08  103.36  179.77   99.69  210.43   97.32  278.17   98.34
  304.67   96.79  349.81    96.7  431.16   91.64  442.55   92.25  503.59   91.87
 509.436  91.041 533.507  90.644  548.73   89.18 551.843  88.517  558.73   89.17
     584  90.031  589.44   94.23  606.25   95.54   626.2   95.77  682.17   98.67
  691.47   98.57   813.5  101.07  883.02  105.15  917.93  108.82  940.27  110.24
#Mann= 7 ,-1 , 0
       0    .045       0   13.92      .1       0  153.08     .09       0
  210.43      .1       0  548.73    .045       0  558.73    .085       0
  691.47    .045       0
#XS Ineff= 2 , 0
       0  543.73   92.02  563.73       0    94.4
Permanent Ineff=
       F       F
Bank Sta=548.73,558.73
XS Rating Curve= 0 ,0
Exp/Cntr=0.5,0.3

Type RM Length L Ch R = 2 ,7426    ,,,
BEGIN DESCRIPTION:
Golf cart path
END DESCRIPTION:
Bridge Culvert--1,0,-1,-1, 0
Deck Dist Width WeirC Skew NumUp NumDn MinLoCord MaxHiCord MaxSubmerge Is_Ogee
45,10,2.6,0, 110, 110, , , 0.95, 0, 1,1,,
       0    3.93   10.56   19.28   28.53   34.48   45.77   49.22    63.3   64.28
   70.12   79.08   80.67   93.96    98.2  109.06  111.09  116.07   124.1  133.95
  139.36  152.33  154.77  167.89  170.45  170.98  178.54  187.19  195.24  204.21
  219.62  221.33  222.21  224.58  235.28  246.65  249.61  254.65  267.04  283.95
  284.09   301.2  315.51  326.89  344.99  355.48  355.63  374.62  386.66  404.63
  420.36  422.42   433.6  440.61  445.98  447.87  470.55  479.98  496.62 520.598
 561.818 594.455 643.834 690.882  692.63  695.65  697.42  714.95  721.11  734.34
  746.02  751.52  758.41  758.89  764.24  769.92  778.17  785.82  792.14  798.69
  807.79   809.6  825.41  839.24  854.25  854.26  854.29  867.98  875.39  876.47
  879.75  903.18  908.99  918.95  928.57  934.88  943.47  957.63  969.52  978.66
  982.32  984.83 1013.13 1021.32 1029.04 1044.78 1046.32 1049.78 1052.16 1059.63
  111.32  111.08  111.03   110.9  110.65  110.18  109.07   108.7  107.46   107.4
  107.18   106.8  106.67  105.63  105.08  103.81  103.63  103.19  102.29   101.5
  101.17  100.26  100.07    99.1   98.93    98.9   98.53   98.14   97.79   97.47
   97.23   97.21   97.16    97.1   96.77   96.32   96.24   96.17   96.02   95.67
   95.67   95.52   95.13   94.23   93.95   92.98   92.97   92.19   91.97   91.68
   92.26   92.25   90.93   90.87    91.1   91.18   91.25      92   92.25  93.972
  94.541  94.119  95.153  96.912   96.08   96.29   96.36   97.52   97.68   97.92
   98.36   99.33   98.68   98.68   98.72   98.99  100.03   99.74   99.97  100.43
  101.17  101.21  101.51  101.52  101.76  101.76  101.76  102.01  102.15  102.19
  102.45  104.36  104.23  104.08  104.46  104.94  105.53  105.82  106.18  106.82
  107.07  107.09   107.2   107.5  107.63  107.49  107.54  107.85  108.05  107.91
                                                                                
                                                                                
                                                                                
                                                                                
                                                                                
                                                                                
                                                                                
                                                                                
                                                                                
                                                                                
                                                                                
       0    3.93   10.56   19.28   28.53   34.48   45.77   49.22    63.3   64.28
   70.12   79.08   80.67   93.96    98.2  109.06  111.09  116.07   124.1  133.95
  139.36  152.33  154.77  167.89  170.45  170.98  178.54  187.19  195.24  204.21
  219.62  221.33  222.21  224.58  235.28  246.65  249.61  254.65  267.04  283.95
  284.09   301.2  315.51  326.89  344.99  355.48  355.63  374.62  386.66  404.63
  420.36  422.42   433.6  440.61  445.98  447.87  470.55  479.98  496.62 520.598
 561.818 594.455 643.834 690.882  692.63  695.65  697.42  714.95  721.11  734.34
  746.02  751.52  758.41  758.89  764.24  769.92  778.17  785.82  792.14  798.69
  807.79   809.6  825.41  839.24  854.25  854.26  854.29  867.98  875.39  876.47
  879.75  903.18  908.99  918.95  928.57  934.88  943.47  957.63  969.52  978.66
  982.32  984.83 1013.13 1021.32 1029.04 1044.78 1046.32 1049.78 1052.16 1059.63
  111.32  111.08  111.03   110.9  110.65  110.18  109.07   108.7  107.46   107.4
  107.18   106.8  106.67  105.63  105.08  103.81  103.63  103.19  102.29   101.5
  101.17  100.26  100.07    99.1   98.93    98.9   98.53   98.14   97.79   97.47
   97.23   97.21   97.16    97.1   96.77   96.32   96.24   96.17   96.02   95.67
   95.67   95.52   95.13   94.23   93.95   92.98   92.97   92.19   91.97   91.68
   92.26   92.25   90.93   90.87    91.1   91.18   91.25      92   92.25  93.972
  94.541  94.119  95.153  96.912   96.08   96.29   96.36   97.52   97.68   97.92
   98.36   99.33   98.68   98.68   98.72   98.99  100.03   99.74   99.97  100.43
  101.17  101.21  101.51  101.52  101.76  101.76  101.76  102.01  102.15  102.19
  102.45  104.36  104.23  104.08  104.46  104.94  105.53  105.82  106.18  106.82
  107.07  107.09   107.2   107.5  107.63  107.49  107.54  107.85  108.05  107.91
                                                                                
                                                                                
                                                                                
                                                                                
                                                                                
                                                                                
                                                                                
                                                                                
                                                                                
                                                                                
                                                                                
BR Coef=-1 , 0 , 0 ,, 0 ,,,0.8,0,,0,
WSPro=,,,, 1 ,,,, 0 ,,,, 0 ,,,,-1 ,-1 ,-1 , 0 , 0 , 0 , 0 , 0
Culvert=1,4,,40,0.024,0.9,1,2,3,87.1902,551.24,87.3251,570.6,Culvert #1  , 0 ,30
Culvert Bottom n=0.024
Culvert=1,4,,40,0.024,0.9,1,2,3,86.9382,556.24,87.3236,575.6,Culvert #2  , 0 ,30
Culvert Bottom n=0.024
BC Design=,, 0 ,, 0 ,,,,,,
BC Use User HTab Curves=0
BC User HTab FreeFlow(D)= 0

Type RM Length L Ch R = 1 ,7392    ,340.85,419.53,366.18
BEGIN DESCRIPTION:
Surveyed Section
END DESCRIPTION:
XS GIS Cut Line= 6
 2333063.5937518  705514.0576449 2332909.3453978  705615.2041066
    2332539.5324     705675.5799 2332350.7232277  705650.4808213
 2332301.6577703  705655.3182608 2332080.5176802    705597.96005
#Sta/Elev= 30
       0  110.48   25.23  109.81   71.97  107.07  119.73  101.81  164.64   98.86
  202.26   98.39  227.41   96.32  265.01   95.74  281.76   94.57  299.08   94.61
   369.8   92.74  456.41   92.56  483.46   91.28  529.07  93.169 559.647  93.046
 563.044  88.939 571.177  86.402  578.59  86.755 583.017  88.975 588.576  89.285
 590.738  91.056 621.212  92.382  626.87   96.34  647.16   99.23  659.42  100.29
  703.72  101.45  723.06  101.26  770.26  102.38  888.69  107.09 1029.52  107.74
#Mann= 5 ,-1 , 0
       0    .042       0  299.08     .11       0 563.044    .045       0
 583.017    .085       0  647.16    .042       0
#XS Ineff= 2 , 0
       0   560.6    91.8  593.02       0   91.17
Permanent Ineff=
       F       F
Bank Sta=563.044,583.017
XS Rating Curve= 0 ,0
Exp/Cntr=0.5,0.3

Type RM Length L Ch R = 1 ,6972    ,228.81,335.83,238.29
XS GIS Cut Line= 6
2333490.63469137705305.3845134382333270.62105164705298.897598282
2333085.07038239705320.225261405  2332940.042273705313.826962456
2332560.40986912705320.2252614052331912.04890974705281.835467741
#Sta/Elev= 30
       0  107.34  124.65  105.35  168.89   103.3  284.17  101.37  319.28  103.43
   339.1  101.83  365.42   95.65  453.52    96.3  496.76   98.87  505.54  101.35
  532.79   98.19  560.43   98.12  705.97   92.96  768.97   94.98  786.35   92.19
  833.93    92.8  875.43   88.92  979.33   90.48   997.9   89.72 1006.42   86.09
 1008.83   86.09 1018.42   90.75 1053.18   93.92 1111.07   97.07  1159.3  104.68
 1243.83  104.36 1297.85  101.71 1380.63  100.92 1506.51  102.26 1581.35  107.52
#Mann= 7 ,-1 , 0
       0    .042       0  168.89    .032       0  319.28    .042       0
  560.43     .11       0  979.33    .045       0 1018.42     .11       0
 1053.18    .042       0
#XS Ineff= 2 , 0
       0  505.54     108    1176       0     108
Permanent Ineff=
       F       F
Bank Sta=979.33,1018.42
XS Rating Curve= 0 ,0
Exp/Cntr=0.3,0.1

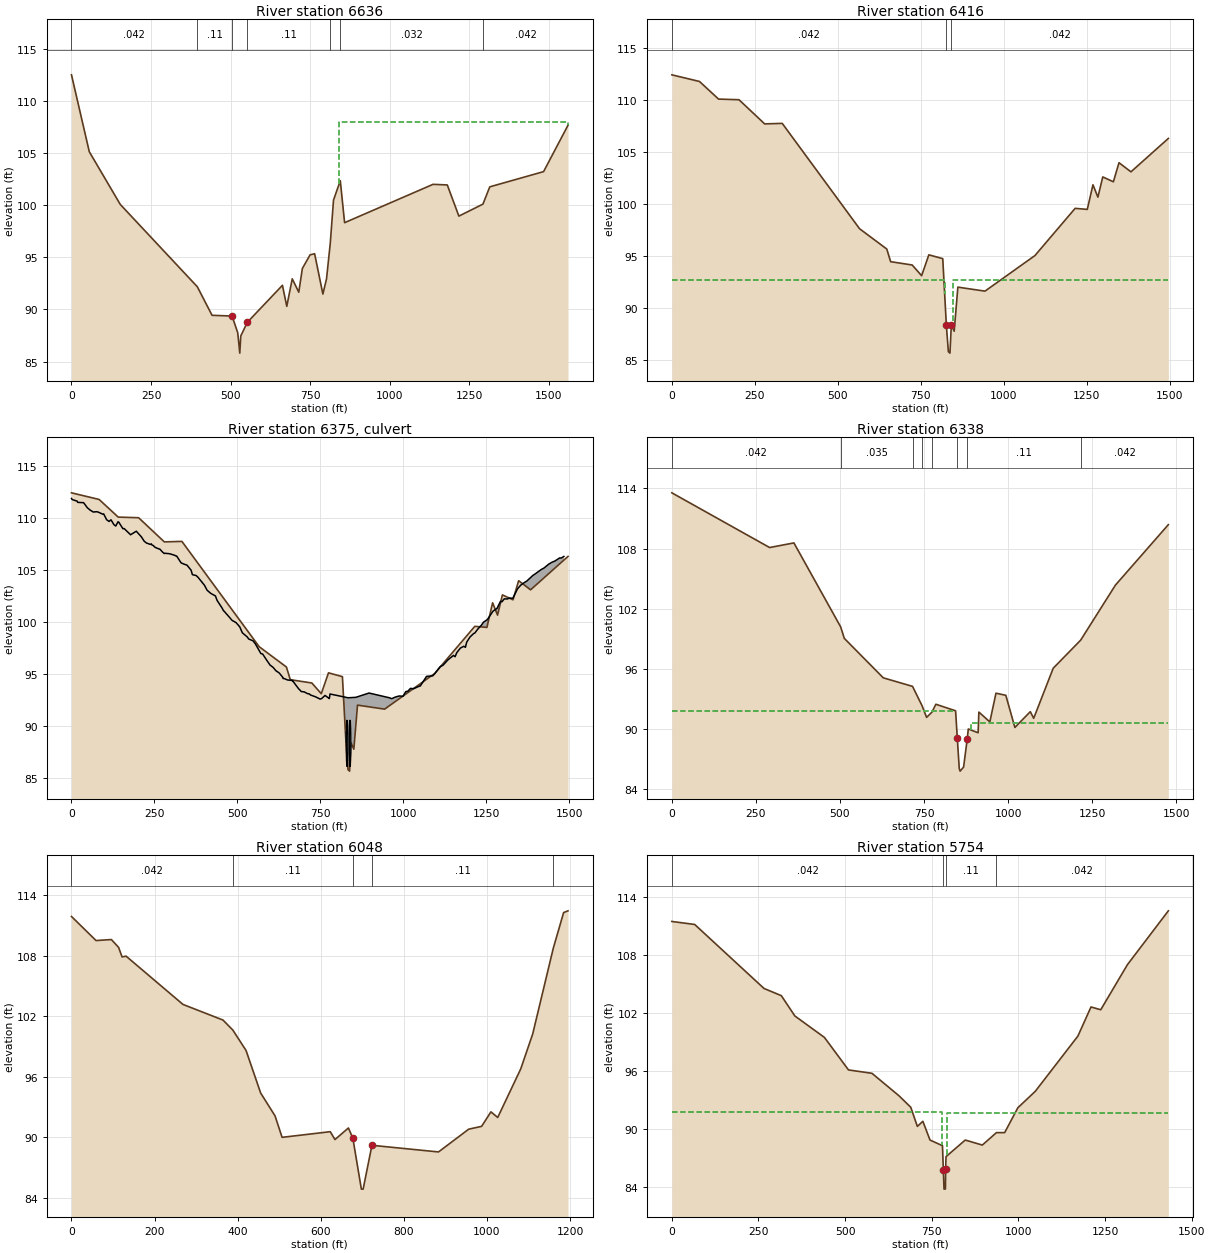
Type RM Length L Ch R = 1 ,6636    ,236.34,220.02,206.39
XS GIS Cut Line= 6
2333105.58231731705079.2809342152332927.24567516705092.019265801
2332690.50861426705096.2847984282332458.03708607 705083.48820056
 2331871.5263498705121.877994195 2331547.5048825705121.626054138
#Sta/Elev= 30
       0  112.52   55.93  105.14  153.33  100.08  395.43   92.18  441.72   89.44
   504.6   89.37  522.37   87.77  528.87   85.81  531.98   87.46  552.63   88.77
  662.85   92.32  676.54    90.3  693.67   92.94  714.23   91.66  725.45   93.93
  749.65   95.24  764.01   95.35  789.96   91.48  801.38   92.93  813.16   96.35
  823.39   100.5  844.68  102.36   858.2   98.33 1136.15  102.01 1180.95  101.95
 1217.33   98.96 1292.92  100.11 1314.44  101.77  1483.5  103.23 1560.23  107.68
#Mann= 7 ,-1 , 0
       0    .042       0  395.43     .11       0   504.6    .045       0
  552.63     .11       0  813.16    .042       0  844.68    .032       0
 1292.92    .042       0
#XS Ineff= 2 , 0
       0                  840.62       0     108
Permanent Ineff=
       F       F
Bank Sta=504.6,552.63
XS Rating Curve= 0 ,0
Exp/Cntr=0.5,0.3

Type RM Length L Ch R = 1 ,6416    ,84.86,78.72,72.81
BEGIN DESCRIPTION:
Surveyed Section
END DESCRIPTION:
XS GIS Cut Line= 6
2333357.31002006704872.2025786792333140.77192192704854.956181467
2332901.23862751704847.2911160592332212.83323398704899.432404712
2331925.09283012704882.6141546522331865.33985522704874.986115322
#Sta/Elev= 30
       0  112.44   83.29   111.8  140.86   110.1  202.29  110.04  279.82  107.71
   332.7  107.76  565.58   97.61  647.71   95.65  659.37   94.43  724.33   94.11
  752.67   93.08 774.471   95.09 816.412  94.722  827.17   88.33 833.295  85.756
 838.043  85.616 842.263  88.355 850.836  87.728 861.915  91.977  943.61   91.59
 1094.19   95.02 1215.33   99.57 1251.91   99.47 1269.03  101.84 1283.94  100.65
 1298.55   102.6 1330.53  102.13 1347.49  103.97 1383.49  103.09 1496.22  106.31
#Mann= 3 ,-1 , 0
       0    .042       0  827.17    .045       0 842.263    .042       0
#XS Ineff= 2 , 0
       0  822.17   92.69  847.26       0   92.69
Permanent Ineff=
       F       F
Bank Sta=827.17,842.263
XS Rating Curve= 0 ,0
Exp/Cntr=0.5,0.3

Type RM Length L Ch R = 2 ,6375    ,,,
BEGIN DESCRIPTION:
Wedgewood Drive
END DESCRIPTION:
Bridge Culvert--1,0,-1,-1, 0
Deck Dist Width WeirC Skew NumUp NumDn MinLoCord MaxHiCord MaxSubmerge Is_Ogee
32,20,2.6,0, 174, 171, , , 0.98, 0, 1,1,,
       0    1.83     4.1   16.98   18.81   24.44    36.5   47.78   56.42   65.77
   75.78   80.81   94.44   96.91  105.84  113.17  119.04   127.9   133.4   134.2
  140.27   142.7  154.96  158.64  176.26  176.84  177.02  177.97  194.91  195.27
   210.5  219.47  226.04  237.54  240.49  242.41  246.41  251.74  261.01  266.38
  274.37  279.45  281.76  291.39  293.11  297.67  310.87  315.04  316.88  330.22
  338.81  348.05  360.48  364.31  375.49  376.89  381.32  383.29  400.49  408.68
  419.59  433.73  438.78  454.27  458.16   459.4  473.23  477.15  483.72  495.97
  507.06  514.89  530.31  533.62  547.36  552.16  553.29  570.67   576.1  585.08
  588.87  598.31  607.16   616.1  625.79  635.67  637.86  639.94  651.15  664.43
  665.19  665.85  683.54  690.53  692.74   700.9  711.62  716.58  720.26  734.61
  749.23  753.77  764.04  776.07  776.52  777.07 778.994 833.262 856.747 896.686
  957.56   964.9  975.52  983.16  983.88  988.61  999.01 1007.43 1013.64 1021.49
 1030.88 1049.19 1051.23  1052.3  1069.9 1085.51  1088.7 1094.99 1095.72 1111.25
 1119.43 1134.72 1151.31  1155.9 1160.94 1172.08 1182.42 1187.05 1191.12 1197.12
 1200.64 1211.47 1215.48 1223.99 1235.89 1238.67  1241.3 1253.08 1266.85 1268.36
 1270.14 1282.38 1292.89 1297.13 1304.18 1313.35 1319.09 1326.85 1329.97 1344.42
 1347.19 1353.72 1366.42 1371.88 1389.57 1397.47 1415.09 1423.72 1437.92 1446.62
 1456.92 1471.27 1475.57 1483.85
   111.9   111.8  111.77  111.64  111.52  111.51  111.49     111  110.77  110.59
  110.62  110.58  110.38  110.41  109.85  109.68  109.84  109.37  109.24  109.29
  109.65   109.6  108.98     109  108.45  108.42  108.43   108.4  108.74  108.74
   108.2  107.76   107.6  107.47  107.52  107.41  107.36  107.19  107.06  107.01
  106.73  106.59  106.61  106.59  106.58  106.55  106.42  106.35  106.35  105.69
  105.57  105.47  104.98  104.55  104.47  104.43   104.3  104.22  103.54  103.05
  102.75   102.5  102.07  101.31  101.07  101.05  100.55   100.4  100.15   99.93
   99.52   98.95   98.53   98.36   98.17   97.96   97.93   96.95    96.9   96.46
   96.28   95.84   95.63   95.29   95.08    94.7   94.54   94.55    94.4   94.36
   94.33   94.35   93.59   93.36   93.28   93.26   93.08   93.06   92.95   92.79
   92.56   92.61   92.91   92.62   92.62   92.61  93.051  92.688  92.728  93.144
   92.69    92.6   92.75   92.83   92.83   92.86   92.83   93.28   93.32   93.59
   93.56   93.82   93.82   93.88   94.75    94.8    94.8   95.02   95.05   95.69
   95.82   96.35   96.77   96.64   97.03   97.48   97.65   97.55   98.06   98.36
   98.53   98.87   98.93   99.29   99.71   99.84   99.97  100.22  100.88  100.97
  101.03  101.31  101.99  101.94  102.22  102.21  102.29  102.28  102.28  103.21
   103.3  103.54  103.83  103.93  104.46  104.63  105.04  105.19  105.56  105.73
  105.87  106.17  106.15  106.31
                                                                                
                                                                                
                                                                                
                                                                                
                                                                                
                                                                                
                                                                                
                                                                                
                                                                                
                                                                                
                                                                                
                                                                                
                                                                                
                                                                                
                                                                                
                                                                                
                                                                                
                                
       0    1.83     4.1   16.98   18.81   24.44    36.5   47.78   56.42   65.77
   75.78   80.81   94.44   96.91  105.84  113.17  119.04   127.9   133.4   134.2
  140.27   142.7  154.96  158.64  176.26  176.84  177.02  177.97  194.91  195.27
   210.5  219.47  226.04  237.54  240.49  242.41  246.41  251.74  261.01  266.38
  274.37  279.45  281.76  291.39  293.11  297.67  310.87  315.04  316.88  330.22
  338.81  348.05  360.48  364.31  375.49  376.89  381.32  383.29  400.49  408.68
  419.59  433.73  438.78  454.27  458.16   459.4  473.23  477.15  483.72  495.97
  507.06  514.89  530.31  533.62  547.36  552.16  553.29  570.67   576.1  585.08
  588.87  598.31  607.16   616.1  625.79  635.67  637.86  639.94  651.15  664.43
  665.19  665.85  683.54  690.53  692.74   700.9  711.62  716.58  720.26  734.61
  749.23  753.77  764.04 778.994 833.262 856.747 896.686  957.56   964.9  975.52
  983.16  983.88  988.61  999.01 1007.43 1013.64 1021.49 1030.88 1049.19 1051.23
  1052.3  1069.9 1085.51  1088.7 1094.99 1095.72 1111.25 1119.43 1134.72 1151.31
  1155.9 1160.94 1172.08 1182.42 1187.05 1191.12 1197.12 1200.64 1211.47 1215.48
 1223.99 1235.89 1238.67  1241.3 1253.08 1266.85 1268.36 1270.14 1282.38 1292.89
 1297.13 1304.18 1313.35 1319.09 1326.85 1329.97 1344.42 1347.19 1353.72 1366.42
 1371.88 1389.57 1397.47 1415.09 1423.72 1437.92 1446.62 1456.92 1471.27 1475.57
 1483.85
   111.9   111.8  111.77  111.64  111.52  111.51  111.49     111  110.77  110.59
  110.62  110.58  110.38  110.41  109.85  109.68  109.84  109.37  109.24  109.29
  109.65   109.6  108.98     109  108.45  108.42  108.43   108.4  108.74  108.74
   108.2  107.76   107.6  107.47  107.52  107.41  107.36  107.19  107.06  107.01
  106.73  106.59  106.61  106.59  106.58  106.55  106.42  106.35  106.35  105.69
  105.57  105.47  104.98  104.55  104.47  104.43   104.3  104.22  103.54  103.05
  102.75   102.5  102.07  101.31  101.07  101.05  100.55   100.4  100.15   99.93
   99.52   98.95   98.53   98.36   98.17   97.96   97.93   96.95    96.9   96.46
   96.28   95.84   95.63   95.29   95.08    94.7   94.54   94.55    94.4   94.36
   94.33   94.35   93.59   93.36   93.28   93.26   93.08   93.06   92.95   92.79
   92.56   92.61   92.91  93.051  92.688  92.728  93.144   92.69    92.6   92.75
   92.83   92.83   92.86   92.83   93.28   93.32   93.59   93.56   93.82   93.82
   93.88   94.75    94.8    94.8   95.02   95.05   95.69   95.82   96.35   96.77
   96.64   97.03   97.48   97.65   97.55   98.06   98.36   98.53   98.87   98.93
   99.29   99.71   99.84   99.97  100.22  100.88  100.97  101.03  101.31  101.99
  101.94  102.22  102.21  102.29  102.28  102.28  103.21   103.3  103.54  103.83
  103.93  104.46  104.63  105.04  105.19  105.56  105.73  105.87  106.17  106.15
  106.31
                                                                                
                                                                                
                                                                                
                                                                                
                                                                                
                                                                                
                                                                                
                                                                                
                                                                                
                                                                                
                                                                                
                                                                                
                                                                                
                                                                                
                                                                                
                                                                                
                                                                                
        
BR Coef=-1 , 0 , 0 ,, 0 ,,,0.8,-1,,0,
WSPro=,,,, 1 ,,,, 0 ,,,, 0 ,,,,-1 ,-1 ,-1 , 0 , 0 , 0 , 0 , 0
Multiple Barrel Culv=1,4.5,,40,0.011,0.2,1,1,2,86.05,86.1, 2,Culvert #1  , 0 ,17
  830.37   852.2  839.37   861.2
Culvert Bottom n=0.011
BC Design=,, 0 ,, 0 ,,,,,,
BC Use User HTab Curves=0
BC User HTab FreeFlow(D)= 0

Type RM Length L Ch R = 1 ,6338    ,275.12,289.89,298.06
BEGIN DESCRIPTION:
Surveyed Section
END DESCRIPTION:
XS GIS Cut Line= 6
2333361.99775644704794.4919201882333006.85184523704764.680402085
2332700.95974652704776.3457787332332458.48000003 704814.31370002
2332045.28370249704823.3210038692331893.30933282704811.419120774
#Sta/Elev= 30
       0  113.55  290.79   108.1  363.03  108.56  501.85  100.21  512.96   99.05
  628.82   95.12  715.83   94.27   743.9   92.36  757.65   91.18   773.7   91.71
 785.217  92.489 843.877  91.837  848.95    89.1 854.735   86.09 857.251  85.827
 867.579  86.224  878.64   89.06 881.615  90.026 910.879   89.65  913.06   91.71
  945.67   90.73  963.94   93.59  993.25   93.38 1020.19   90.18 1066.04   91.75
 1076.13   91.09 1134.23   96.08  1215.7   98.87 1319.24  104.36 1476.58  110.38
#Mann= 8 ,-1 , 0
       0    .042       0  501.85    .035       0  715.83    .045       0
   743.9     .11       0   773.7    .045       0  848.95    .045       0
  878.64     .11       0  1215.7    .042       0
#XS Ineff= 2 , 0
       0  843.88   91.84  888.81       0    90.6
Permanent Ineff=
       F       F
Bank Sta=848.95,878.64
XS Rating Curve= 0 ,0
Exp/Cntr=0.5,0.3

Type RM Length L Ch R = 1 ,6048    ,314.93,293.69,276.2
XS GIS Cut Line= 6
  2333089.335915  704541.7655568 2332986.9631319  704516.1723611
 2332743.8277721  704507.6412958 2332308.7434441  704539.6327905
 2332135.9893727  704560.9604537 2331903.5178445  704601.4830136
#Sta/Elev= 30
       0   111.9   59.09  109.51   96.04  109.61  113.46  108.83  121.71  107.89
  131.47  107.96  268.36  103.17  364.66  101.62   388.3  100.63   420.2    98.6
  455.34   94.38  489.97   92.11  506.93   89.98  622.87   90.54   634.2   89.76
  666.61   90.91  677.34   89.88  697.78   84.84  702.02   84.84  723.19   89.19
  883.44   88.53  956.15   90.79  987.18   91.07 1009.64   92.51 1025.94   91.95
 1081.36   96.77 1110.19  100.24 1159.54  108.72  1184.6  112.29 1195.15  112.46
#Mann= 5 ,-1 , 0
       0    .042       0   388.3     .11       0  677.34    .045       0
  723.19     .11       0 1159.54    .042       0
Bank Sta=677.34,723.19
XS Rating Curve= 0 ,0
Exp/Cntr=0.5,0.3

Type RM Length L Ch R = 1 ,5754    ,83.62,78.37,92.09
BEGIN DESCRIPTION:
Surveyed Section
END DESCRIPTION:
XS GIS Cut Line= 6
 2333021.3556014  704433.7128247 2332925.1223617  704330.6057821
 2332797.9570092  704258.4308523 2332397.1186476   704238.281951
 2331939.8453971  704346.2981066 2331737.8651878  704523.7958663
#Sta/Elev= 30
       0  111.47   65.97  111.16  266.07  104.54  315.92   103.8     355   101.7
  440.33   99.48  509.77   96.12  577.53   95.77  655.68   93.44  689.45   92.26
  708.49   90.28  724.37   90.81  744.97   88.87 780.984  88.284  783.42  85.773
 785.426  83.795 789.437  83.809 790.154  85.892 791.157  87.153  846.67   88.87
  895.89   88.35  936.72   89.64  960.42   89.64  998.52   92.21 1048.79   93.91
 1171.76   99.62 1209.54  102.63 1237.64  102.34 1314.57     107 1432.74  112.57
#Mann= 4 ,-1 , 0
       0    .042       0  783.42    .045       0 790.154     .11       0
  936.72    .042       0
#XS Ineff= 2 , 0
       0  778.42   91.75  795.15       0   91.65
Permanent Ineff=
       F       F
Bank Sta=783.42,790.154
XS Rating Curve= 0 ,0
Exp/Cntr=0.5,0.3