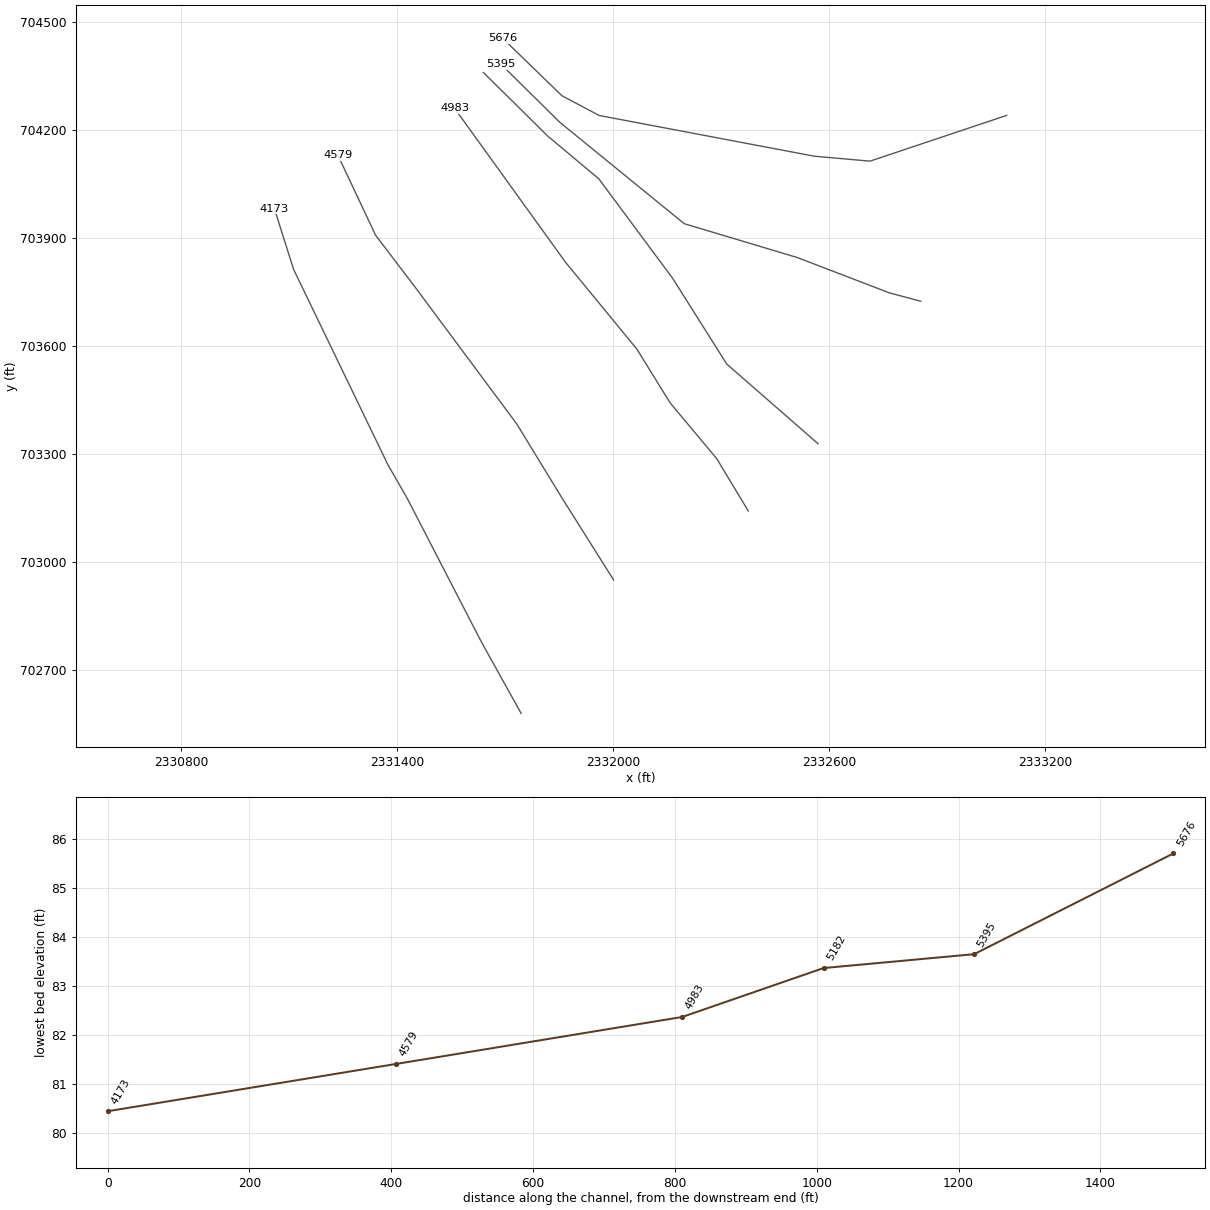
HEC-RAS study dtl_Hominy_Swamp_Trib1.prj: DTL_Hominy_Swamp_Trib1

--- dtl_Hominy_Swamp_Trib1.g01 (geometry) --- (continued)

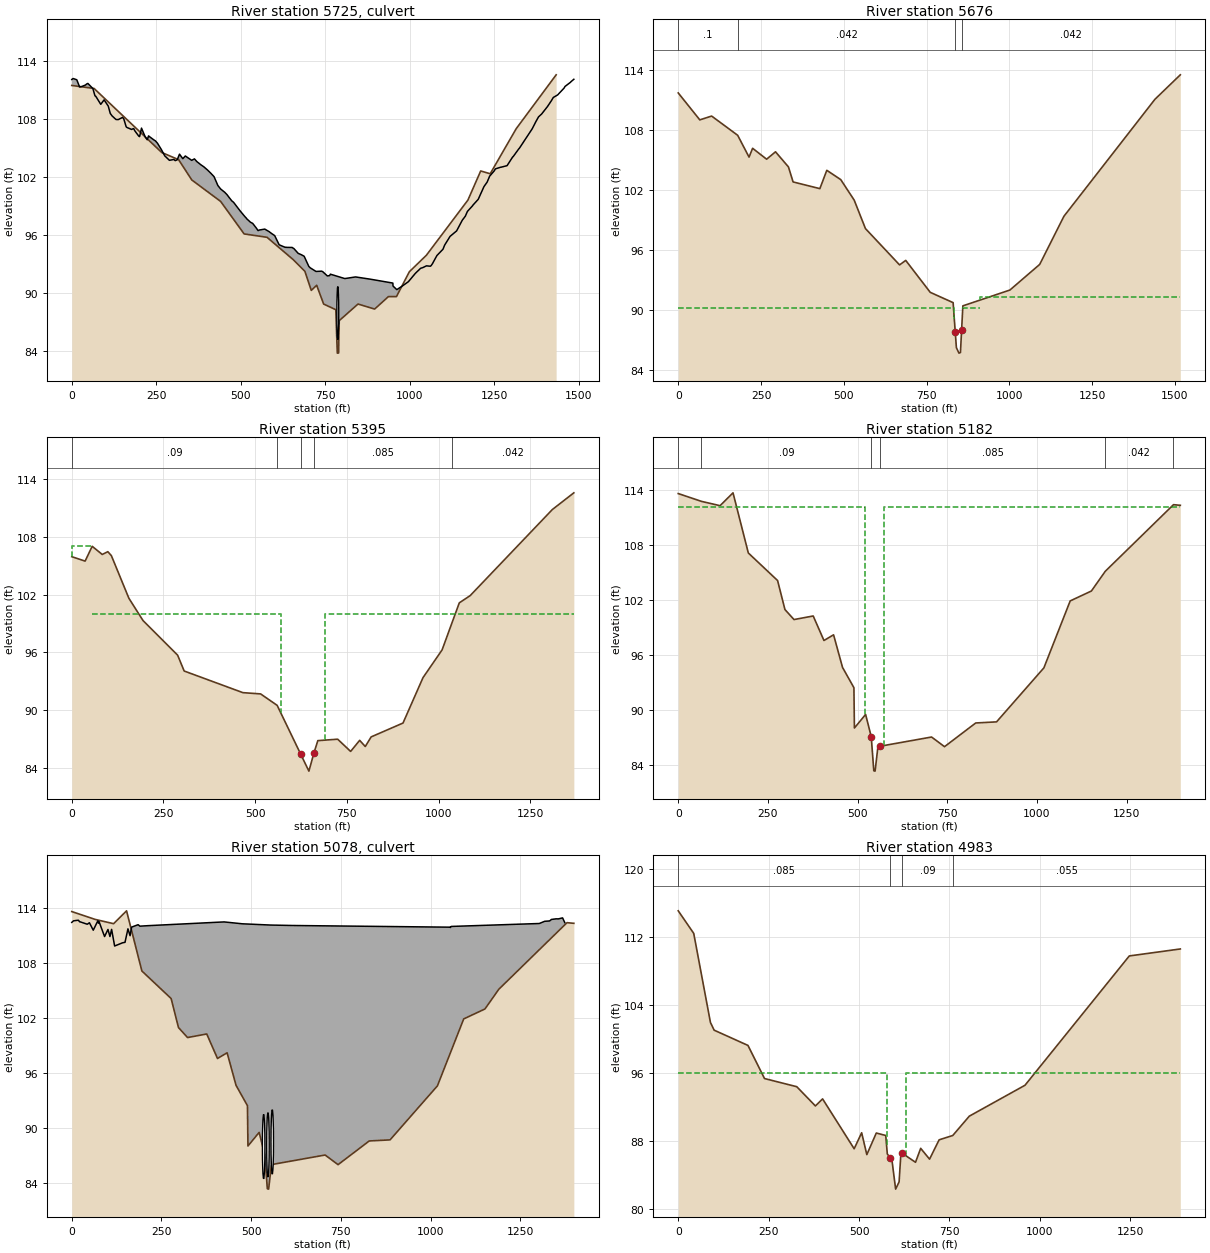
Type RM Length L Ch R = 2 ,5725    ,,,
BEGIN DESCRIPTION:
Golf cart path
END DESCRIPTION:
Bridge Culvert--1,0,-1,-1, 0
Deck Dist Width WeirC Skew NumUp NumDn MinLoCord MaxHiCord MaxSubmerge Is_Ogee
25,6,2.6,0, 193, 193, , , 0.95, 0, 1,1,,
       0    4.08   14.81   22.61   22.95   23.64    28.6   40.71   43.88   47.61
   54.93   62.45   68.36   69.07   70.09   70.83   85.66   85.77   90.68   95.66
  107.87  114.03   114.4  114.97  119.01  129.29   130.8  137.14  137.38  150.28
  153.89  160.85  163.03  177.18  179.59  183.14  186.32  197.74  199.85  200.46
  200.85  206.25  217.45  223.18  227.15  229.39  242.11  246.14  247.42  253.46
  256.15  264.74  275.07  288.86  301.93  305.87  311.82  318.64  328.45  335.65
  335.86  336.15  336.27  342.67  354.69  362.45  362.72  362.83  369.74  369.99
     370  382.26  390.61  401.53  411.18  420.88  432.13  440.19  452.65  459.45
  463.01  473.07  478.81  493.13  498.25  513.05  515.95  517.43   528.6   535.1
  545.78  551.08  554.33  569.38  570.89  579.53  583.57  591.95  600.15  613.25
  617.09  631.69  633.88  634.46   651.9  653.44  657.16  669.72  679.07  687.41
  701.15  705.14  721.97  722.36  722.44  732.56  738.97   742.5  755.88   762.6
 764.955 807.576 839.357 882.423 949.697  950.28  961.29  961.43   978.4  995.57
  995.74  995.91 1016.48 1031.96 1035.43 1037.82 1046.99 1049.26 1060.64 1063.06
 1066.79 1080.12 1093.22 1098.04 1099.93 1102.83 1118.99 1136.66 1138.22 1139.91
 1140.81 1155.13 1164.03 1170.36 1180.71 1183.03 1185.73 1186.43  1202.3 1207.32
 1219.17 1228.61    1236 1249.77 1251.75 1252.76 1268.83 1270.13 1286.34 1287.48
 1287.58 1304.15 1305.74 1321.21 1324.38 1338.32 1343.02 1355.39 1361.73 1372.59
 1380.53 1389.84 1399.32 1407.07 1418.14 1424.33 1437.04  1441.6 1455.98 1459.01
 1475.15 1476.54 1485.06
  112.09  112.19  112.06  111.34  111.34  111.31  111.35  111.52  111.62  111.68
  111.42  111.15  110.43  110.39  110.36  110.36  109.53  109.52  109.75  109.98
  109.34  108.56  108.56  108.53  108.33     108  107.95  107.94  107.94  108.17
  108.01   107.2  107.13  106.92  106.97  107.01  106.79  106.25   106.2  106.18
  106.21  107.06  106.13  105.86  106.26  106.19  105.86  105.77  105.74   105.5
  105.35  104.86  104.19  103.73  103.82   103.7  103.78  104.37   103.9  104.17
  104.18  104.17  104.17  104.02  103.73  103.88  103.88  103.88  103.61   103.6
   103.6  103.26  103.06  102.73   102.4  102.04  101.13  100.77  100.42  100.17
     100   99.55   99.38   98.73   98.49   97.87   97.77   97.69   97.33   97.21
   96.73   96.46   96.52   96.61   96.62   96.44   96.36   96.14   95.95   95.01
   94.94   94.73   94.75   94.73   94.72   94.68    94.6   94.11   93.97   93.81
   92.76   92.62   92.25   92.24   92.24   92.26   92.27   92.21   91.78   91.81
  91.959  91.504  91.673  91.445  91.039   90.73   90.36   90.36   90.75   91.18
   91.18   91.19   92.05   92.57   92.61   92.63   92.78   92.82   92.78   92.85
   93.04   93.89   94.36   94.54    94.7   94.96   95.87   96.38   96.43   96.54
    96.6   97.54   97.95   98.45   98.84   98.92   99.04   99.09    99.7  100.09
  101.01  101.48  102.09  102.65  102.78  102.84  103.02  103.02  103.16  103.18
  103.18  104.08  104.12  104.87     105  105.75  105.99  106.64  106.98  107.72
  108.22  108.52  108.95  109.29  109.87  110.23  110.49  110.66  111.19  111.37
   111.8  111.86  112.11
                                                                                
                                                                                
                                                                                
                                                                                
                                                                                
                                                                                
                                                                                
                                                                                
                                                                                
                                                                                
                                                                                
                                                                                
                                                                                
                                                                                
                                                                                
                                                                                
                                                                                
                                                                                
                                                                                
                        
       0    4.08   14.81   22.61   22.95   23.64    28.6   40.71   43.88   47.61
   54.93   62.45   68.36   69.07   70.09   70.83   85.66   85.77   90.68   95.66
  107.87  114.03   114.4  114.97  119.01  129.29   130.8  137.14  137.38  150.28
  153.89  160.85  163.03  177.18  179.59  183.14  186.32  197.74  199.85  200.46
  200.85  206.25  217.45  223.18  227.15  229.39  242.11  246.14  247.42  253.46
  256.15  264.74  275.07  288.86  301.93  305.87  311.82  318.64  328.45  335.65
  335.86  336.15  336.27  342.67  354.69  362.45  362.72  362.83  369.74  369.99
     370  382.26  390.61  401.53  411.18  420.88  432.13  440.19  452.65  459.45
  463.01  473.07  478.81  493.13  498.25  513.05  515.95  517.43   528.6   535.1
  545.78  551.08  554.33  569.38  570.89  579.53  583.57  591.95  600.15  613.25
  617.09  631.69  633.88  634.46   651.9  653.44  657.16  669.72  679.07  687.41
  701.15  705.14  721.97  722.36  722.44  732.56  738.97   742.5  755.88   762.6
 764.955 807.576 839.357 882.423 949.697  950.28  961.29  961.43   978.4  995.57
  995.74  995.91 1016.48 1031.96 1035.43 1037.82 1046.99 1049.26 1060.64 1063.06
 1066.79 1080.12 1093.22 1098.04 1099.93 1102.83 1118.99 1136.66 1138.22 1139.91
 1140.81 1155.13 1164.03 1170.36 1180.71 1183.03 1185.73 1186.43  1202.3 1207.32
 1219.17 1228.61    1236 1249.77 1251.75 1252.76 1268.83 1270.13 1286.34 1287.48
 1287.58 1304.15 1305.74 1321.21 1324.38 1338.32 1343.02 1355.39 1361.73 1372.59
 1380.53 1389.84 1399.32 1407.07 1418.14 1424.33 1437.04  1441.6 1455.98 1459.01
 1475.15 1476.54 1485.06
  112.09  112.19  112.06  111.34  111.34  111.31  111.35  111.52  111.62  111.68
  111.42  111.15  110.43  110.39  110.36  110.36  109.53  109.52  109.75  109.98
  109.34  108.56  108.56  108.53  108.33     108  107.95  107.94  107.94  108.17
  108.01   107.2  107.13  106.92  106.97  107.01  106.79  106.25   106.2  106.18
  106.21  107.06  106.13  105.86  106.26  106.19  105.86  105.77  105.74   105.5
  105.35  104.86  104.19  103.73  103.82   103.7  103.78  104.37   103.9  104.17
  104.18  104.17  104.17  104.02  103.73  103.88  103.88  103.88  103.61   103.6
   103.6  103.26  103.06  102.73   102.4  102.04  101.13  100.77  100.42  100.17
     100   99.55   99.38   98.73   98.49   97.87   97.77   97.69   97.33   97.21
   96.73   96.46   96.52   96.61   96.62   96.44   96.36   96.14   95.95   95.01
   94.94   94.73   94.75   94.73   94.72   94.68    94.6   94.11   93.97   93.81
   92.76   92.62   92.25   92.24   92.24   92.26   92.27   92.21   91.78   91.81
  91.959  91.504  91.673  91.445  91.039   90.73   90.36   90.36   90.75   91.18
   91.18   91.19   92.05   92.57   92.61   92.63   92.78   92.82   92.78   92.85
   93.04   93.89   94.36   94.54    94.7   94.96   95.87   96.38   96.43   96.54
    96.6   97.54   97.95   98.45   98.84   98.92   99.04   99.09    99.7  100.09
  101.01  101.48  102.09  102.65  102.78  102.84  103.02  103.02  103.16  103.18
  103.18  104.08  104.12  104.87     105  105.75  105.99  106.64  106.98  107.72
  108.22  108.52  108.95  109.29  109.87  110.23  110.49  110.66  111.19  111.37
   111.8  111.86  112.11
                                                                                
                                                                                
                                                                                
                                                                                
                                                                                
                                                                                
                                                                                
                                                                                
                                                                                
                                                                                
                                                                                
                                                                                
                                                                                
                                                                                
                                                                                
                                                                                
                                                                                
                                                                                
                                                                                
                        
BR Coef=-1 , 0 , 0 ,, 0 ,,,0.8,0,,0,
WSPro=,,,, 1 ,,,, 0 ,,,, 0 ,,,,-1 ,-1 ,-1 , 0 , 0 , 0 , 0 , 0
Culvert=1,5.5,,18,0.025,0.5,1,2,1,85.1791,786.87,84.6322,847.98,Culvert #1  , 0 ,20
Culvert Bottom n=0.025
BC Design=,, 0 ,, 0 ,,,,,,
BC Use User HTab Curves=0
BC User HTab FreeFlow(D)= 0

Type RM Length L Ch R = 1 ,5676    ,264.09,281.11,252.88
BEGIN DESCRIPTION:
Surveyed Section
END DESCRIPTION:
XS GIS Cut Line= 6
 2333093.5305312  704241.2463452 2332713.7529244  704114.0809927
 2332559.0923606  704127.8285984 2331961.4381165  704240.9454485
 2331858.1248599  704295.7907576 2331693.5889326  704455.2247957
#Sta/Elev= 30
       0  111.69   65.12     109  100.88  109.38  179.51  107.46  213.84  105.28
  224.61  106.16   266.9  105.07  293.72  105.81  332.81   104.3  346.84   102.8
  427.68  102.13  448.66  103.96  490.81  103.03  531.42  100.98  565.33   98.14
  668.43   94.51  686.98   94.96  761.02   91.77 830.103   90.74  836.53   87.81
 839.958  86.243 847.691  85.696 852.239  85.759  855.66   87.96 859.517  90.418
 1001.63      92 1091.55   94.56 1164.73   99.37 1439.64  111.06 1516.17   113.5
#Mann= 4 ,-1 , 0
       0      .1       0  179.51    .042       0  836.53     .05       0
  855.66    .042       0
#XS Ineff= 3 ,-1
       0   833.6    90.2  858.98 911.825    90.2 911.825 1516.17   91.35
Permanent Ineff=
       F       F       F
Bank Sta=836.53,855.66
XS Rating Curve= 0 ,0
Exp/Cntr=0.5,0.3

Type RM Length L Ch R = 1 ,5395    ,228.16,212.34,188.07
XS GIS Cut Line= 6
 2332854.7316204  703724.9160586 2332767.2882016  703748.3764881
 2332511.3562439  703846.4837385 2332197.8395958  703940.3254564
  2331852.331453  704221.8506098 2331688.1084468  704383.9408496
#Sta/Elev= 30
       0  105.94   36.42  105.48   55.64  107.02   83.08  106.17   98.28  106.46
  107.94  106.05  155.63  101.62  194.16    99.3  288.55    95.7  306.39   94.05
  466.46    91.8  514.68   91.67  559.85   90.48  623.76   85.42  646.36   83.64
  659.65   85.48  670.67   86.81  724.78   86.96  760.09   85.69  784.73   86.84
  799.97    86.2  816.03    87.2  902.87   88.64  957.33   93.36 1009.44   96.25
 1036.91   99.12 1056.33  101.14 1085.94  101.89 1309.84  110.84  1368.5  112.58
#Mann= 5 ,-1 , 0
       0     .09       0  559.85    .085       0  623.76    .047       0
  659.65    .085       0 1036.91    .042       0
#XS Ineff= 3 ,-1
       0   55.64  107.02   55.64     570     100     690  1368.5     100
Permanent Ineff=
       F       F       F
Bank Sta=623.76,659.65
XS Rating Curve= 0 ,0
Exp/Cntr=0.5,0.3

Type RM Length L Ch R = 1 ,5182    ,195.76,199.4,197.18
BEGIN DESCRIPTION:
Surveyed Section
END DESCRIPTION:
XS GIS Cut Line= 6
 2332569.4623209  703329.2176792 2332315.7215224  703550.6641942
    2332165.6465     703788.4892 2331960.4844047  704065.0659946
 2331819.7735983  704182.7094557 2331639.8483049  704360.3280146
#Sta/Elev= 30
       0  113.58    64.8  112.73  116.61  112.26  152.72  113.66  195.38  107.11
  276.94  104.11  297.44  100.95  322.72   99.86  376.21  100.25  406.19   97.58
  432.99    98.2  457.96   94.65   489.7   92.44 491.074  88.052 522.282  89.529
 537.956  87.117 545.094  83.397 548.732  83.357 556.289  85.902  562.92   86.07
  706.16   87.07  742.27   86.02  829.19    88.6  887.28   88.72 1019.21    94.6
 1092.52  101.89 1151.66  102.97 1190.39  105.12 1380.44  112.37 1399.47   112.3
#Mann= 6 ,-1 , 0
       0    .045       0    64.8     .09       0 537.956    .042       0
  562.92    .085       0 1190.39    .042       0 1380.44    .085       0
#XS Ineff= 2 , 0
       0  521.33  112.11  572.33       0  112.11
Permanent Ineff=
       F       F
Bank Sta=537.956,562.92
XS Rating Curve= 0 ,0
Exp/Cntr=0.5,0.3

Type RM Length L Ch R = 2 ,5078    ,,,
BEGIN DESCRIPTION:
Railroad
END DESCRIPTION:
Bridge Culvert--1,0,-1,-1, 0
Deck Dist Width WeirC Skew NumUp NumDn MinLoCord MaxHiCord MaxSubmerge Is_Ogee
87,28,2.6,0, 39, 23, , , 0.95, 0, 1,1,,
       0    4.79   18.39   22.05   24.16    43.2   49.22   59.86   72.64   74.59
   76.06   91.43  100.91   106.4  111.03  119.47   141.7   148.4  156.59  162.48
  166.85  184.97  189.92  210.29 424.538 475.801 555.101 614.748  1054.6 1055.06
 1057.68 1303.14 1318.09 1331.93 1336.96 1350.01 1355.82  1368.1 1374.35
   112.4  112.57  112.64  112.46  112.45   112.2  112.36  111.55  112.57  112.32
  112.48  110.86  111.63  110.86  111.64  109.83  110.18  110.23   111.7  110.95
  111.89  112.15  111.99  112.04 112.453 112.247  112.11 112.064  111.88  111.84
  111.96  112.28  112.52  112.56  112.72  112.79  112.78  112.89  112.37
                                                                                
                                                                                
                                                                                
                                                                        
       0    4.79   18.39   22.05   24.16    43.2   49.22  166.85  184.97  189.92
  210.29 424.538 475.801 555.101 614.748  1054.6 1318.09 1331.93 1336.96 1350.01
 1355.82  1368.1 1374.35
   112.4  112.57  112.64  112.46  112.45   112.2  112.36  111.89  112.15  111.99
  112.04 112.453 112.247  112.11 112.064  111.88  112.52  112.56  112.72  112.79
  112.78  112.89  112.37
                                                                                
                                                                                
                        
BR Coef=-1 , 0 , 0 ,, 0 ,,,0.8,-1,,0,
WSPro=,,,, 1 ,,,, 0 ,,,, 0 ,,,,-1 ,-1 ,-1 , 0 , 0 , 0 , 0 , 0
Culvert=1,7,,100,0.027,0.9,1,2,3,84.4885,534.83,84.2987,590.6,Culvert #1  , 0 ,52
Culvert Bottom n=0.027
Culvert=1,7,,100,0.027,0.9,1,2,3,84.6814,546.83,84.3451,602.6,Culvert #2  , 0 ,53
Culvert Bottom n=0.027
Culvert=1,7,,100,0.027,0.9,1,2,3,84.9991,558.83,84.5058,614.6,Culvert #3  , 0 ,52
Culvert Bottom n=0.027
BC Design=,, 0 ,, 0 ,,,,,,
BC Use User HTab Curves=0
BC User HTab FreeFlow(D)= 0

Type RM Length L Ch R = 1 ,4983    ,391.56,403.81,387.14
BEGIN DESCRIPTION:
Surveyed Section
END DESCRIPTION:
XS GIS Cut Line= 6
 2332375.6966203  703142.3721822 2332288.0407081  703287.6964576
 2332158.8635743  703442.2476712    2332066.1225     703592.0798
 2331867.8236698  703833.5123601 2331560.0823965  704260.6199455
#Sta/Elev= 30
       0  115.05   42.86   112.4   89.11  101.93   99.34  101.03  192.89   99.24
  238.64   95.35  327.83   94.39  379.35   92.13  399.23   92.96  486.54    87.1
  507.29   88.98 521.544  86.412 547.788  88.949 573.893   88.66 578.197  86.495
  586.11   86.04 590.972  85.793 601.247  82.359 610.828  83.211 615.966  86.636
  619.25   86.58 656.234  85.512  670.56   87.15  695.05   85.88  721.53   88.15
  759.27   88.66  805.03   90.93     959   94.56 1247.47  109.75 1388.56  110.57
#Mann= 4 ,-1 , 0
       0    .085       0  586.11     .05       0  619.25     .09       0
  759.27    .055       0
#XS Ineff= 2 , 0
       0  576.11      96  629.25       0      96
Permanent Ineff=
       F       F
Bank Sta=586.11,619.25
XS Rating Curve= 0 ,0
Exp/Cntr=0.5,0.3

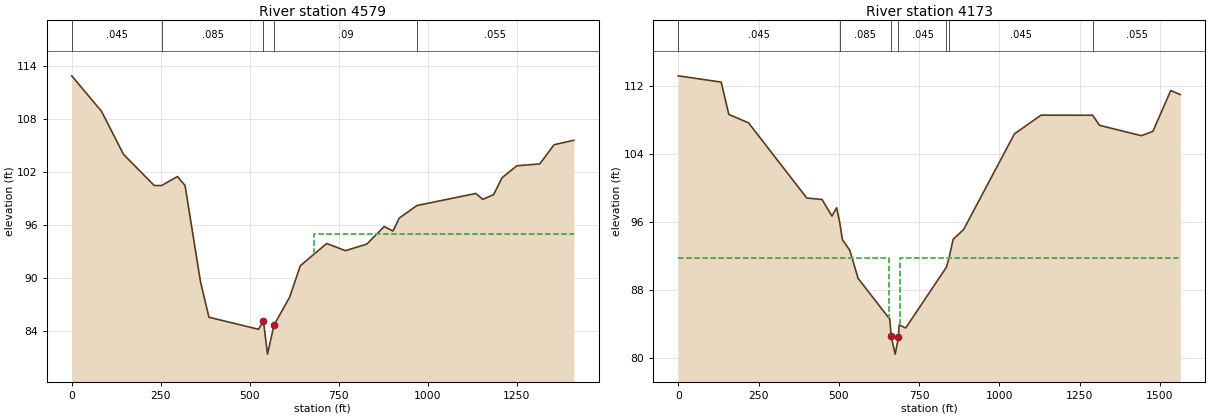
Type RM Length L Ch R = 1 ,4579    ,377.31,406.47,357.8
XS GIS Cut Line= 6
 2332001.6250949  702950.7218867 2331856.5969856  703181.0606486
 2331732.8965394  703383.6734484 2331449.2386197  703765.4386186
 2331340.4675376  703908.3339616 2331235.9619883  704130.1416583
#Sta/Elev= 30
       0  112.87   83.63  108.85  145.33  103.99  231.54  100.47   252.1  100.46
  296.62  101.48  318.08  100.48  361.52   89.58  385.31   85.57  524.32   84.21
  538.33   85.11  549.72    81.4   567.8   84.67  611.83   87.84  641.83   91.39
  715.89   93.91  768.58    93.1  828.54   93.84  877.33   95.83  902.06   95.32
  919.55   96.78  969.21    98.2 1134.69   99.57 1154.27    98.9 1184.76   99.44
 1208.24  101.34 1249.97   102.7 1314.47  102.91 1354.44  105.08 1409.97  105.58
#Mann= 5 ,-1 , 0
       0    .045       0   252.1    .085       0  538.33    .045       0
   567.8     .09       0  969.21    .055       0
#XS Ineff= 2 , 0
       0                     680       0   94.98
Permanent Ineff=
       F       F
Bank Sta=538.33,567.8
XS Rating Curve= 0 ,0
Exp/Cntr=0.5,0.3

Type RM Length L Ch R = 1 ,4173    ,98.39,96.27,84.07
BEGIN DESCRIPTION:
Surveyed Section
END DESCRIPTION:
XS GIS Cut Line= 6
 2331744.7271605  702580.1660833 2331634.6863416  702777.8665377
    2331428.5084     703177.0508     2331374.745     703270.6633
 2331112.6101843  703813.5647395 2331059.2957762  703982.3936983
#Sta/Elev= 30
       0  113.21  133.79  112.47  157.53  108.67  218.97  107.67  400.45   98.82
  447.92   98.65  478.79    96.7  493.37   97.68  502.45   96.06  511.51   93.91
   534.4   92.66  560.17   89.36 658.992  84.553 663.214  82.512 675.881  80.436
  685.89  82.433 687.923  83.867 708.565  83.519  835.55   90.69  843.84   91.84
  856.29   93.96  888.89   95.11 1047.13  106.37 1129.91  108.58 1290.77  108.57
 1312.16  107.38  1442.7  106.16 1478.62  106.68 1534.11  111.48 1563.82     111
#Mann= 7 ,-1 , 0
       0    .045       0  502.45    .085       0 663.214    .047       0
  685.89    .045       0  835.55     .09       0  843.84    .045       0
 1290.77    .055       0
#XS Ineff= 2 , 0
       0  657.09   91.71  690.89       0   91.71
Permanent Ineff=
       F       F
Bank Sta=663.214,685.89
XS Rating Curve= 0 ,0
Exp/Cntr=0.5,0.3