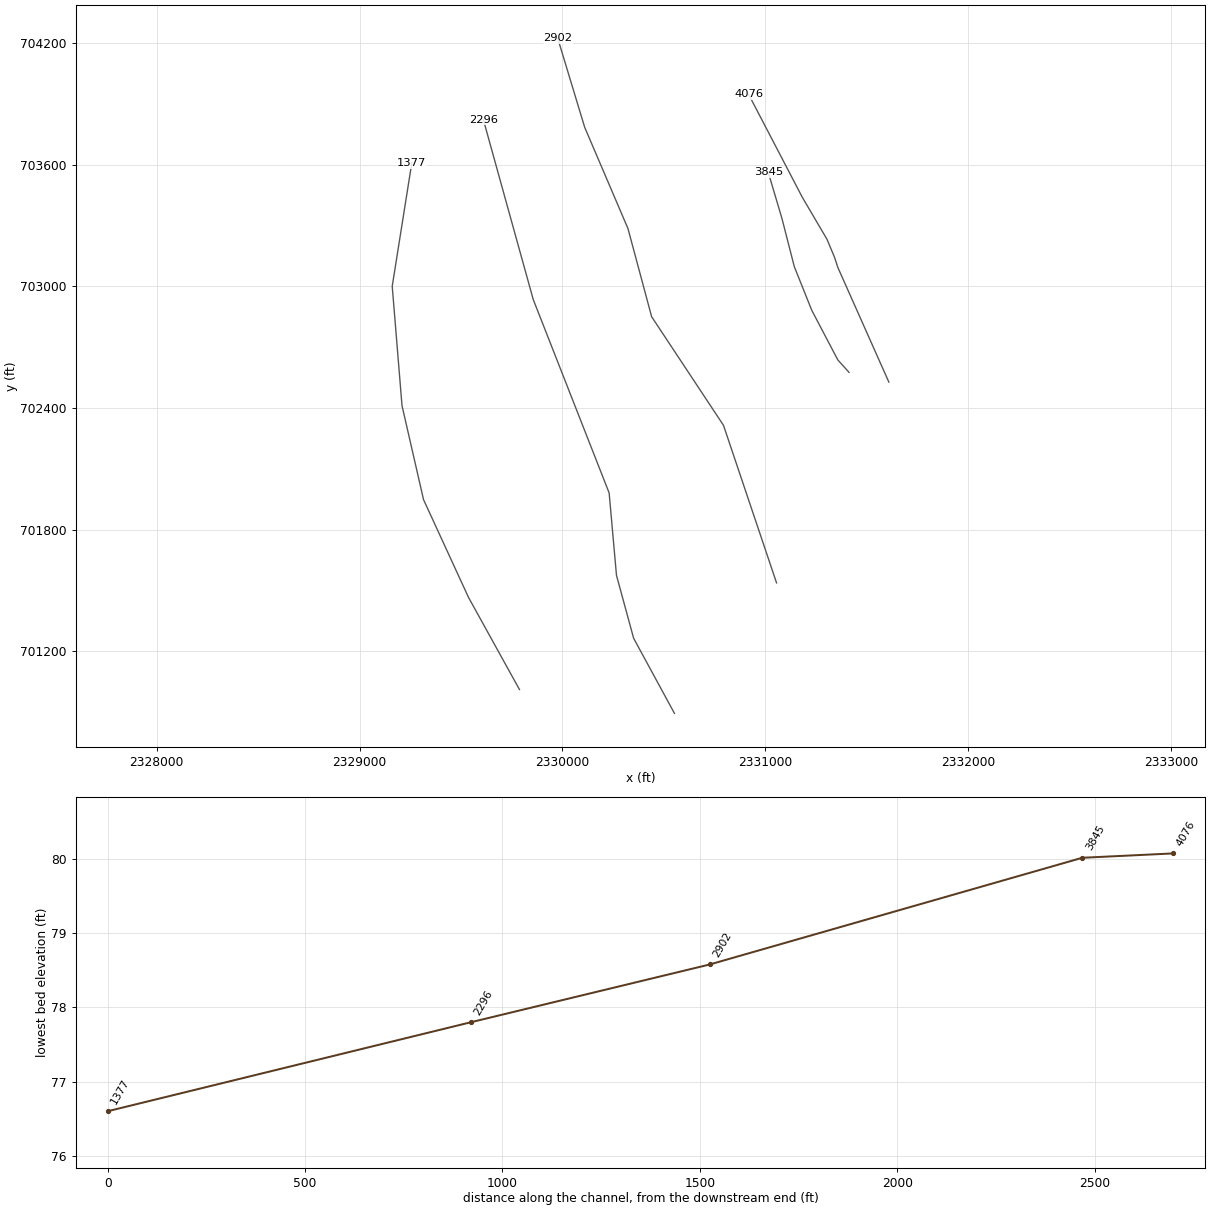
HEC-RAS study dtl_Hominy_Swamp_Trib1.prj: DTL_Hominy_Swamp_Trib1

--- dtl_Hominy_Swamp_Trib1.g01 (geometry) --- (continued)

Type RM Length L Ch R = 2 ,4117    ,,,
BEGIN DESCRIPTION:
Old Statonsburg Rd
END DESCRIPTION:
Bridge Culvert--1,0,-1,-1, 0
Deck Dist Width WeirC Skew NumUp NumDn MinLoCord MaxHiCord MaxSubmerge Is_Ogee
40,21,2.6,0, 165, 168, , , 0.95, 0, 1,1,,
       0     .51   13.08   17.16   36.77   39.03   41.61   51.66   60.89   64.32
   68.92    76.8   82.81    92.5  104.67   108.8  114.02  120.88  126.37  133.77
  138.03  144.53  146.68  148.08  160.02  168.88  172.91  177.74  185.11   191.4
  197.09  204.26  209.19  213.31  227.05   233.7  246.21  256.84  261.36  262.35
   271.3  276.52  279.79  291.46  302.65     306  309.77  317.84  324.78  329.86
  335.24  342.18  348.66  355.11  363.06  363.47  369.43  374.52  388.43  398.81
  405.11  410.65  416.95   425.5   431.4  437.23  449.06  456.66   466.3  470.79
 471.145 550.185 615.922 663.408 724.196 818.703  880.78  893.02  899.44  917.68
   917.9  918.57  923.11  935.42  941.29  953.02  965.23  970.93  986.92  988.71
  989.25 1006.12 1011.92 1023.48 1034.39 1040.91  1057.1 1058.32  1062.4 1076.19
 1080.43  1094.3 1103.97 1112.32 1127.73 1130.41 1139.17 1148.64 1151.75 1167.39
  1176.8 1186.41 1201.93 1205.14 1214.88 1224.39 1238.11 1243.98 1259.57 1263.55
 1265.48 1270.96  1277.5 1283.35 1287.94  1293.2 1302.38 1307.99  1320.4 1326.16
 1337.48 1338.57 1340.27 1352.88 1353.15 1359.28 1368.48 1375.95 1381.98  1385.7
 1396.64 1399.59 1404.72 1407.72 1409.41 1421.65 1424.42 1430.42 1437.17 1443.39
 1450.73  1453.9  1461.8 1463.22 1472.85 1477.28 1489.65 1491.72 1492.66 1496.93
 1508.58 1514.52  1516.2 1533.01 1546.77
  108.42  108.41     108  107.95  107.95  107.92  107.86  107.77  107.44  107.41
  107.29  107.23  106.88   106.5  106.27  106.27  106.07  105.97  105.69  105.56
  105.66  105.82  105.84  105.85  105.21  104.72  104.59  104.43  104.26   103.9
  103.65  103.36  103.18  102.92  102.28  102.05  101.65  101.36  101.13  101.08
  100.65  100.47  100.27   99.92   99.54   99.29   99.13   98.77   98.21   98.08
   98.04   98.02   97.85   97.64   97.26   97.25   97.04    96.8   96.25   95.81
   95.65   95.47   95.35    95.1   94.96   94.79    94.3   94.22   93.73   93.64
  94.662  92.726  91.817  91.659  91.866  94.101   94.99   95.34   95.65   96.15
   96.15   96.17   96.33   96.75   97.02   97.39   97.59   97.91   98.63   98.72
   98.77   99.41   99.79  100.38  100.65   101.1  101.75  101.78  101.96   102.5
  102.68  103.13  103.31  103.82   104.4  104.48  104.75  105.07  105.26  105.73
  105.97  106.45  106.97  107.09  107.38  107.64  107.91  108.25  108.57  108.68
  108.78  108.88  109.16  109.37  109.52  109.73  109.99  109.98   110.1  110.22
  110.67  110.71  110.72   110.8   110.8  110.88  111.06  111.06  111.06  111.07
  111.31  111.43  111.44  111.48  111.55  111.62  111.76  111.59  111.53  112.14
  111.86  111.55  112.15  112.23  112.04  112.33  112.21  112.14  112.23  112.27
  112.59  112.76  112.74  112.89  113.12
                                                                                
                                                                                
                                                                                
                                                                                
                                                                                
                                                                                
                                                                                
                                                                                
                                                                                
                                                                                
                                                                                
                                                                                
                                                                                
                                                                                
                                                                                
                                                                                
                                        
       0     .51   13.08   17.16   36.77   39.03   41.61   51.66   60.89   64.32
   68.92    76.8   82.81    92.5  104.67   108.8  114.02  120.88  126.37  133.77
  138.03  144.53  146.68  148.08  160.02  168.88  172.91  177.74  185.11   191.4
  197.09  204.26  209.19  213.31  227.05   233.7  246.21  256.84  261.36  262.35
   271.3  276.52  279.79  291.46  302.65     306  309.77  317.84  324.78  329.86
  335.24  342.18  348.66  355.11  363.06  363.47  369.43  374.52  388.43  398.81
  405.11  410.65  416.95   425.5   431.4 471.145 550.185 615.922 663.408 724.196
 818.703  822.87  827.57  843.48  843.62  843.66  843.72  862.18  868.35  880.78
  893.02  899.44  917.68   917.9  918.57  923.11  935.42  941.29  953.02  965.23
  970.93  986.92  988.71  989.25 1006.12 1011.92 1023.48 1034.39 1040.91  1057.1
 1058.32  1062.4 1076.19 1080.43  1094.3 1103.97 1112.32 1127.73 1130.41 1139.17
 1148.64 1151.75 1167.39  1176.8 1186.41 1201.93 1205.14 1214.88 1224.39 1238.11
 1243.98 1259.57 1263.55 1265.48 1270.96  1277.5 1283.35 1287.94  1293.2 1302.38
 1307.99  1320.4 1326.16 1337.48 1338.57 1340.27 1352.88 1353.15 1359.28 1368.48
 1375.95 1381.98  1385.7 1396.64 1399.59 1404.72 1407.72 1409.41 1421.65 1424.42
 1430.42 1437.17 1443.39 1450.73  1453.9  1461.8 1463.22 1472.85 1477.28 1489.65
 1491.72 1492.66 1496.93 1508.58 1514.52  1516.2 1533.01 1546.77
  108.42  108.41     108  107.95  107.95  107.92  107.86  107.77  107.44  107.41
  107.29  107.23  106.88   106.5  106.27  106.27  106.07  105.97  105.69  105.56
  105.66  105.82  105.84  105.85  105.21  104.72  104.59  104.43  104.26   103.9
  103.65  103.36  103.18  102.92  102.28  102.05  101.65  101.36  101.13  101.08
  100.65  100.47  100.27   99.92   99.54   99.29   99.13   98.77   98.21   98.08
   98.04   98.02   97.85   97.64   97.26   97.25   97.04    96.8   96.25   95.81
   95.65   95.47   95.35    95.1   94.96  94.662  92.726  91.817  91.659  91.866
  94.101   93.11   93.33   93.96   93.97   93.97   93.97   94.35   94.57   94.99
   95.34   95.65   96.15   96.15   96.17   96.33   96.75   97.02   97.39   97.59
   97.91   98.63   98.72   98.77   99.41   99.79  100.38  100.65   101.1  101.75
  101.78  101.96   102.5  102.68  103.13  103.31  103.82   104.4  104.48  104.75
  105.07  105.26  105.73  105.97  106.45  106.97  107.09  107.38  107.64  107.91
  108.25  108.57  108.68  108.78  108.88  109.16  109.37  109.52  109.73  109.99
  109.98   110.1  110.22  110.67  110.71  110.72   110.8   110.8  110.88  111.06
  111.06  111.06  111.07  111.31  111.43  111.44  111.48  111.55  111.62  111.76
  111.59  111.53  112.14  111.86  111.55  112.15  112.23  112.04  112.33  112.21
  112.14  112.23  112.27  112.59  112.76  112.74  112.89  113.12
                                                                                
                                                                                
                                                                                
                                                                                
                                                                                
                                                                                
                                                                                
                                                                                
                                                                                
                                                                                
                                                                                
                                                                                
                                                                                
                                                                                
                                                                                
                                                                                
                                                                
BR Coef=-1 , 0 , 0 ,, 0 ,,,0.8,0,,0,
WSPro=,,,, 1 ,,,, 0 ,,,, 0 ,,,,-1 ,-1 ,-1 , 0 , 0 , 0 , 0 , 0
Multiple Barrel Culv=1,6,,60,0.028,0.7,1,2,2,81.13,80.8, 2,Culvert #1  , 0 ,19
   667.5  649.03   680.5  662.03
Culvert Bottom n=0.028
BC Design=,, 0 ,, 0 ,,,,,,
BC Use User HTab Curves=0
BC User HTab FreeFlow(D)= 0

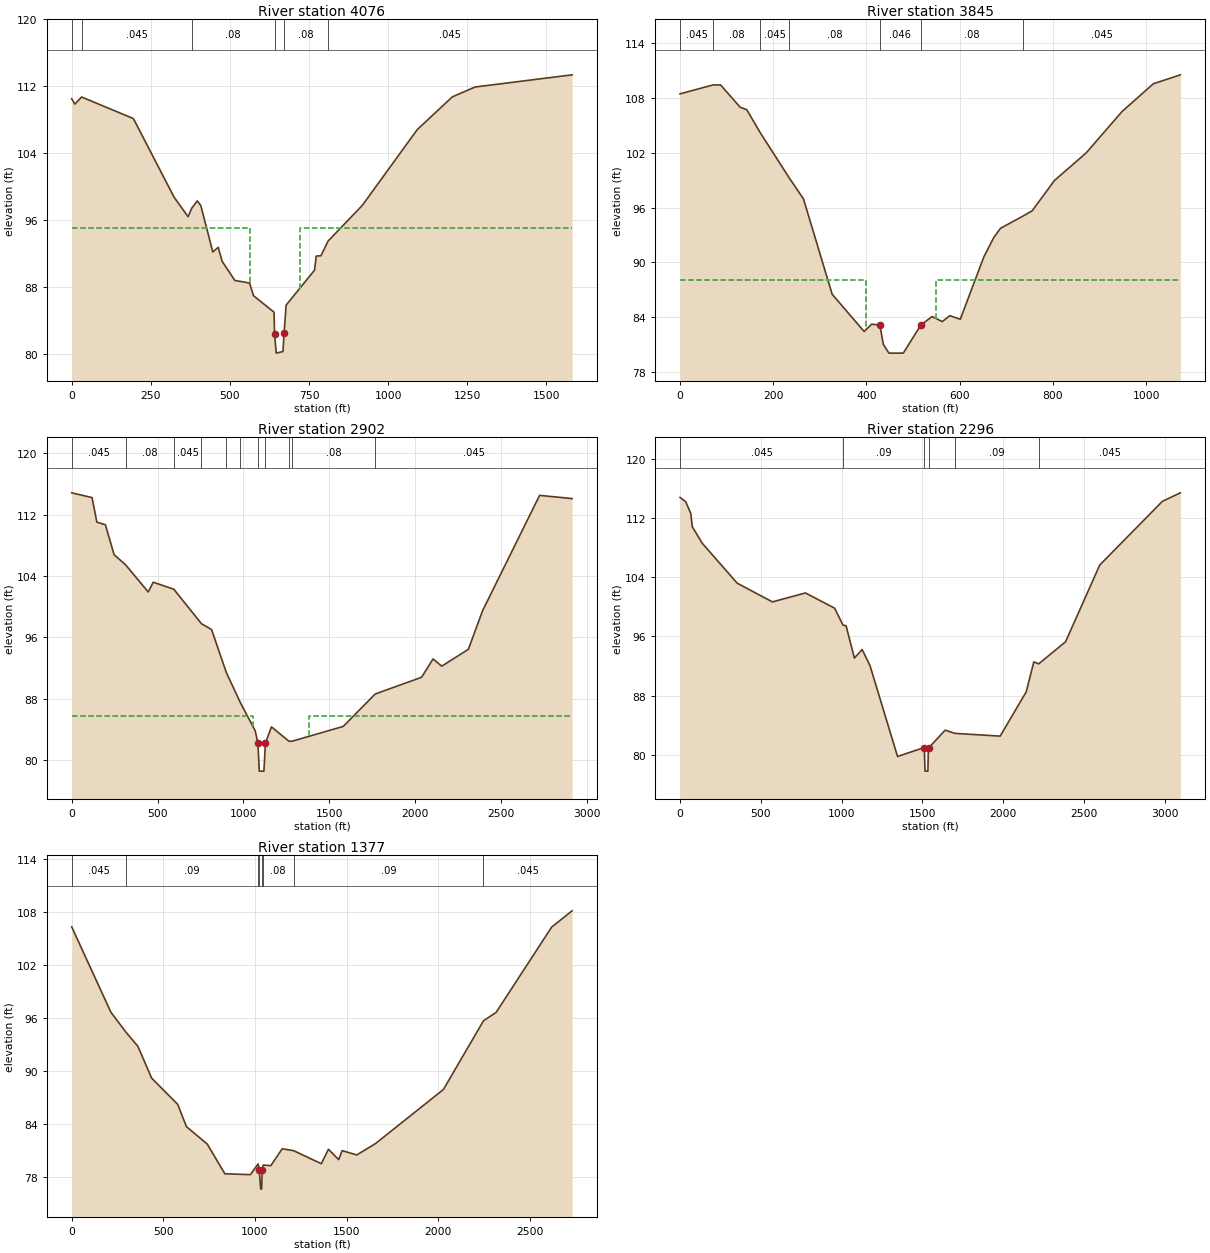
Type RM Length L Ch R = 1 ,4076    ,260.88,230.9,204.49
BEGIN DESCRIPTION:
Surveyed Section
END DESCRIPTION:
XS GIS Cut Line= 6
   2331608.87636  702527.6559131    2331357.3816     703092.7675
    2331341.2011      703142.537    2331304.0982     703231.1713
 2331181.8778423  703439.2189201 2330917.1240215  703946.8507596
#Sta/Elev= 30
       0  110.49   10.27  109.85   31.31   110.7  195.05  108.12   323.8   98.71
  367.85   96.39  379.41    97.4  397.04   98.28  408.26    97.7  446.04   92.17
     463   92.73  475.64   91.05  515.62   88.77  562.17   88.46 574.564  86.948
 639.565  84.973 641.146  82.408 646.523  80.079 667.716   80.27 671.353  82.508
 677.679  85.813 767.509  89.998  772.79   91.68  787.75   91.72  810.37   93.48
  918.26   97.73  1092.1   106.8 1202.85  110.71 1274.53  111.89 1581.52  113.35
#Mann= 6 ,-1 , 0
       0     .08       0   31.31    .045       0  379.41     .08       0
 641.146     .05       0 671.353     .08       0  810.37    .045       0
#XS Ineff= 4 ,-1
       0     562      95     562  631.15      85  681.35     720      85
     720 1581.52      95
Permanent Ineff=
       F       F       F       F
Bank Sta=641.146,671.353
XS Rating Curve= 0 ,0
Exp/Cntr=0.5,0.3

Type RM Length L Ch R = 1 ,3845    ,701.9,943.93,746.12
XS GIS Cut Line= 6
2331412.42770644702575.7182099822331357.28574693702636.987053871
2331228.62117483702882.0624293832331142.84479341703096.503382936
2331081.57594955703335.4518740482331014.18022124703562.146596387
#Sta/Elev= 30
       0  108.47   70.63109.4483   87.12  109.45  129.11     107  143.18  106.74
  171.85104.2363   234.199.26718  264.86   96.95  326.44   86.48  395.09   82.39
  411.23    83.2  428.74   83.09  436.23   80.98  448.16   80.02  478.97   80.02
  516.43   83.08  540.62   84.04  562.55   83.48  578.71   84.13  601.25   83.74
  651.86   90.59  673.36   92.73  687.59   93.72  734.7295.03228  755.48   95.64
  803.34   98.97  871.04  101.98  948.32  106.54 1015.31  109.58 1073.36  110.56
#Mann= 7 ,-1 , 0
       0    .045       0   70.63     .08       0  171.85    .045       0
   234.1     .08       0  428.74    .046       0  516.43     .08       0
  734.72    .045       0
#XS Ineff= 2 , 0
       0     400      88     550       0      88
Permanent Ineff=
       F       F
Bank Sta=428.74,516.43
XS Rating Curve= 0 ,0
Exp/Cntr=0.3,0.1

Type RM Length L Ch R = 1 ,2902    ,663.31,605.4,570.88
XS GIS Cut Line= 6
 2331055.3011311  701537.9981389 2330793.7408626  702314.6309363
 2330439.6284989  702849.8234858 2330322.9323791   703284.415932
 2330109.6601601  703783.3924444 2329976.8680238  704222.0088947
#Sta/Elev= 30
       0  114.85  118.56  114.23  146.52  111.03  196.28  110.69     247  106.78
  313.46  105.48   445.6  101.93  474.64   103.2  594.59  102.29  755.69   97.79
  814.16   97.04  900.19   91.44  982.63   87.48 1068.36   83.84 1084.33    82.2
 1092.13   78.58 1119.14   78.58 1127.76   82.23 1163.16   84.35 1264.49   82.48
 1283.49   82.48 1581.02   84.41 1766.87   88.63 2036.84   90.81 2103.81    93.2
 2154.36   92.26 2309.45   94.46 2392.01   99.48 2724.07  114.52 2913.22   114.1
#Mann= 11 ,-1 , 0
       0    .045       0  313.46     .08       0  594.59    .045       0
  755.69     .08       0  900.19    .045       0  982.63     .09       0
 1084.33    .042       0 1127.76     .07       0 1264.49    .042       0
 1283.49     .08       0 1766.87    .045       0
#XS Ineff= 2 ,-1
       0 1054.29   85.72    1380 2913.22   85.72
Permanent Ineff=
       F       F
Bank Sta=1084.33,1127.76
XS Rating Curve= 0 ,0
Exp/Cntr=0.3,0.1

Type RM Length L Ch R = 1 ,2296    ,861.79,919.43,789.96
XS GIS Cut Line= 6
2330552.09349449  700894.78094322330350.89328788701264.989323333
2330266.38920112701574.8376414782330230.17316392701981.262058765
2329855.94077969702934.9510380032329610.47652763 703820.23194699
#Sta/Elev= 30
       0  114.79   35.18  114.22   67.02  112.61   76.15  110.83  136.81  108.62
  353.94   103.2  571.64  100.67  776.12  101.88  956.52   99.82 1008.3997.52775
 1027.13   97.45 1078.86   93.08 1126.66   94.24 1175.52   92.05 1345.61   79.78
 1510.93   80.99 1515.64    77.8 1533.33    77.8 1536.26   80.82 1537.65   80.92
 1640.08   83.34 1700.1582.90398 1980.43   82.53 2141.41   88.51 2188.63   92.57
 2218.89 92.2979 2384.88   95.28  2596.2  105.65 2983.74  114.26 3095.12  115.41
#Mann= 6 ,-1 , 0
       0    .045       0 1008.39     .09       0 1510.93    .045       0
 1537.65     .08       0 1700.15     .09       0 2218.89    .045       0
Bank Sta=1510.93,1537.65
XS Rating Curve= 0 ,0
Exp/Cntr=0.3,0.1

Type RM Length L Ch R = 1 ,1377    ,1237.77,1376.71,1719.69
XS GIS Cut Line= 6
 2329788.1271646  701012.3786498 2329537.2670889  701465.8564791
 2329315.3524065  701948.2797017 2329209.2192975  702411.4059954
 2329160.9769752   702999.962327 2329257.4616197  703607.8155875
#Sta/Elev= 30
       0   106.3  213.66   96.64  296.52   94.36  360.98   92.78  436.28   89.17
  578.43    86.2  626.23   83.67  739.48   81.71  835.69   78.34   974.8   78.24
 1017.34   79.45  1023.5   78.74 1031.24   76.62 1036.15    76.6 1039.56   78.76
 1044.37   79.32 1086.69   79.26 1148.57   81.17 1210.38   80.96 1362.16   79.48
 1400.95   81.11 1456.78   79.94 1475.55   80.96 1555.76   80.47 1657.82   81.76
 2028.19   87.88 2246.56   95.65 2316.16   96.62 2618.93  106.27 2730.38  108.11
#Mann= 8 ,-1 , 0
       0    .045       0  296.52     .09       0 1017.34    .045       0
  1023.5    .045       0 1039.56    .045       0 1044.37     .08       0
 1210.38     .09       0 2246.56    .045       0
Bank Sta=1023.5,1039.56
XS Rating Curve= 0 ,0
Exp/Cntr=0.3,0.1

Chan Stop Cuts=-1
Use User Specified Reach Order=0
User Specified Reach Order=Hominy Swamp    ,Trib 1