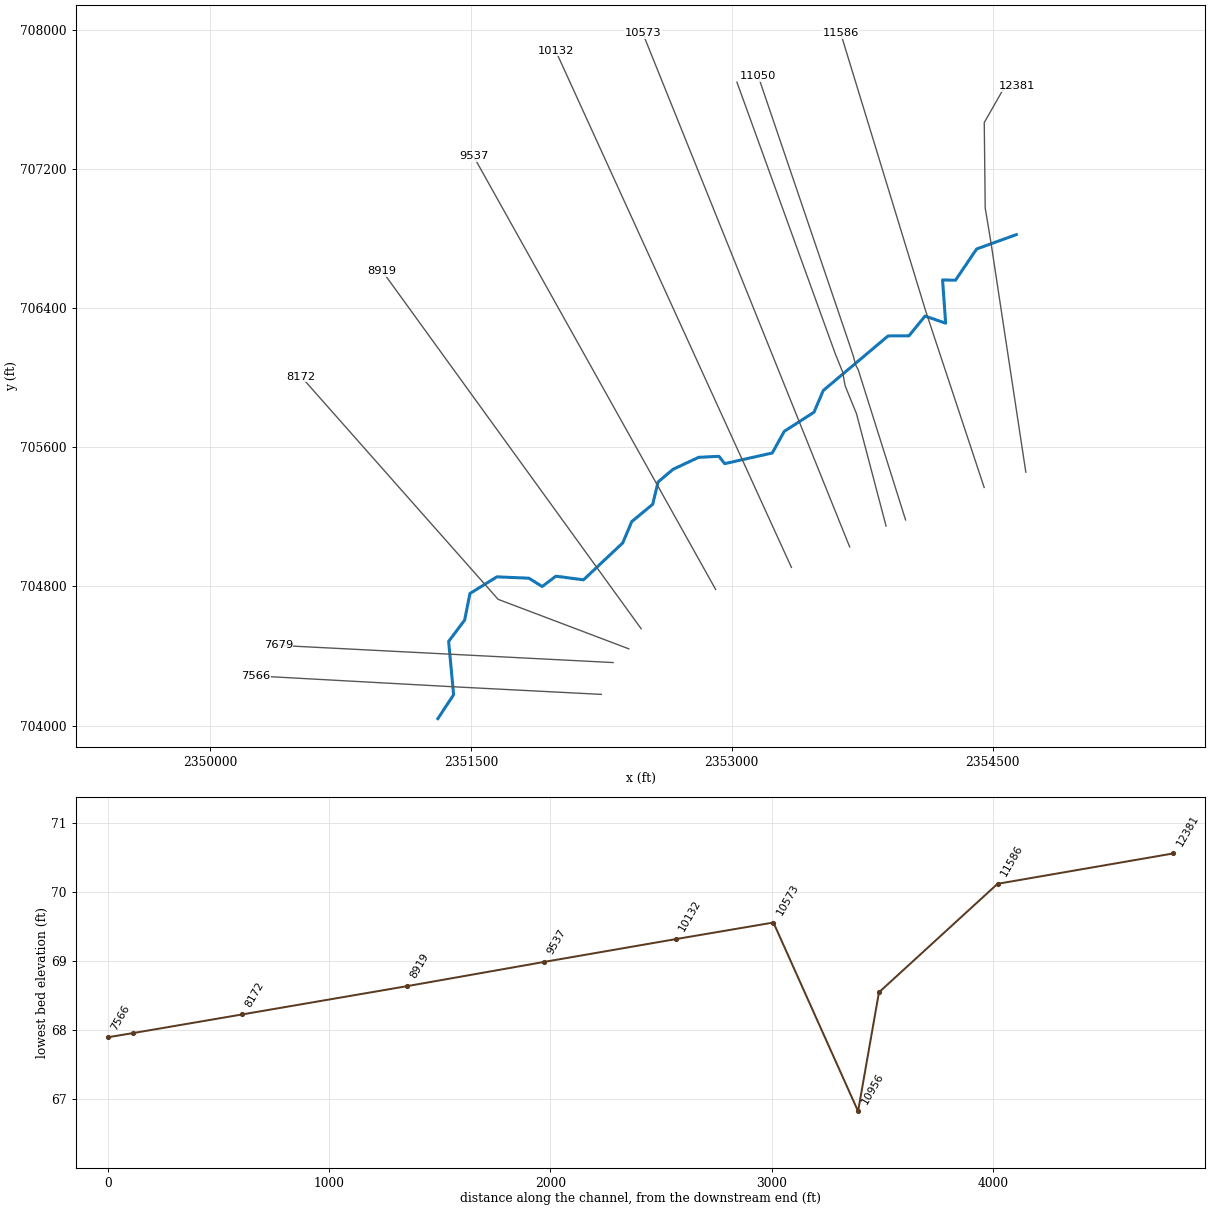
--- dtl_Whiteoak_Swamp.prj (project) ---

Proj Title=dtl_Whiteoak_Swamp
Current Plan=p01
Default Exp/Contr=0.3,0.1
English Units
Geom File=g01
Flow File=f01
Flow File=f02
Plan File=p01
Plan File=p02
Y Axis Title=Elevation
X Axis Title(PF)=Main Channel Distance
X Axis Title(XS)=Station
BEGIN DESCRIPTION:
END DESCRIPTION:
DSS Export Rating Curves= 0
DSS Export Rating Curve Sorted= 0
DSS Export Volume Flow Curves= 0
DXF OffsetX= 0
DXF OffsetY= 0
DXF ScaleX= 1
DXF ScaleY= 10

--- dtl_Whiteoak_Swamp.p01 (plan) ---

Plan Title=dtl_whiteoak_swamp
Program Version=4.00
Short Identifier=multiple
Geom File=g01
Flow File=f01
Subcritical Flow
K Sum by GR= 0
Std Step Tol= 0.01
Critical Tol= 0.01
Num of Std Step Trials= 20
Max Error Tol= 0.3
Flow Tol Ratio= 0.001
Split Flow NTrial= 30
Split Flow Tol= 0.02
Split Flow Ratio= 0.02
Log Output Level= 0
Friction Slope Method= 1
Unsteady Friction Slope Method= 2
Unsteady Bridges Friction Slope Method= 1
Parabolic Critical Depth
Global Vel Dist= 0 , 0 , 0
Global Log Level= 0
CheckData=True
Encroach Param=-1 ,10,10, 2
Encroach River=River
Encroach Reach=1
Encroach Node=12381
       1    1050    1600
Encroach Node=11586
       1     720    1240
Encroach Node=11050
       1     810     990
Encroach Node=10956
       1     800    1000
Encroach Node=10573
       1     610    1430
Encroach Node=10132
       1     620    1780
Encroach Node=9537
       1     530    1735
Encroach Node=8919
       1     300    1580
Encroach Node=8172
       4       1
Encroach Node=7679
       1     465    1370
Encroach Node=7566
       1   781.2  1601.2
Computation Interval=1HOUR
Output Interval=1HOUR
Run HTab= 0
Run UNet= 0
Run PostProcess= 0
Run WQNet= 0
UNET Theta= 1
UNET Theta Warmup= 1
UNET ZTol= 0.02
UNET ZSATol= 0.05
UNET MxIter= 20
UNET MaxInSteps= 0
UNET DtIC= 0
UNET DtMin= 0
UNET MaxCRTS= 20
UNET WFStab= 2
UNET SFStab= 1
UNET WFX= 1
UNET SFX= 1
UNET DSS MLevel= 4
UNET DZMax Abort= 100
UNET Convert EG Bridges=-1
UNET Use Existing IB Tables=-1
UNET Froude Reduction=False
UNET Froude Limit= 1
UNET Froude Power= 10
UNET Time Slicing=0,0, 5
Instantaneous Interval=1HOUR
Write IC File= 0
Echo Input=False
Echo Output=False
Write Detailed= 0
Detailed Automatic Start=False, 10
WQ ULTIMATE=-1
WQ Max Comp Step=1HOUR
WQ Output Interval=15MIN
WQ Output Selected Increments= 0
WQ Output face flow=0
WQ Output face velocity=0
WQ Output face area=0
WQ Output face dispersion=0
WQ Output cell volume=0
WQ Output cell surface area=0
WQ Output cell continuity=0
WQ Output face conc=0
WQ Output face dconc_dx=0
WQ Output face courant=0
WQ Output face peclet=0
WQ Output face adv mass=0
WQ Output face disp mass=0
WQ Output cell mass=0
WQ Output cell source sink temp=0
WQ Output cell source sink nsm=0
WQ Output MaxMinRange=-1
WQ Daily Max Min Mean=-1
WQ Daily Range=0
WQ Daily Time=0
WQ Create Restart=0
WQ Fixed Restart=0
WQ System Summary=False
Sorting and Armoring Iterations= 10
XS Update Threshold= 0.02
Hydraulics Update Threshold= 0.02
Energy Slope Method= 1
Volume Change Method= 0
XS Weighting Method= 0
Number of US Weighted Cross Sections= 1
Number of DS Weighted Cross Sections= 1
Upstream XS Weight=0.25
Main XS Weight=0.5
Downstream XS Weight=0.25
Number of DS XS's Weighted with US Boundary= 1
Upstream Boundary Weight= 1
Weight of XSs Associated with US Boundary= 0
Number of US XS's Weighted with DS Boundary= 1
Downstream Boundary Weight= 0.5
Weight of XSs Associated with DS Boundary= 0.5
Sediment Output Level= 4
Mass or Volume Output= 0
Output Increment Type= 1
Profile and TS Output Increment= 10
XS Output Flag= 0
XS Output Increment= 10
Disregard all LS=0
Disregard all Conn=0
Disregard all Breaches=0
Disregard all Pumps=0

--- dtl_Whiteoak_Swamp.p02 (plan) ---

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Plan Title=dtl_whiteoak_swamp_FUTURE
Short Identifier=Future
Geom File=g01
Flow File=f02
Encroach Param=-1 ,0,0, 0
BEGIN DESCRIPTION:
Future Condtions
END DESCRIPTION:
UNET Convert EG Bridges= 0

--- dtl_Whiteoak_Swamp.f01 (steady flow) ---

Flow Title=dtl_whiteoak_swamp
Program Version=4.00
Number of Profiles= 6
Profile Names=100yr,FW,10yr,25yr,50yr,500yr
River Rch & RM=River,1               ,12381
    5550    5550    2802    3781    4631    8103
River Rch & RM=River,1               ,11586
    6020    6020    3060    4110    5030    8770
River Rch & RM=River,1               ,7679
    6430    6430    3270    4400    5380    9340
River Rch & RM=River,1               ,7566
    6296    6296    3056    4114    5032    8771
Boundary for River Rch & Prof#=River,1               , 1
Up Type= 0
Dn Type= 1
Dn Known WS=79.45
Boundary for River Rch & Prof#=River,1               , 2
Up Type= 0
Dn Type= 1
Dn Known WS=80.19
Boundary for River Rch & Prof#=River,1               , 3
Up Type= 0
Dn Type= 1
Dn Known WS=77.09
Boundary for River Rch & Prof#=River,1               , 4
Up Type= 0
Dn Type= 1
Dn Known WS=78.46
Boundary for River Rch & Prof#=River,1               , 5
Up Type= 0
Dn Type= 1
Dn Known WS=79
Boundary for River Rch & Prof#=River,1               , 6
Up Type= 0
Dn Type= 1
Dn Known WS=80.36
DSS Import GetInterval= 0
DSS Import GetPeak= 0
DSS Import FillOption= 0

--- dtl_Whiteoak_Swamp.f02 (steady flow) ---

Flow Title=dtl_whiteoak_swamp_future
Program Version=4.00
Number of Profiles= 3
Profile Names=100-yr-10%,100-yr-20%,100-yr-35%
River Rch & RM=River,1               ,12381
    5732    7347    8977
River Rch & RM=River,1               ,11586.
    6200    7940    9700
River Rch & RM=River,1               ,7679.
    6590    8450   10300
River Rch & RM=River,1               ,7566
    6195    7940    9701
Boundary for River Rch & Prof#=River,1               , 1
Up Type= 0
Dn Type= 1
Dn Known WS=79.5
Boundary for River Rch & Prof#=River,1               , 2
Up Type= 0
Dn Type= 1
Dn Known WS=80.09
Boundary for River Rch & Prof#=River,1               , 3
Up Type= 0
Dn Type= 1
Dn Known WS=80.6
DSS Import GetInterval= 0
DSS Import GetPeak= 0
DSS Import FillOption= 0

--- dtl_Whiteoak_Swamp.g01 (geometry) ---

Geom Title=dtl_whiteoak_swamp
Program Version=4.00

River Reach=River           ,1
Reach XY= 30
 2354636.1125362  706822.7430169 2354408.0122977  706740.2373653
 2354286.6892922  706560.6755839 2354212.2750828  706562.2932841
 2354229.9243537  706313.3596016 2354111.5903206  706354.7284099
 2354019.2320509  706241.2047034 2353898.9738873  706240.2426381
 2353525.8816748  705926.1428479 2353473.2327414  705801.6999143
 2353301.8843943  705691.6157807 2353232.9621542  705567.1728471
 2352959.1877002  705505.9086336 2352926.6410867  705548.0277804
 2352809.8561798  705542.2842603 2352662.4391661  705473.3620202
 2352576.2863659  705400.6107667 2352545.6542592  705272.3388197
 2352425.0403389  705172.7844728 2352373.3486587  705050.2560458
 2352147.4368715  704837.7458053 2351988.5328178  704858.8053787
 2351910.0380443  704799.4556719 2351833.4577775  704847.3183387
  2351649.665137  704854.9763654 2351494.5900967  704759.2510318
   2351463.95799  704606.0904981 2351372.0616697  704483.5620712
 2351400.7792698  704177.2410038 2351310.2145628  704039.7566476

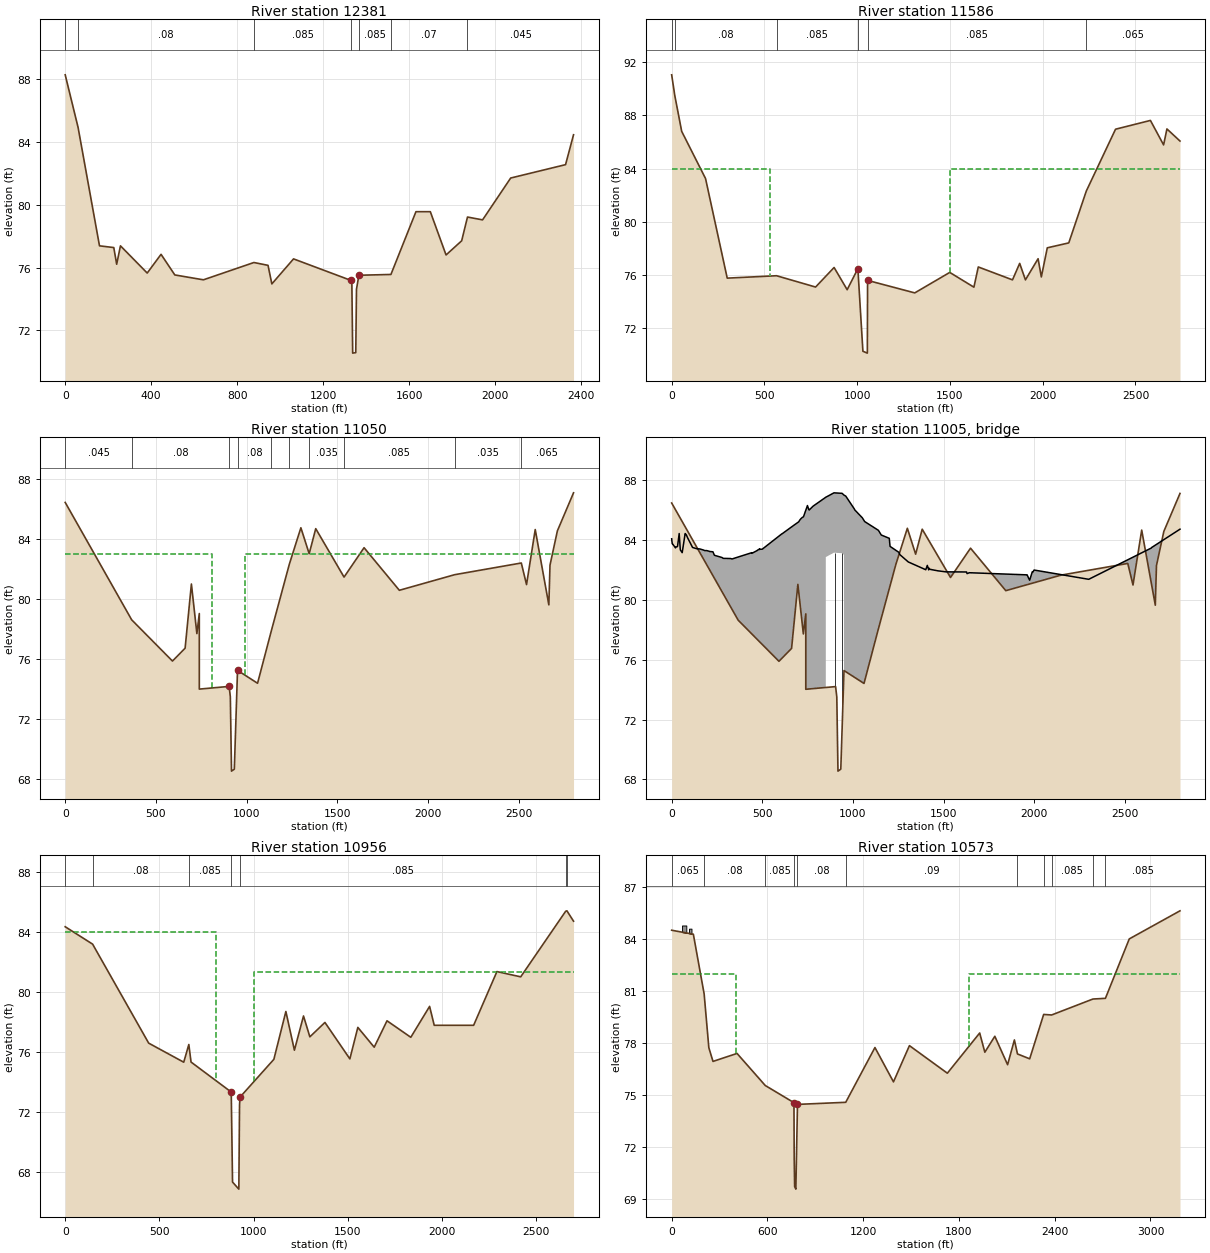
Type RM Length L Ch R = 1 ,12381   ,335.64,794.71,722.14
BEGIN DESCRIPTION:
12381.
END DESCRIPTION:
XS GIS Cut Line= 6
 2354690.9999967  705456.8125182 2354490.2499832  706779.1874731
 2354457.4999942   706975.812533 2354452.0000306  707467.3750296
 2354561.2500013  707658.5625359 2354640.0000344  707676.9374823
#Sta/Elev= 30
       0   88.25   59.87   84.91  159.53   77.38     226   77.27  239.45   76.21
  257.08   77.38  381.51   75.65  445.89   76.84     510   75.53  643.03   75.22
     878   76.32  943.63   76.14  961.35   74.96 1062.28   76.55 1329.92   75.18
 1333.62   74.98 1337.45   70.56 1351.79   70.59 1355.12   74.62 1366.27   75.51
 1515.35   75.56 1631.77   79.55 1698.66   79.55 1771.84    76.8 1844.52    77.7
 1871.54   79.21 1941.74   79.03 2072.53   81.69  2327.8   82.54 2364.91   84.44
#Mann= 7 ,-1 , 0
       0    .045       0   59.87     .08       0     878    .085       0
 1329.92     .05       0 1366.27    .085       0 1515.35     .07       0
 1871.54    .045       0
Bank Sta=1329.92,1366.27
XS Rating Curve= 0 ,0
Exp/Cntr=0.3,0.1

Type RM Length L Ch R = 1 ,11586   ,496.72,535.76,521.43
BEGIN DESCRIPTION:
11586.
END DESCRIPTION:
XS GIS Cut Line= 3
 2354451.5074761  705368.9254869 2354115.6611045  706382.1569131
 2353626.1223255  707981.6964118
#Sta/Elev= 30
       0   91.05   16.72    89.5   53.97    86.8  182.59   83.25  299.47   75.76
  565.58   75.94  775.75   75.09  875.58   76.56  946.01   74.89 1003.74   76.47
 1030.89   70.26 1054.81   70.12 1056.08   75.59 1310.47   74.65 1499.06   76.19
 1629.29   75.08 1652.84    76.6 1837.29   75.63 1876.05   76.87 1907.04   75.63
 1975.19   77.22 1992.73   75.85 2024.83   78.04 2140.67   78.41 2235.19   82.31
 2392.75   86.96 2580.81   87.62 2651.82   85.78 2669.81   86.98 2740.22   86.07
#Mann= 6 ,-1 , 0
       0    .045       0   16.72     .08       0  565.58    .085       0
 1003.74     .05       0 1056.08    .085       0 2235.19    .065       0
#XS Ineff= 2 , 0
       0     530      84    1500       0      84
Permanent Ineff=
       F       F
Bank Sta=1003.74,1056.08
XS Rating Curve= 0 ,0
Exp/Cntr=0.5,0.3

Type RM Length L Ch R = 1 ,11050   ,107.31,94.39,116.31
BEGIN DESCRIPTION:
11050.
END DESCRIPTION:
XS GIS Cut Line= 6
 2353999.6131918  705182.2112933 2353727.8065001     706044.2166
     2353711.965     706075.1311    2353699.7673     706122.3187
    2353676.8725     706191.4761 2353152.3008795   707733.828942
#Sta/Elev= 30
       0   86.47  366.62   78.64  591.56   75.89  661.27   76.75  695.94   81.03
  726.14   77.72  739.52   79.06 739.579   74.02 903.975    74.2 910.608   73.51
 917.091   68.55 932.629   68.68 950.259   75.271060.741   74.41 1137.23   77.93
 1236.22   82.36 1299.69   84.78 1345.42   83.05 1381.61   84.72 1537.74   81.49
 1648.11   83.45 1842.59   80.61 2147.51   81.65  2515.2   82.43 2544.04   80.99
 2592.01   84.66 2667.07   79.64 2673.49   82.29 2714.11   84.57 2803.22   87.11
#Mann= 10 ,-1 , 0
       0    .045       0  366.62     .08       0 903.975     .05       0
 950.259     .08       0 1137.23    .035       0 1236.22    .085       0
 1345.42    .035       0 1537.74    .085       0 2147.51    .035       0
  2515.2    .065       0
#XS Ineff= 2 , 0
       0     810      83     990       0      83
Permanent Ineff=
       F       F
Bank Sta=903.975,950.259
XS Rating Curve= 0 ,0
Exp/Cntr=0.5,0.3

Type RM Length L Ch R = 3 ,11005   ,,,
BEGIN DESCRIPTION:
11007.
END DESCRIPTION:
Bridge Culvert--1,0,-1,-1, 0
Deck Dist Width WeirC Skew NumUp NumDn MinLoCord MaxHiCord MaxSubmerge Is_Ogee
25,40,2.6,0, 90, 90, , , 0.95, 0, 1,1,,
       0    1.71    3.69    4.06   21.14   23.64   32.11   41.47   47.56   58.02
   74.08   74.14   74.34   80.37   83.76   86.79  115.09  139.01  155.11  174.52
  182.52  193.09  205.82  208.68   227.4  235.47  239.92  277.13  284.51  324.74
   332.9  441.59  442.95  472.33  472.74  484.41   485.3  486.35  499.05  607.63
  608.57  667.73  700.19  707.79  711.82  713.57     720  726.86   748.7  755.38
  758.16     780     850     850     895     940     950     950     960 1007.47
 1009.66 1051.38 1064.39    1140 1155.86    1200 1204.38  1253.3 1257.46 1304.83
 1401.16 1409.74 1417.28 1419.71  1423.6 1466.53 1511.34 1625.94 1629.05 1641.66
 1955.68 1959.96 1974.09 1988.56 1992.21 1998.64 2299.87  2644.7 2647.44 2803.22
   84.08   83.88   83.74   83.75   83.47   83.53   83.56   84.43   83.34   83.15
   84.41   84.42   84.43   84.35   84.26   84.17    83.5   83.41    83.4   83.33
   83.29   83.29   83.25   83.23   83.21   82.98   82.96   82.83   82.77   82.76
   82.73   83.15   83.11    83.3   83.31    83.4   83.36   83.38   83.38   84.41
   84.41   84.93   85.21   85.35   85.41   85.43  85.503   85.55    86.3   86.06
      86  86.261  86.857  86.857   87.15  87.116      87      87  86.931   86.07
   86.01   85.48   85.23  84.644   84.33   84.11   83.57   83.17   83.03   82.53
   82.01    82.3      82   82.11   82.04   81.94   81.87   81.86   81.75   81.81
   81.67   81.67   81.31   81.87   81.86   81.99   81.37   83.46    83.5   84.72
                                                                                
                                                                                
                                                                                
                                                                                
                                                                                
                          82.857   83.15  83.116      83
                                                                                
                                                                                
                                                                                
       0    1.71    3.69    4.06   21.14   23.64   32.11   41.47   47.56   58.02
   74.08   74.14   74.34   80.37   83.76   86.79  115.09  139.01  155.11  174.52
  182.52  193.09  205.82  208.68   227.4  235.47  239.92  277.13  284.51  324.74
   332.9  441.59  442.95  472.33  472.74  484.41   485.3  486.35  499.05  607.63
  608.57  667.73  700.19  707.79  711.82  713.57     720  726.86   748.7  755.38
  758.16     780     850     850     895     940     950     950     960 1007.47
 1009.66 1051.38 1064.39    1140 1155.86    1200 1204.38  1253.3 1257.46 1304.83
 1401.16 1409.74 1417.28 1419.71  1423.6 1466.53 1511.34 1625.94 1629.05 1641.66
 1955.68 1959.96 1974.09 1988.56 1992.21 1998.64 2299.87  2644.7 2647.44 2803.22
   84.08   83.88   83.74   83.75   83.47   83.53   83.56   84.43   83.34   83.15
   84.41   84.42   84.43   84.35   84.26   84.17    83.5   83.41    83.4   83.33
   83.29   83.29   83.25   83.23   83.21   82.98   82.96   82.83   82.77   82.76
   82.73   83.15   83.11    83.3   83.31    83.4   83.36   83.38   83.38   84.41
   84.41   84.93   85.21   85.35   85.41   85.43  85.503   85.55    86.3   86.06
      86  86.261  86.857  86.857   87.15  87.116      87      87  86.931   86.07
   86.01   85.48   85.23  84.644   84.33   84.11   83.57   83.17   83.03   82.53
   82.01    82.3      82   82.11   82.04   81.94   81.87   81.86   81.75   81.81
   81.67   81.67   81.31   81.87   81.86   81.99   81.37   83.46    83.5   84.72
                                                                                
                                                                                
                                                                                
                                                                                
                                                                                
                          82.857   83.15  83.116      83
                                                                                
                                                                                
                                                                                
Pier Skew, UpSta & Num, DnSta & Num=  ,900, 2 ,895, 2 , 0 , 0 , 0 ,,
       3       3
    67.3   83.15
       3       3
    12.5   83.15
Pier Skew, UpSta & Num, DnSta & Num=  ,940, 2 ,935, 2 , 0 , 0 , 0 ,,
       3       3
    67.3   83.15
       3       3
    12.5   83.15
BR Coef=-1 , 0 , 0 ,, 0 ,,,0.8,0,,0,
WSPro=,,,, 1 ,,,, 0 ,,,, 0 ,,,,-1 ,-1 ,-1 , 0 , 0 , 0 , 0 , 0
BC Design=,, 0 ,, 0 ,,,,,,
BC Use User HTab Curves=0
BC User HTab FreeFlow(D)= 0

Type RM Length L Ch R = 1 ,10956   ,271.43,382.46,376.6
BEGIN DESCRIPTION:
10956.
END DESCRIPTION:
XS GIS Cut Line= 6
 2353887.3574311  705147.1669024    2353717.4031     705792.8436
    2353651.5589      705954.473    2353638.1175     706031.6351
    2353595.1597     706138.0575 2353029.8174871  707699.4752016
#Sta/Elev= 30
       0   84.32  145.37   83.16  442.96   76.56  628.93   75.29  655.91   76.47
 667.667    75.3 880.911    73.3 887.803    67.3  921.23   66.83 924.908    72.4
 927.353   72.961107.042   75.48 1170.81   78.67 1216.09   76.09 1264.33   78.37
 1298.06   76.98 1378.07   77.94 1510.29   75.51 1552.63   77.61 1639.51   76.29
 1707.39   78.05 1833.62   76.95 1933.36   79.01 1957.89   77.75 2166.99   77.75
 2290.53   81.33 2416.78   80.98 2655.21   85.35 2661.95   85.38 2697.01   84.69
#Mann= 7 ,-1 , 0
       0    .065       0  145.37     .08       0  655.91    .085       0
 880.911     .05       0 927.353    .085       0 2655.21     .07       0
 2661.95    .085       0
#XS Ineff= 2 , 0
       0     800      84    1000       0    81.3
Permanent Ineff=
       F       F
Bank Sta=880.911,927.353
XS Rating Curve= 0 ,0
Exp/Cntr=0.5,0.3

Type RM Length L Ch R = 1 ,10573   ,366.77,441.11,445.81
BEGIN DESCRIPTION:
10573.
END DESCRIPTION:
XS GIS Cut Line= 2
  2353678.158963  705027.0479085 2352488.1214131  707981.4908712
#Sta/Elev= 30
       0    84.5  135.83   84.27  203.53   80.82  232.91   77.72  258.92   76.93
  409.55   77.39  586.38   75.54   766.2   74.55  767.81   71.33   770.5   69.71
  778.04   69.56  788.31   74.45 1090.58   74.57  1273.7   77.73 1389.85   75.75
 1489.78   77.84 1727.43   76.25 1929.98   78.57 1962.29   77.46 2024.79   78.38
 2104.93   76.74 2147.49   78.17 2166.83   77.36  2243.3   77.08 2330.86   79.64
 2380.87   79.61  2639.5   80.53 2717.85   80.57 2867.37      84 3185.11   85.62
#Mann= 11 ,-1 , 0
       0    .065       0  203.53     .08       0  586.38    .085       0
   766.2     .05       0  788.31     .08       0 1090.58     .09       0
 2166.83    .032       0 2330.86    .045       0 2380.87    .085       0
  2639.5     .07       0 2717.85    .085       0
#XS Ineff= 2 , 0
       0     400      82    1860       0      82
Permanent Ineff=
       F       F
#Block Obstruct= 2 ,-1
   64.94   91.7484.77488  108.58   124.284.59179
Bank Sta=766.2,788.31
XS Rating Curve= 0 ,0
Exp/Cntr=0.3,0.1

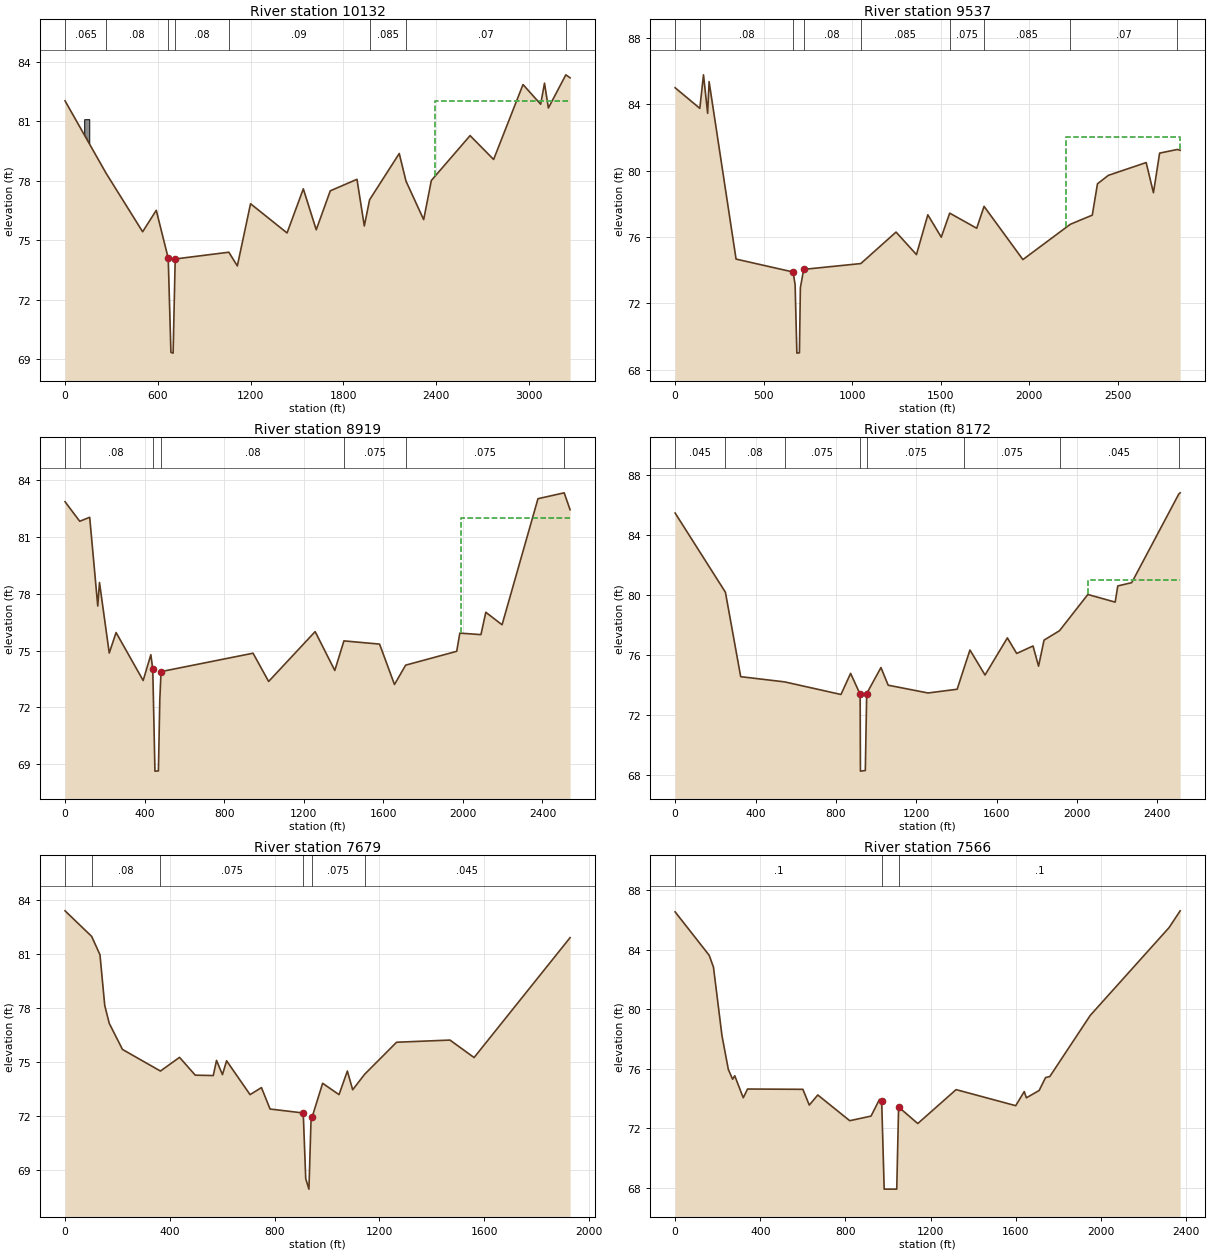
Type RM Length L Ch R = 1 ,10132   ,469.26,594.87,608.45
BEGIN DESCRIPTION:
10132.
END DESCRIPTION:
XS GIS Cut Line= 2
 2353343.1791098  704909.1801129 2351986.8806944  707881.2427275
#Sta/Elev= 30
       0   82.02  265.27   78.38  501.95   75.43  590.14   76.51  667.43    74.1
  684.92   69.36  699.13   69.32  712.59   74.06 1059.46    74.4 1114.45   73.71
 1199.95   76.84 1436.09   75.37  1541.3   77.59 1624.96   75.53 1715.65   77.49
 1888.42   78.07 1935.92   75.72 1969.95   77.04 2161.87   79.37 2205.49   77.98
 2319.84   76.04  2369.4   78.01 2620.01   80.27 2772.29   79.07  2962.4   82.84
 3076.71   81.85 3101.47   82.91 3126.56   81.66 3239.47   83.33 3266.91   83.18
#Mann= 8 ,-1 , 0
       0    .065       0  265.27     .08       0  667.43     .05       0
  712.59     .08       0 1059.46     .09       0 1969.95    .085       0
 2205.49     .07       0 3239.47    .075       0
#XS Ineff= 2 , 0
       0                    2396       0      82
Permanent Ineff=
       F       F
#Block Obstruct= 1 ,-1
  123.79  156.6981.09598
Bank Sta=667.43,712.59
XS Rating Curve= 0 ,0
Exp/Cntr=0.3,0.1

Type RM Length L Ch R = 1 ,9537    ,499.06,618.53,703.32
BEGIN DESCRIPTION:
9537.
END DESCRIPTION:
XS GIS Cut Line= 2
 2352907.2645464  704782.8479429 2351515.1247238  707273.8569154
#Sta/Elev= 30
       0   84.99  139.54   83.75  160.31   85.77  183.78   83.45  191.93   85.36
  344.35   74.66  666.95   73.88  678.02    73.1  687.89   68.99  702.43   69.01
  707.71   72.93  726.42   74.04 1049.28   74.39 1248.27   76.29 1363.66   74.93
 1427.86   77.33 1503.85   75.98 1551.52   77.43 1704.09   76.52 1745.56   77.84
 1965.07   74.63 2233.25   76.76  2357.1   77.31 2386.46    79.2 2447.96   79.71
 2661.53   80.48 2702.66   78.66 2737.56   81.05  2838.5   81.27 2853.63   81.22
#Mann= 9 ,-1 , 0
       0    .045       0  139.54     .08       0  666.95     .05       0
  726.42     .08       0 1049.28    .085       0 1551.52    .075       0
 1745.56    .085       0 2233.25     .07       0  2838.5    .075       0
#XS Ineff= 2 , 0
       0                    2210       0      82
Permanent Ineff=
       F       F
Bank Sta=666.95,726.42
XS Rating Curve= 0 ,0
Exp/Cntr=0.3,0.1

Type RM Length L Ch R = 1 ,8919    ,206.83,746.39,685.62
BEGIN DESCRIPTION:
8919.
END DESCRIPTION:
XS GIS Cut Line= 2
 2352478.9596036  704556.8772345 2350990.2962066  706613.3985566
#Sta/Elev= 30
       0   82.85   73.88   81.82  123.95   82.03  164.51   77.35  173.14   78.59
  222.23   74.87   256.6   75.95  392.72   73.42   431.3   74.78  440.99   74.03
  451.93   68.64  469.36   68.65  476.39   72.41  482.62   73.89  945.09   74.86
 1023.43   73.37 1257.26      76 1356.07   73.95 1401.91   75.51 1581.15   75.34
 1656.01   73.21 1712.15   74.23 1968.89   74.96 1984.52   75.92 2090.73   75.84
 2115.14   77.02 2196.88   76.36  2377.4   83.01 2509.08   83.32 2538.78   82.43
#Mann= 7 ,-1 , 0
       0    .045       0   73.88     .08       0  440.99     .05       0
  482.62     .08       0 1401.91    .075       0 1712.15    .075       0
 2509.08    .085       0
#XS Ineff= 2 , 0
       0                    1990       0      82
Permanent Ineff=
       F       F
Bank Sta=440.99,482.62
XS Rating Curve= 0 ,0
Exp/Cntr=0.3,0.1

Type RM Length L Ch R = 1 ,8172    ,153.03,493.34,1127.36
BEGIN DESCRIPTION:
8173.
END DESCRIPTION:
XS GIS Cut Line= 3
 2352407.9676895  704441.0787315 2351656.5825869  704725.6943006
 2350523.8126217  706006.4643618
#Sta/Elev= 30
       0   85.47  250.33   80.18  326.31   74.54  545.39   74.19  825.26   73.35
  873.34   74.76  920.15   73.38  920.88   73.05  922.19   68.23  946.54   68.27
  953.33   73.41 1024.31   75.15 1060.26   73.97 1258.57   73.45 1403.54    73.7
 1439.38   75.18 1467.24   76.32 1542.29   74.65  1653.5   77.13 1699.79   76.09
 1781.05   76.59 1808.66   75.24 1835.94   76.98 1912.89   77.61 2054.02   80.03
 2189.88   79.52 2202.98    80.6  2272.3   80.82 2506.53   86.74 2513.32   86.82
#Mann= 8 ,-1 , 0
       0    .045       0  250.33     .08       0  545.39    .075       0
  920.15     .05       0  953.33    .075       0 1439.38    .075       0
 1912.89    .045       0 2506.53    .065       0
#XS Ineff= 2 , 0
       0                    2054       0      81
Permanent Ineff=
       F       F
Bank Sta=920.15,953.33
XS Rating Curve= 0 ,0
Exp/Cntr=0.3,0.1

Type RM Length L Ch R = 1 ,7679    ,113.1,113.1,113.1
BEGIN DESCRIPTION:
7679.
END DESCRIPTION:
XS GIS Cut Line= 2
 2352317.7500194  704362.1250164 2350392.0000366  704461.0000017
#Sta/Elev= 30
       0   83.42  101.62      82  133.37   80.98  151.62   78.16  168.77   77.17
  219.31   75.72  364.25   74.52  437.11   75.28  497.23   74.29  565.92   74.27
  578.37   75.11  601.04   74.32  616.84   75.09  706.45   73.21  749.93    73.6
  782.78   72.41  909.47   72.19  918.97   68.54  931.22   67.96  938.96   71.68
  943.51   71.97  983.52   73.84 1046.09   73.21 1077.93   74.52 1098.21   73.48
 1143.86   74.34 1265.88   76.12 1469.73   76.24 1561.78   75.27 1928.29   81.93
#Mann= 6 ,-1 , 0
       0    .045       0  101.62     .08       0  364.25    .075       0
  909.47     .05       0  943.51    .075       0 1143.86    .045       0
Bank Sta=909.47,943.51
XS Rating Curve= 0 ,0
Exp/Cntr=0.3,0.1

Type RM Length L Ch R = 1 ,7566    ,764.1,764.1,764.1
BEGIN DESCRIPTION:
7565.9
END DESCRIPTION:
XS GIS Cut Line= 4
2352249.85576394704179.111552567 2351398.2500251  704222.9374868
  2350340.749975  704281.12500862350260.87080482704285.520252795
#Sta/Elev= 30
       0   86.54     160   83.62     180   82.83     220   78.22     250   75.94
     270   75.29     280   75.52     320   74.04     340   74.63     600   74.61
     630   73.55     670   74.23     820    72.5     920   72.81     960   73.94
     970   73.83   981.8    67.9 1040.75    67.9  1049.5   73.42  1139.5   72.31
  1319.5   74.59  1599.5   73.51  1639.5   74.46  1649.5   74.04  1709.5   74.53
  1739.5    75.4  1759.5   75.47  1949.5   79.58  2319.5   85.48  2371.7   86.61
#Mann= 3 ,-1 , 0
       0      .1       0     970     .04       0  1049.5      .1       0
Bank Sta=970,1049.5
XS Rating Curve= 0 ,0
Exp/Cntr=0.3,0.1
Stream Node=River           ,1               , 0 , 0 ,Upstream end
Stream Node=River           ,1               , 0 , 1 ,Downstream end

Chan Stop Cuts=-1
Use User Specified Reach Order=0