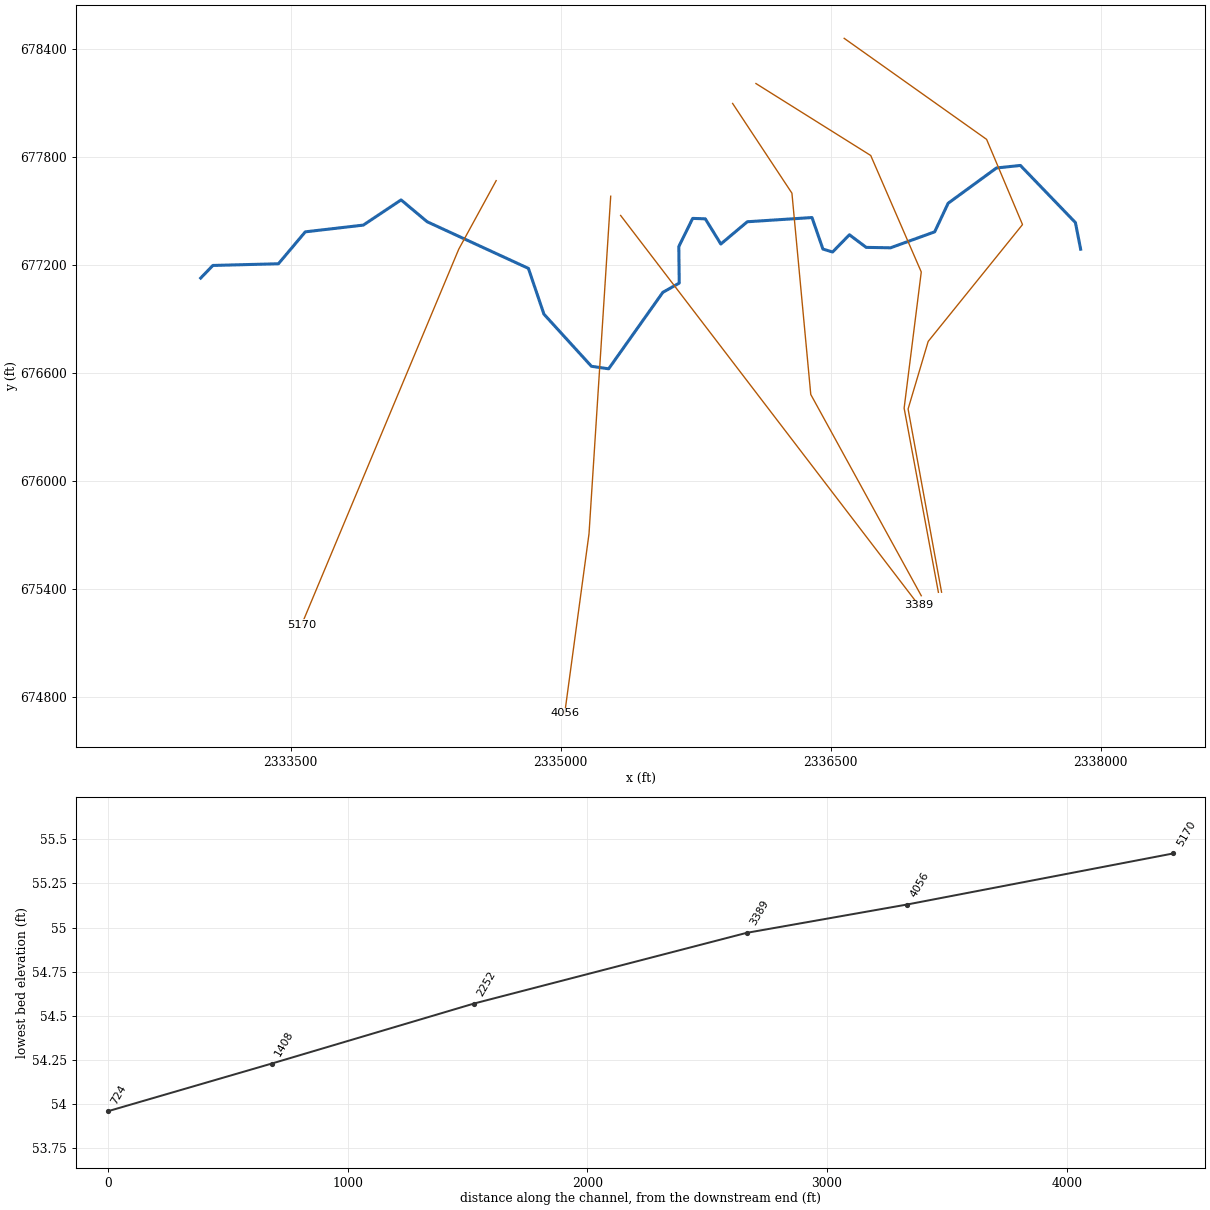
--- dtl_black_crk_dwnst.prj (project) ---

Proj Title=dtl_black_crk_dwnstrm
Current Plan=p01
Default Exp/Contr=0.3,0.1
English Units
Geom File=g01
Flow File=f01
Flow File=f02
Plan File=p01
Plan File=p02
Y Axis Title=Elevation
X Axis Title(PF)=Main Channel Distance
X Axis Title(XS)=Station
BEGIN DESCRIPTION:
END DESCRIPTION:
DSS Export Rating Curves= 0
DSS Export Rating Curve Sorted= 0
DSS Export Volume Flow Curves= 0
DXF OffsetX= 0
DXF OffsetY= 0
DXF ScaleX= 1
DXF ScaleY= 10

--- dtl_black_crk_dwnst.p01 (plan) ---

Plan Title=dtl_black_crk_dwnstrm
Program Version=4.00
Short Identifier=dtl_black_cr
Geom File=g01
Flow File=f01
Subcritical Flow
K Sum by GR= 0
Std Step Tol= 0.01
Critical Tol= 0.01
Num of Std Step Trials= 20
Max Error Tol= 0.3
Flow Tol Ratio= 0.001
Split Flow NTrial= 30
Split Flow Tol= 0.02
Split Flow Ratio= 0.02
Log Output Level= 0
Friction Slope Method= 1
Unsteady Friction Slope Method= 2
Unsteady Bridges Friction Slope Method= 1
Parabolic Critical Depth
Global Vel Dist= 0 , 0 , 0
Global Log Level= 0
CheckData=True
Encroach Param=-1 ,10,10, 2
Encroach River=Black Creek
Encroach Reach=dwnstrm
Encroach Node=5170
       1  239.77 1010.59
Encroach Node=4056
       1     458    1700
Encroach Node=3389
       4       1
Encroach Node=2252
       1     440    1918
Encroach Node=1408
       4       1
Encroach Node=724
       4       1
Computation Interval=1HOUR
Output Interval=1HOUR
Run HTab= 0
Run UNet= 0
Run PostProcess= 0
Run WQNet= 0
UNET Theta= 1
UNET Theta Warmup= 1
UNET ZTol= 0.02
UNET ZSATol= 0.05
UNET MxIter= 20
UNET MaxInSteps= 0
UNET DtIC= 0
UNET DtMin= 0
UNET MaxCRTS= 20
UNET WFStab= 2
UNET SFStab= 1
UNET WFX= 1
UNET SFX= 1
UNET DSS MLevel= 4
UNET DZMax Abort= 100
UNET Convert EG Bridges= 0
UNET Use Existing IB Tables=-1
UNET Froude Reduction=False
UNET Froude Limit= 1
UNET Froude Power= 10
UNET Time Slicing=0,0, 5
Instantaneous Interval=1HOUR
Write IC File= 0
Echo Input=False
Echo Output=False
Write Detailed= 0
Detailed Automatic Start=False, 10
WQ ULTIMATE=-1
WQ Max Comp Step=1HOUR
WQ Output Interval=15MIN
WQ Output Selected Increments= 0
WQ Output face flow=0
WQ Output face velocity=0
WQ Output face area=0
WQ Output face dispersion=0
WQ Output cell volume=0
WQ Output cell surface area=0
WQ Output cell continuity=0
WQ Output face conc=0
WQ Output face dconc_dx=0
WQ Output face courant=0
WQ Output face peclet=0
WQ Output face adv mass=0
WQ Output face disp mass=0
WQ Output cell mass=0
WQ Output cell source sink temp=0
WQ Output cell source sink nsm=0
WQ Output MaxMinRange=-1
WQ Daily Max Min Mean=-1
WQ Daily Range=0
WQ Daily Time=0
WQ Create Restart=0
WQ Fixed Restart=0
WQ System Summary=False
Sorting and Armoring Iterations= 10
XS Update Threshold= 0.02
Hydraulics Update Threshold= 0.02
Energy Slope Method= 1
Volume Change Method= 0
XS Weighting Method= 0
Number of US Weighted Cross Sections= 1
Number of DS Weighted Cross Sections= 1
Upstream XS Weight=0.25
Main XS Weight=0.5
Downstream XS Weight=0.25
Number of DS XS's Weighted with US Boundary= 1
Upstream Boundary Weight= 1
Weight of XSs Associated with US Boundary= 0
Number of US XS's Weighted with DS Boundary= 1
Downstream Boundary Weight= 0.5
Weight of XSs Associated with DS Boundary= 0.5
Sediment Output Level= 4
Mass or Volume Output= 0
Output Increment Type= 1
Profile and TS Output Increment= 10
XS Output Flag= 0
XS Output Increment= 10
Disregard all LS=0
Disregard all Conn=0
Disregard all Breaches=0
Disregard all Pumps=0

--- dtl_black_crk_dwnst.p02 (plan) ---

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Plan Title=dtl_black_crk_dwnstrm_future
Short Identifier=future
Geom File=g01
Flow File=f02
BEGIN DESCRIPTION:
Future Conditons based on 10%, 20% and 35% impervious
END DESCRIPTION:

--- dtl_black_crk_dwnst.f01 (steady flow) ---

Flow Title=dtl_black_crk_dwnstrm
Program Version=4.00
Number of Profiles= 6
Profile Names=100-yr,FW,10-yr,25-yr,50-yr,500-yr
River Rch & RM=Black Creek,dwnstrm         ,5170
   13344   13344    7097    9351   11292   18945
River Rch & RM=Black Creek,dwnstrm         ,4056
   13360   13360    7110    9360   11310   18970
Boundary for River Rch & Prof#=Black Creek,dwnstrm         , 1
Up Type= 0
Dn Type= 3
Dn Slope=0.00066
Boundary for River Rch & Prof#=Black Creek,dwnstrm         , 2
Up Type= 0
Dn Type= 3
Dn Slope=0.00066
Boundary for River Rch & Prof#=Black Creek,dwnstrm         , 3
Up Type= 0
Dn Type= 3
Dn Slope=0.00066
Boundary for River Rch & Prof#=Black Creek,dwnstrm         , 4
Up Type= 0
Dn Type= 3
Dn Slope=0.00066
Boundary for River Rch & Prof#=Black Creek,dwnstrm         , 5
Up Type= 0
Dn Type= 3
Dn Slope=0.00066
Boundary for River Rch & Prof#=Black Creek,dwnstrm         , 6
Up Type= 0
Dn Type= 3
Dn Slope=0.00066
DSS Import GetInterval= 0
DSS Import GetPeak= 0
DSS Import FillOption= 0

--- dtl_black_crk_dwnst.f02 (steady flow) ---

Flow Title=dtl_black_crk_dwnstrm_future
Program Version=4.00
Number of Profiles= 3
Profile Names=100-yr 10%,100-yr 20%,100-yr 35%
River Rch & RM=Black Creek,dwnstrm         ,5170
   13200   16900   20600
River Rch & RM=Black Creek,dwnstrm         ,4056
   13200   16900   20700
Boundary for River Rch & Prof#=Black Creek,dwnstrm         , 1
Up Type= 0
Dn Type= 3
Dn Slope=0.00066
Boundary for River Rch & Prof#=Black Creek,dwnstrm         , 2
Up Type= 0
Dn Type= 3
Dn Slope=0.00066
Boundary for River Rch & Prof#=Black Creek,dwnstrm         , 3
Up Type= 0
Dn Type= 3
Dn Slope=0.00066
DSS Import GetInterval= 0
DSS Import GetPeak= 0
DSS Import FillOption= 0

--- dtl_black_crk_dwnst.g01 (geometry) ---

Geom Title=dtl_black_crk_dwnstrm
Program Version=4.00

River Reach=Black Creek     ,dwnstrm
Reach XY= 30
2332999.68962538677129.7411871852333067.38883671677199.774854004
 2333431.5639042677209.1126762632333580.96906009677386.531298906
2333903.12392755677423.8825878652334113.22492805677563.949921548
2334257.96117288677442.5582323672334820.56496309677183.433665067
2334906.93981886676928.9780089262335170.73329729676639.505519345
2335266.44597526676625.4987859582335567.59074268677050.369698092
2335658.63450956677101.7277204392335656.30005398677304.825354263
 2335733.3370875677461.2338768542335803.37075435 677458.89942129
2335889.74561012677318.832087636 2336036.8163105677442.558232367
 2336396.3224669677465.9027879832336457.01831144677290.818620905
2336510.71078938677274.4774319532336604.08901182677370.190109983
2336697.46723425677300.1564431342336832.86565682677297.821987569
2337077.98349071677386.5312989062337152.68606868677545.274277061
 2337421.1484582677741.3685441912337554.21242519677755.375277564
2337860.02610372677437.8893212532337888.96488766677290.210466906

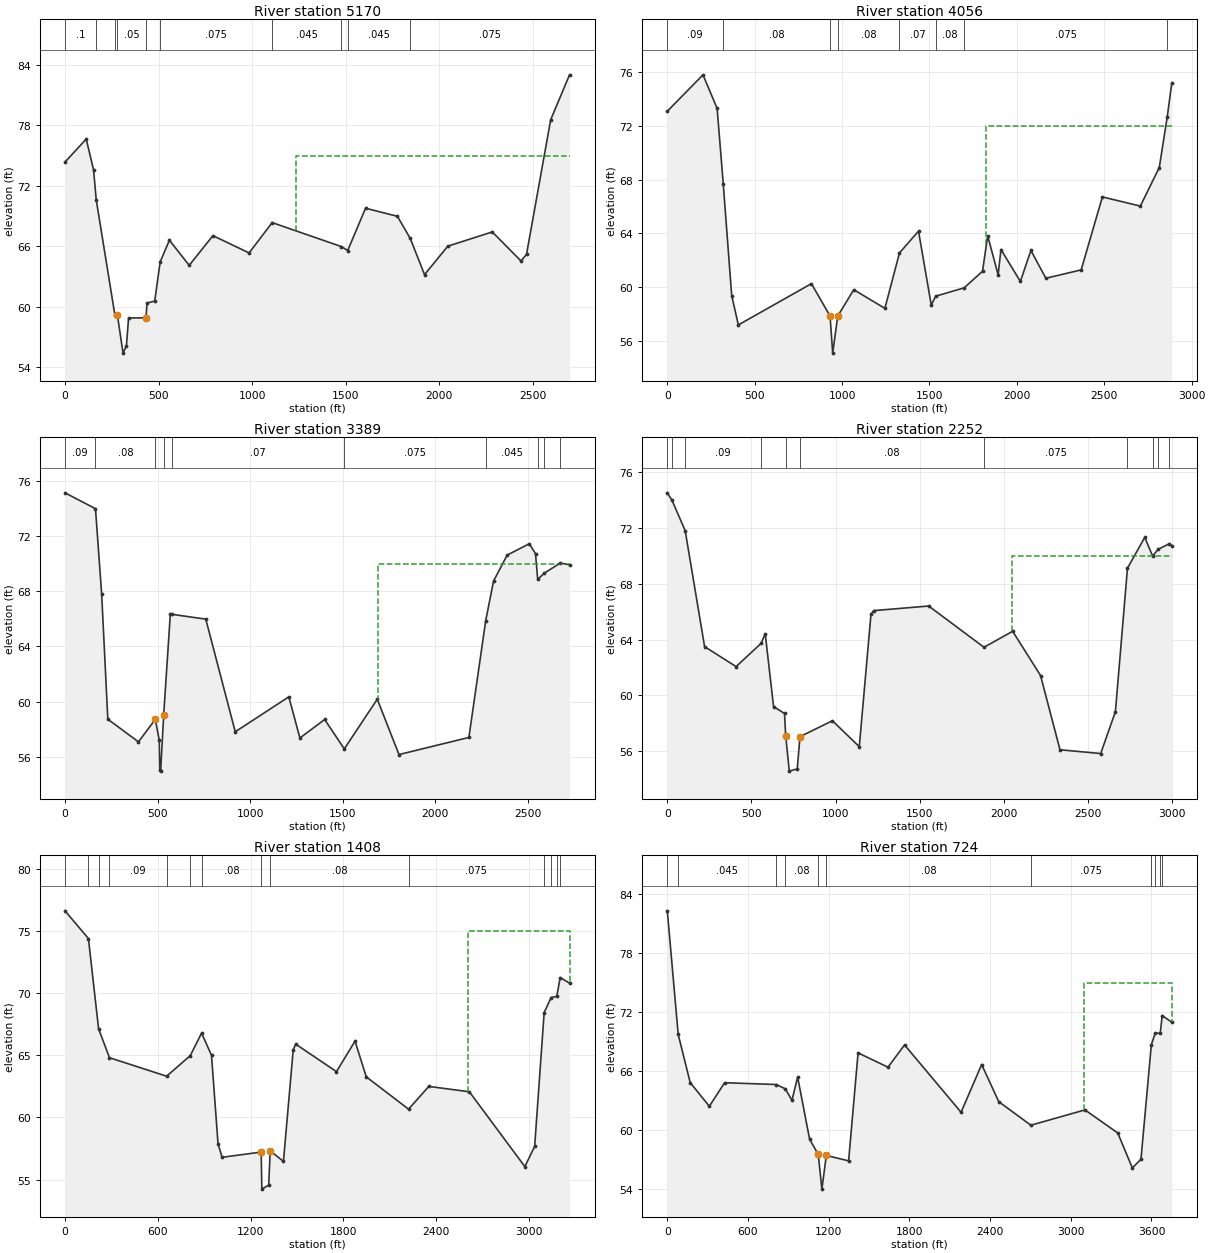
Type RM Length L Ch R = 1 ,5170    ,809.53,1113.65,1217.11
XS GIS Cut Line= 3
2334641.49996589677671.0625219792334433.49998288677290.062519595
2333560.00003263675202.499980956
#Sta/Elev= 30
       0   74.36  113.24   76.63  152.55   73.59  166.95   70.61  266.74   59.18
  280.28   59.16  310.15   55.42  328.27   56.14  339.75    58.9  432.79   58.92
  438.57   60.39  479.33   60.57  508.66   64.46  558.03   66.61  663.83   64.12
  790.72   67.06  984.03   65.35  1107.468.35486 1477.16   65.98 1511.14   65.59
 1606.61   69.78 1776.98   68.98 1845.57   66.78 1921.79    63.2 2046.61   66.02
 2283.93   67.43  2437.7   64.55 2467.07   65.21 2596.18   78.54 2697.02      83
#Mann= 10 ,-1 , 0
       0      .1       0  166.95     .08       0  266.74     .05       0
  280.28     .05       0  432.79     .08       0  508.66    .075       0
  1107.4    .045       0 1477.16    .075       0 1511.14    .045       0
 1845.57    .075       0
#XS Ineff= 2 , 0
       0                 1235.32       0      75
Permanent Ineff=
       F       F
Bank Sta=280.28,432.79
XS Rating Curve= 0 ,0
Exp/Cntr=0.3,0.1

Type RM Length L Ch R = 1 ,4056    ,330.46,667.4,1246.55
XS GIS Cut Line= 3
2335277.84951535677584.4468896392335157.31545249675708.936871216
2335022.31730206674710.914830565
#Sta/Elev= 30
       0   73.06  204.19   75.76  285.12   73.27  320.11   67.67  368.43   59.39
  406.52   57.22  824.47   60.28  931.18   57.88  946.29   55.13  975.23   57.88
 1066.95   59.83 1244.87   58.45 1328.36   62.56  1437.3   64.17 1510.23   58.69
 1535.32   59.35 1698.41   59.97 1803.51    61.2 1832.97   63.83 1892.74   60.94
 1909.08   62.81 2019.94   60.44 2080.27   62.74 2165.88   60.68 2367.89    61.3
 2489.32   66.71 2706.38   66.03 2814.81   68.89 2860.51   72.66 2886.49   75.17
#Mann= 8 ,-1 , 0
       0     .09       0  320.11     .08       0  931.18     .05       0
  975.23     .08       0 1328.36     .07       0 1535.32     .08       0
 1698.41    .075       0 2860.51    .035       0
#XS Ineff= 2 , 0
       0                    1825       0      72
Permanent Ineff=
       F       F
Bank Sta=931.18,975.23
XS Rating Curve= 0 ,0
Exp/Cntr=0.3,0.1

Type RM Length L Ch R = 1 ,3389    ,881.73,1136.52,215.81
XS GIS Cut Line= 2
2335332.98960082677477.5886403472336989.15139844675312.204680845
#Sta/Elev= 30
       0   75.13  164.66   73.98  198.04   67.78  231.33   58.73  397.02   57.09
  487.82   58.72  509.23   57.21  511.97   55.08  516.56   54.97  533.23   59.06
  569.22   66.38  577.39   66.33  760.56   65.98  919.82   57.82 1209.22   60.35
 1269.16   57.37 1403.05   58.71 1508.91   56.58 1687.24   60.18 1804.51   56.17
  2182.3   57.41 2273.32   65.88 2315.59   68.74 2388.98   70.62 2508.82   71.44
 2542.21   70.72 2554.11   68.86 2590.64   69.32 2677.0670.04993 2726.13   69.91
#Mann= 10 ,-1 , 0
       0     .09       0  164.66     .08       0  487.82     .05       0
  533.23     .08       0  577.39     .07       0 1508.91    .075       0
 2273.32    .045       0 2554.11    .035       0 2590.64    .045       0
 2677.06    .045       0
#XS Ineff= 2 , 0
       0                    1690       0      70
Permanent Ineff=
       F       F
Bank Sta=487.82,533.23
XS Rating Curve= 0 ,0
Exp/Cntr=0.3,0.1

Type RM Length L Ch R = 1 ,2252    ,519.75,844.27,531.78
XS GIS Cut Line= 4
2335955.24948318678099.9451499732336284.80672589677601.324866608
2336389.50660963676482.9397446662337003.42865528 675364.55462271
#Sta/Elev= 30
       0   74.51   27.87   73.98  106.39   71.79  221.54   63.49  408.64   62.06
   556.8   63.72  581.75   64.41  631.17   59.19  696.27    58.7   703.3   57.09
  724.62   54.57  771.85   54.73  788.15   57.04   980.8   58.18 1140.36   56.32
 1209.84    65.8 1225.68   66.07 1552.58    66.4 1881.0763.44348 2051.38   64.59
 2217.04   61.42 2332.54    56.1 2574.28   55.83 2661.73   58.83 2733.35   69.11
 2836.01   71.32 2882.29   69.99 2916.76   70.47 2981.79   70.86 2996.77   70.73
#Mann= 11 ,-1 , 0
       0     .09       0   27.87    .045       0  106.39     .09       0
   556.8     .08       0   703.3     .05       0  788.15     .08       0
 1881.07    .075       0 2733.35    .045       0 2882.29    .035       0
 2916.76    .045       0 2981.79    .045       0
#XS Ineff= 2 , 0
       0                    2050       0      70
Permanent Ineff=
       F       F
Bank Sta=703.3,788.15
XS Rating Curve= 0 ,0
Exp/Cntr=0.3,0.1

Type RM Length L Ch R = 1 ,1408    ,578.63,683.53,75.12
XS GIS Cut Line= 5
2336084.92512962 678210.48782666 2336722.6426034677810.724634126
2337003.42865528 677163.488989072336908.24694276 676406.79437466
2337098.61036779675383.590965226
#Sta/Elev= 30
       0   76.61  151.34   74.38   216.9   67.13  287.35    64.8  656.89   63.31
  809.8564.96765  882.91   66.78  947.05   64.99  989.24   57.87 1015.43   56.79
 1268.11   57.21 1272.31   54.23 1316.74   54.55 1326.49   57.31 1412.01   56.46
 1475.32   65.44 1491.33   65.89 1754.75   63.68 1874.78   66.13 1947.45   63.26
 2221.15   60.66 2351.59   62.49 2613.91   62.06 2972.81   56.04 3036.12   57.67
 3097.54   68.43 3142.87   69.64 3179.08   69.73 3200.93   71.24 3261.59    70.8
#Mann= 14 ,-1 , 0
       0    .045       0  151.34     .09       0   216.9    .045       0
  287.35     .09       0  656.89    .045       0  809.85     .09       0
  882.91     .08       0 1268.11     .05       0 1326.49     .08       0
 2221.15    .075       0 3097.54    .045       0 3142.87    .035       0
 3179.08    .045       0 3200.93    .045       0
#XS Ineff= 2 , 0
       0                    2606       0      75
Permanent Ineff=
       F       F
Bank Sta=1268.11,1326.49
XS Rating Curve= 0 ,0
Exp/Cntr=0.3,0.1

Type RM Length L Ch R = 1 ,724     ,1637.75,724.22,988.62
XS GIS Cut Line= 6
2336575.13312961678461.6971966922337366.46989265 677900.32154429
2337565.99497393677426.8721988952337041.81891297676777.570239469
 2336930.2201387676402.1925442072337116.21809581675384.276451573
#Sta/Elev= 30
       0   82.31   81.02   69.72   170.3   64.81  312.59    62.4  426.27    64.8
  809.8764.61561  877.39   64.18  926.88   63.01  969.06   65.38 1058.12   59.04
 1122.44   57.49 1149.23   53.96 1182.35   57.39 1348.11   56.84 1418.49   67.84
 1641.07   66.38 1763.97   68.65 2184.15   61.79 2337.16   66.65 2464.41   62.87
 2703.07   60.47 3105.32   62.03 3349.18   59.68 3457.55   56.12 3521.74      57
 3598.84   68.66 3627.72   69.85 3664.86   69.84 3679.86   71.64 3751.14   70.96
#Mann= 11 ,-1 , 0
       0     .09       0   81.02    .045       0  809.87     .09       0
  877.39     .08       0 1122.44     .05       0 1182.35     .08       0
 2703.07    .075       0 3598.84    .045       0 3627.72    .035       0
 3664.86    .045       0 3679.86    .045       0
#XS Ineff= 2 , 0
       0                    3100       0      75
Permanent Ineff=
       F       F
Bank Sta=1122.44,1182.35
XS Rating Curve= 0 ,0
Exp/Cntr=0.3,0.1

Chan Stop Cuts=-1
Use User Specified Reach Order=0