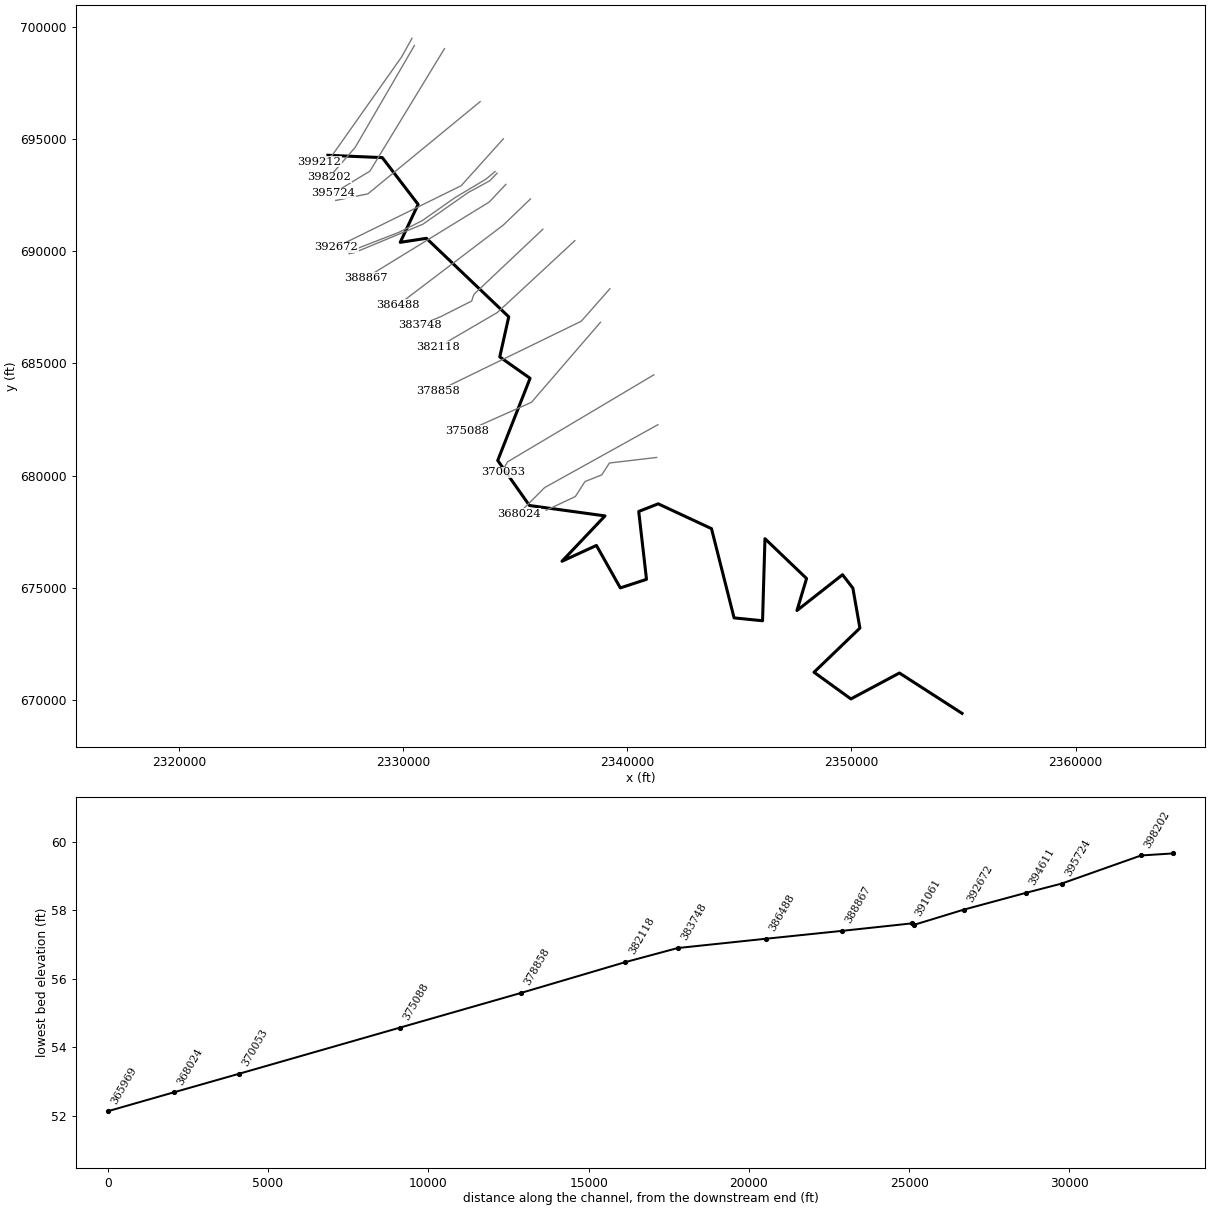
--- dtl_contentnea_crk_ds.prj (project) ---

Proj Title=dtl_contentnea_crk_ds
Current Plan=p01
Default Exp/Contr=0.3,0.1
English Units
Geom File=g01
Flow File=f01
Flow File=f02
Plan File=p01
Plan File=p02
Y Axis Title=Elevation
X Axis Title(PF)=Main Channel Distance
X Axis Title(XS)=Station
BEGIN DESCRIPTION:
END DESCRIPTION:
DSS Export Rating Curves= 0
DSS Export Rating Curve Sorted= 0
DSS Export Volume Flow Curves= 0
DXF OffsetX= 0
DXF OffsetY= 0
DXF ScaleX= 1
DXF ScaleY= 10

--- dtl_contentnea_crk_ds.p01 (plan) ---

Plan Title=dtl_contentnea_crk_ds
Program Version=4.00
Short Identifier=dtl_contentn
Geom File=g01
Flow File=f01
Subcritical Flow
K Sum by GR= 0
Std Step Tol= 0.01
Critical Tol= 0.01
Num of Std Step Trials= 20
Max Error Tol= 0.3
Flow Tol Ratio= 0.001
Split Flow NTrial= 30
Split Flow Tol= 0.02
Split Flow Ratio= 0.02
Log Output Level= 0
Friction Slope Method= 1
Unsteady Friction Slope Method= 2
Unsteady Bridges Friction Slope Method= 1
Parabolic Critical Depth
Global Vel Dist= 0 , 0 , 0
Global Log Level= 0
CheckData=True
Encroach Param=-1 ,10,10, 2
Encroach River=Contentnea Crk
Encroach Reach=Downstream
Encroach Node=399212
       1    2200    6580
Encroach Node=398202
       1    2462  6052.2
Encroach Node=395724
       1 2797.98  6599.6
Encroach Node=394611
       1 2109.22 6396.12
Encroach Node=392672
       1 3482.69 7609.67
Encroach Node=391131
       1 3394.87 6094.87
Encroach Node=391061
       1    3500    6200
Encroach Node=388867
       1 3607.46 6083.09
Encroach Node=386488
       1    3700    5670
Encroach Node=383748
       1 4286.41  5876.6
Encroach Node=382118
       1 3420.43 5369.13
Encroach Node=378858
       1    3650    6500
Encroach Node=375088
       1 3018.98 6237.28
Encroach Node=370053
       1    4700    7815
Encroach Node=368024
       1 3689.31 6891.97
Encroach Node=365969
       1    1710 4864.81
Encroach Node=365864
       1    1750 4908.81
Encroach Node=363211
       1    1390    5400
Encroach Node=357398
       1    1530    5550
Encroach Node=345617
       1     272    2795
Encroach Node=340949
       1 2405.12 6185.49
Encroach Node=333607
       1   553.1    2930
Encroach Node=333514
       1   553.1    2930
Encroach Node=332663
       1  732.94 2694.56
Encroach Node=330192
       1  1107.3 4021.89
Encroach Node=321739
       1    3600    6600
Encroach Node=319874
       1    4268 6065.87
Encroach Node=317122
       1    3200    5400
Encroach Node=315613
       1    4739    5075
Encroach Node=315500
       1 4739.61    5075
Encroach Node=314309
       1 2339.28 5138.74
Computation Interval=1HOUR
Output Interval=1HOUR
Run HTab= 0
Run UNet= 0
Run PostProcess= 0
Run WQNet= 0
UNET Theta= 1
UNET Theta Warmup= 1
UNET ZTol= 0.02
UNET ZSATol= 0.05
UNET MxIter= 20
UNET MaxInSteps= 0
UNET DtIC= 0
UNET DtMin= 0
UNET MaxCRTS= 20
UNET WFStab= 2
UNET SFStab= 1
UNET WFX= 1
UNET SFX= 1
UNET DSS MLevel= 4
UNET DZMax Abort= 100
UNET Convert EG Bridges= 0
UNET Use Existing IB Tables=-1
UNET Froude Reduction=False
UNET Froude Limit= 1
UNET Froude Power= 10
UNET Time Slicing=0,0, 5
Instantaneous Interval=1HOUR
Write IC File= 0
Echo Input=False
Echo Output=False
Write Detailed= 0
Detailed Automatic Start=False, 10
WQ ULTIMATE=-1
WQ Max Comp Step=1HOUR
WQ Output Interval=15MIN
WQ Output Selected Increments= 0
WQ Output face flow=0
WQ Output face velocity=0
WQ Output face area=0
WQ Output face dispersion=0
WQ Output cell volume=0
WQ Output cell surface area=0
WQ Output cell continuity=0
WQ Output face conc=0
WQ Output face dconc_dx=0
WQ Output face courant=0
WQ Output face peclet=0
WQ Output face adv mass=0
WQ Output face disp mass=0
WQ Output cell mass=0
WQ Output cell source sink temp=0
WQ Output cell source sink nsm=0
WQ Output MaxMinRange=-1
WQ Daily Max Min Mean=-1
WQ Daily Range=0
WQ Daily Time=0
WQ Create Restart=0
WQ Fixed Restart=0
WQ System Summary=False
Sorting and Armoring Iterations= 10
XS Update Threshold= 0.02
Hydraulics Update Threshold= 0.02
Energy Slope Method= 1
Volume Change Method= 0
XS Weighting Method= 0
Number of US Weighted Cross Sections= 1
Number of DS Weighted Cross Sections= 1
Upstream XS Weight=0.25
Main XS Weight=0.5
Downstream XS Weight=0.25
Number of DS XS's Weighted with US Boundary= 1
Upstream Boundary Weight= 1
Weight of XSs Associated with US Boundary= 0
Number of US XS's Weighted with DS Boundary= 1
Downstream Boundary Weight= 0.5
Weight of XSs Associated with DS Boundary= 0.5
Sediment Output Level= 4
Mass or Volume Output= 0
Output Increment Type= 1
Profile and TS Output Increment= 10
XS Output Flag= 0
XS Output Increment= 10
Disregard all LS=0
Disregard all Conn=0
Disregard all Breaches=0
Disregard all Pumps=0

--- dtl_contentnea_crk_ds.p02 (plan) ---

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Plan Title=dtl_contentnea_crk_ds_future
Short Identifier=future
Geom File=g01
Flow File=f02
Encroach Node=85546
Encroach Node=84536
Encroach Node=82058
       4       1
Encroach Node=80945
       4       1
Encroach Node=79006
       4       1
Encroach Node=77465
       4       1
Encroach Node=77395
Encroach Node=75201
       4       1
Encroach Node=72822
Encroach Node=70082
       4       1
Encroach Node=68452
       4       1
Encroach Node=65192
Encroach Node=61422
       4       1
Encroach Node=56387
Encroach Node=54358
       4       1
Encroach Node=52303
Encroach Node=52198
Encroach Node=49545
Encroach Node=43732
Encroach Node=31951
Encroach Node=27283
       4       1
Encroach Node=19941
Encroach Node=19848
Encroach Node=18997
       4       1
Encroach Node=16526
       4       1
Encroach Node=8073
Encroach Node=6208
       4       1
Encroach Node=3456
Encroach Node=1947
Encroach Node=1834
Encroach Node=643
       1    3700    5110

--- dtl_contentnea_crk_ds.f01 (steady flow) ---

Flow Title=dtl_contentnea_crk_ds
Program Version=4.00
Number of Profiles= 6
Profile Names=100-yr,FW,10-yr,25-yr,50-yr,500-yr
River Rch & RM=Contentnea Crk,Downstream      ,399212
   24030   24030   13240   17160   20530   36720
River Rch & RM=Contentnea Crk,Downstream      ,392672
   24130   24130   13290   17230   20610   36840
River Rch & RM=Contentnea Crk,Downstream      ,391131
   24310   24310   13400   17360   20770   37080
River Rch & RM=Contentnea Crk,Downstream      ,388867
   24450   24450   13480   17470   20890   37270
Boundary for River Rch & Prof#=Contentnea Crk,Downstream      , 1
Up Type= 0
Dn Type= 1
Dn Known WS=58.78
Boundary for River Rch & Prof#=Contentnea Crk,Downstream      , 2
Up Type= 0
Dn Type= 1
Dn Known WS=59.54
Boundary for River Rch & Prof#=Contentnea Crk,Downstream      , 3
Up Type= 0
Dn Type= 1
Dn Known WS=56.14
Boundary for River Rch & Prof#=Contentnea Crk,Downstream      , 4
Up Type= 0
Dn Type= 1
Dn Known WS=57.22
Boundary for River Rch & Prof#=Contentnea Crk,Downstream      , 5
Up Type= 0
Dn Type= 1
Dn Known WS=58.02
Boundary for River Rch & Prof#=Contentnea Crk,Downstream      , 6
Up Type= 0
Dn Type= 1
Dn Known WS=60.46
DSS Import GetInterval= 0
DSS Import GetPeak= 0
DSS Import FillOption= 0

--- dtl_contentnea_crk_ds.f02 (steady flow) ---

Flow Title=dtl_contentnea_crk_ds_future
Program Version=4.00
Number of Profiles= 3
Profile Names=100yr-10%,100yr-20%,100yr-35%
River Rch & RM=Contentnea Crk,Downstream      ,399212
   23000   29500   36100
River Rch & RM=Contentnea Crk,Downstream      ,392672
   23100   29600   36200
River Rch & RM=Contentnea Crk,Downstream      ,391131
   23300   29800   36500
River Rch & RM=Contentnea Crk,Downstream      ,388867
   23400   30000   36700
Boundary for River Rch & Prof#=Contentnea Crk,Downstream      , 1
Up Type= 0
Dn Type= 1
Dn Known WS=60.89
Boundary for River Rch & Prof#=Contentnea Crk,Downstream      , 2
Up Type= 0
Dn Type= 1
Dn Known WS=61.43
Boundary for River Rch & Prof#=Contentnea Crk,Downstream      , 3
Up Type= 0
Dn Type= 1
Dn Known WS=62.18
DSS Import GetInterval= 0
DSS Import GetPeak= 0
DSS Import FillOption= 0

--- dtl_contentnea_crk_ds.g01 (geometry) ---

Geom Title=dtl_contentnea_crk_ds
Program Version=4.00

River Reach=Contentnea Crk  ,Downstream
Reach XY= 30
 2326646.5105684694266.7706518322329072.19323315694162.535373583
2330669.53716782692079.307352349  2329871.877459 690388.83563444
2331042.04830086690566.9931328452334712.49767162687070.652226448
2334311.64330016685285.0282082562335664.02067451684331.480688348
2334220.54003394680671.1539027242335635.67743613678664.857528523
2339006.49828681678201.2431292382337087.25614481676180.775135845
2338623.86456862676885.3070614042339688.76052505674994.408157766
2340856.90684991675375.0173589292340510.71443819678399.645797923
2341379.23224296 678739.764658542343756.01523319677634.378361553
2344764.22471286673658.2269196662346033.59688906 673530.68234694
2346140.89629151 677186.960098492347997.37840566675413.483182445
2347568.18079588673986.198678121 2349600.7958914675581.518095747
2350062.38577366674984.2855726332350376.18591292673202.710588485
2348329.39919817671236.9045548442349975.33154149 670048.51305975
2352139.54024382671202.4877653872354932.44196014669404.431237429

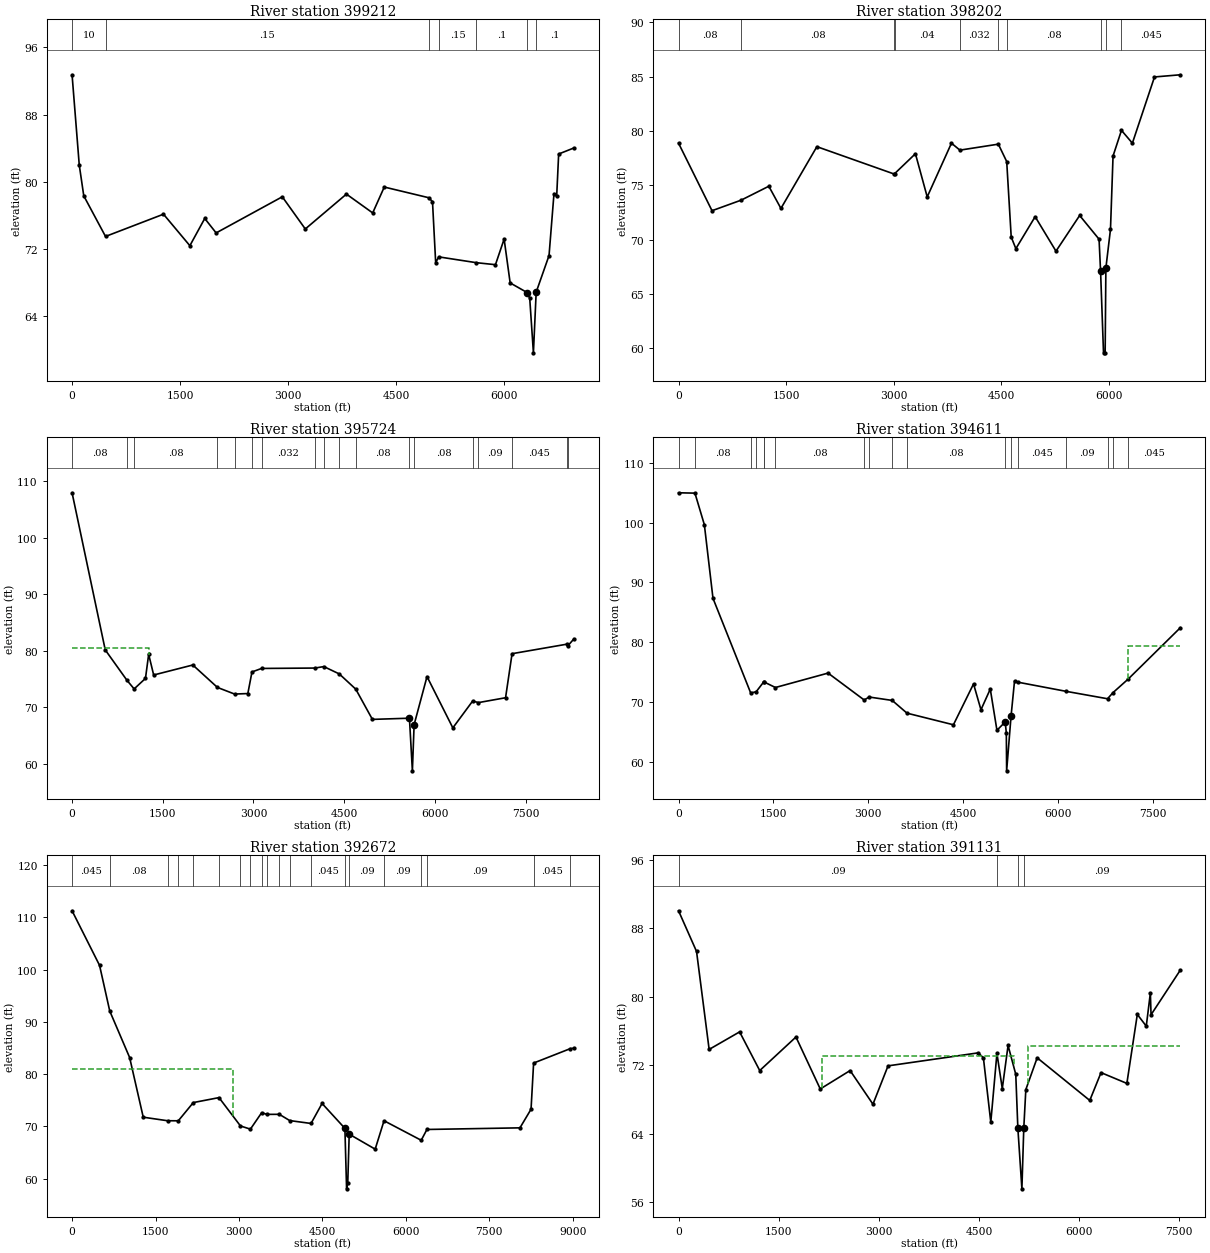
Type RM Length L Ch R = 1 ,399212  ,690.55,1010.15,668.98
XS GIS Cut Line= 5
2330395.99996555699476.2499959022329999.99997874698766.562476993
2329933.49998657698647.4374897032326831.74998499694256.125008777
2326255.75003202693979.187522694
#Sta/Elev= 30
       0   92.75   99.77   82.01  162.46   78.34  464.33   73.51 1268.85   76.16
 1634.98   72.41 1841.41   75.65 1999.57   73.93 2917.64   78.23 3237.02    74.4
 3807.84   78.55 4172.52   76.31 4333.14   79.39 4950.34   78.12 5002.51   77.65
 5046.63   70.39 5088.86   71.08 5610.08   70.39 5876.45   70.15 5996.73    73.2
  6080.3   67.98 6318.92   66.82 6352.01   66.15 6403.17   59.66 6441.49   66.88
 6620.02   71.24 6688.74   78.61 6726.26   78.31 6753.52   83.32 6964.53   84.04
#Mann= 7 ,-1 , 0
       0      10       0  464.33     .15       0 4950.34    .065       0
 5088.86     .15       0 5610.08      .1       0 6318.92     .05       0
 6441.49      .1       0
Bank Sta=6318.92,6441.49
XS Rating Curve= 0 ,0
Exp/Cntr=0.3,0.1

Type RM Length L Ch R = 1 ,398202  ,1388.25,2477.31,1052.09
XS GIS Cut Line= 3
2330502.60642201699152.8688178512327861.54299195694616.203409806
2326711.40246597693295.671694785
#Sta/Elev= 30
       0   78.88   467.1   72.67  872.98   73.64  1259.5   74.92  1428.4   72.88
 1930.07   78.56 3001.16   76.06 3015.16   76.08 3304.92   77.91 3469.37   73.94
 3807.63   78.88 3925.24   78.24 4461.4978.78968  4578.4   77.19 4641.23   70.25
 4706.19   69.18 4975.13   72.12 5265.81   68.95 5596.12   72.23 5866.95   70.05
 5887.95    67.1 5929.02    59.6  5951.8    59.6 5962.03    67.4 6026.26   70.96
 6061.97    77.7 6179.44   80.06  6331.7   78.88 6640.28   84.97 7000.61   85.17
#Mann= 10 ,-1 , 0
       0     .08       0  872.98     .08       0 3001.16     .08       0
 3015.16     .04       0 3925.24    .032       0 4461.49     .04       0
  4578.4     .08       0 5887.95     .05       0 5962.03     .09       0
 6179.44    .045       0
Bank Sta=5887.95,5962.03
XS Rating Curve= 0 ,0
Exp/Cntr=0.3,0.1

Type RM Length L Ch R = 1 ,395724  ,1592.52,1113.07,809.86
XS GIS Cut Line= 3
2331845.67658065699017.0638641422328518.86055161693559.941682652
2326886.14943279692570.985233545
#Sta/Elev= 30
       0  107.96  548.71   80.17  908.86   74.78 1026.72   73.27 1214.08   75.13
 1266.88   79.39 1349.54   75.73 1997.08    77.5 2404.54   73.53  2688.4   72.36
 2907.18   72.45 2975.59   76.27 3134.12   76.89 4016.42   76.96 4164.16   77.22
 4419.81   75.92 4692.05   73.23 4967.54   67.88 5580.16   68.09 5628.89   58.78
 5657.35   66.94 5870.73   75.45 6297.99   66.38 6625.97   71.13 6722.25   70.85
 7169.89   71.71 7277.53    79.5 8178.09   81.17 8202.99   80.92 8299.62   82.11
#Mann= 18 ,-1 , 0
       0     .08       0  908.86    .075       0 1026.72     .08       0
 2404.54    .075       0  2688.4     .08       0 2975.59     .04       0
 3134.12    .032       0 4016.42     .04       0 4164.16    .032       0
 4419.81     .04       0 4692.05     .08       0 5580.16     .05       0
 5657.35     .08       0 6625.97     .04       0 6722.25     .09       0
 7277.53    .045       0 8178.09    .035       0 8202.99    .045       0
#XS Ineff= 2 , 0
         1269.58   80.52
Permanent Ineff=
       F       F
Bank Sta=5580.16,5657.35
XS Rating Curve= 0 ,0
Exp/Cntr=0.3,0.1

Type RM Length L Ch R = 1 ,394611  ,2298.63,1939.61,1599.18
XS GIS Cut Line= 3
2333437.53580952696656.1971574572328430.96846369692548.818681002
2326996.81458075692254.104213268
#Sta/Elev= 30
       0  104.99  259.64  104.93  408.62   99.65  545.13   87.35 1140.97   71.55
 1226.72   71.71    1349   73.39 1353.7673.35967  1533.2   72.44 2366.09   74.85
 2937.78   70.35 3015.59   70.85 3380.83   70.28 3615.06   68.15 4349.53   66.21
 4667.86   73.04 4785.17   68.72 4932.76   72.18 5038.11   65.29 5168.74   66.68
 5186.37   64.88 5191.57   58.51 5261.01   67.61 5316.55   73.55 5368.99   73.33
 6132.02    71.8 6787.86   70.56  6875.2   71.59  7112.6   73.83  7939.8   82.43
#Mann= 18 ,-1 , 0
       0    .045       0  259.64     .08       0 1140.97    .075       0
 1226.72     .08       0    1349     .08       0 1353.76    .075       0
  1533.2     .08       0 2937.78    .075       0 3015.59     .08       0
 3380.83    .075       0 3615.06     .08       0 5168.74     .05       0
 5261.01     .08       0 5368.99    .045       0 6132.02     .09       0
 6787.86     .04       0  6875.2     .09       0  7112.6    .045       0
#XS Ineff= 2 , 0
                         7119.61           79.38
Permanent Ineff=
       F       F
#Block Obstruct= 1 ,-1
  193.31  240.97104.8299
Bank Sta=5168.74,5261.01
XS Rating Curve= 0 ,0
Exp/Cntr=0.3,0.1

Type RM Length L Ch R = 1 ,392672  ,338.15,1540.1,556.85
XS GIS Cut Line= 3
 2334472.3751322695000.4039957822332589.90783691692909.989731848
2327019.11799222690173.845407352
#Sta/Elev= 30
       0  111.27  494.03  100.82  677.37   92.07 1034.58   83.17  1279.3   71.74
 1717.32   71.06 1909.44   71.05 2179.13   74.54 2640.93   75.49 3026.97   70.06
 3205.55   69.45 3408.49   72.61 3500.49   72.28 3725.08   72.29 3912.6971.09081
 4295.12   70.54 4493.86   74.37 4903.94    69.6  4934.5   58.02 4955.56   59.17
 4981.48   68.49 5448.23   65.62 5607.46   71.06 6275.81   67.32 6378.63   69.39
 8050.72    69.7 8250.09   73.27 8296.19   82.11 8948.3184.83916 9019.56   84.96
#Mann= 20 ,-1 , 0
       0    .045       0  677.37     .08       0 1717.32    .075       0
 1909.44     .08       0 2179.13    .045       0 2640.93     .08       0
 3026.97    .075       0 3205.55     .08       0 3408.49    .045       0
 3500.49     .04       0 3725.08    .045       0 3912.69     .08       0
 4295.12    .045       0 4903.94     .05       0 4981.48     .09       0
 5607.46     .09       0 6275.81    .075       0 6378.63     .09       0
 8296.19    .045       0 8948.31     .09       0
#XS Ineff= 2 , 0
       0    2900      81               0
Permanent Ineff=
       F       F
Bank Sta=4903.94,4981.48
XS Rating Curve= 0 ,0
Exp/Cntr=0.5,0.3

Type RM Length L Ch R = 1 ,391131  ,140.01,70.08,91.03
BEGIN DESCRIPTION:
Surveyed Section
END DESCRIPTION:
XS GIS Cut Line= 6
2334103.32728498693542.0676336742333695.82861087693203.157845318
2332328.08553641692388.1604970842330835.26861146691343.188649639
    2329816.9576690836.950900018 2327551.4593063689956.408556297
#Sta/Elev= 30
       0   90.07  269.72   85.32  458.47   73.87  914.93   75.92 1216.34    71.4
 1759.12   75.32 2122.91   69.25 2570.15    71.4 2912.42   67.47 3138.57   71.95
 4491.24   73.47 4566.89   72.88 4677.65   65.37  4769.5    73.4 4849.75    69.3
 4936.45   74.335051.688   70.965082.957   64.68 5143.57   57.58 5171.74   64.67
 5202.53   69.185372.393   72.89 6160.23   67.91 6329.09   71.16 6715.97    69.9
 6872.48   77.96 7006.66   76.59 7068.15   80.47 7078.16   77.92 7516.82   83.14
#Mann= 4 ,-1 , 0
       0     .09       0  4769.5     .06       05082.957     .05       0
 5171.74     .09       0
#XS Ineff= 3 ,-1
       0    2150            2150    5022   73.15    5231 7516.82   74.32
Permanent Ineff=
       F       T       T
Bank Sta=5082.957,5171.74
XS Rating Curve= 0 ,0
Exp/Cntr=0.5,0.3

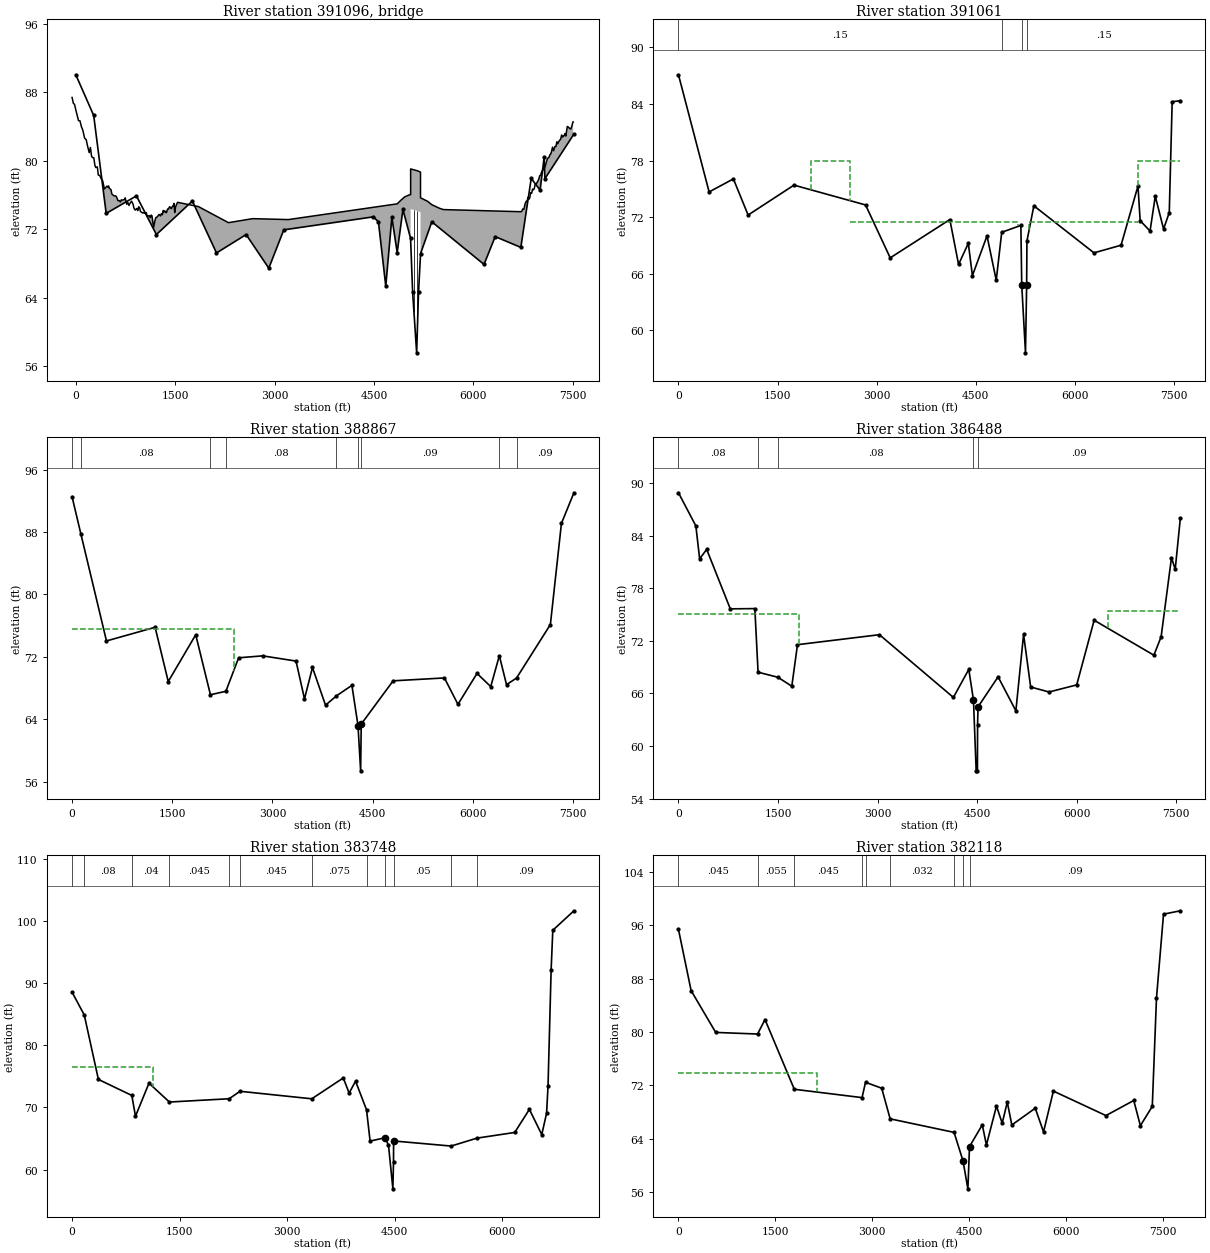
Type RM Length L Ch R = 3 ,391096  ,,,
BEGIN DESCRIPTION:
Evansdale Road
END DESCRIPTION:
Bridge Culvert--1,0,-1,-1, 0
Deck Dist Width WeirC Skew NumUp NumDn MinLoCord MaxHiCord MaxSubmerge Is_Ogee
20,28,2.6,0, 170, 170, , , 0.98, 0, 1,1,,
  -56.37  -37.21  -18.84       1   20.76   40.94   62.82   85.22   98.15  108.95
  131.93  157.21  175.73  202.33  220.57  237.48   250.7  271.41  288.29   301.7
   324.7  339.14  361.35  383.86  406.28  431.45  470.56  481.77  494.61  505.38
  531.26  544.77   575.5  598.58  611.17  636.14   658.1  672.79  687.49  702.34
  733.78  745.12  768.58  784.65  801.15  823.62  841.77  866.06  877.15  896.87
  920.95  935.11  949.17  963.75  975.93  991.71 1005.42 1019.79 1033.48 1046.71
 1063.97 1075.95 1087.17 1109.24 1124.13 1137.63 1149.02 1173.93 1193.76 1207.43
 1220.85 1234.22 1256.18  1278.2 1292.06 1306.04 1319.63 1330.18 1343.49 1354.64
 1368.06 1384.81 1398.01 1415.11  1427.1 1440.79 1458.34 1470.33  1481.5 1492.27
 1505.39 1523.83 1535.27 1849.89 2304.06 2668.55 3207.384850.352 4907.724964.906
5022.6195052.7485052.7485102.7895152.5135201.8625201.8625262.2925312.0095369.905
5429.6065488.7565547.215 6720.06 6731.73 6744.84 6762.22 6781.13 6796.58 6809.52
 6823.76 6838.24 6850.82  6863.7 6879.57 6892.56 6907.52 6919.65 6931.31 6946.19
 6956.93  6970.9 6986.17 7000.09  7015.1 7029.14 7041.76 7053.52  7069.7 7082.78
 7097.19 7114.23 7127.94  7141.1 7153.04 7165.38 7176.34 7193.72  7209.6 7229.39
 7245.51 7259.33 7272.91 7284.67 7298.92 7317.28 7331.32 7346.61 7358.07 7370.23
 7381.99 7394.02  7416.9 7427.54 7440.34  7456.9  7469.8 7486.62 7501.69 7504.55
   87.42   86.74   86.61   85.93   85.33   84.71   84.69   83.98   83.76    83.5
   82.68   82.48    81.8   80.97   81.58   80.57    80.4   80.37   79.48   79.23
   79.31   78.36    78.3   77.92   77.66   76.73   77.06   76.94   77.08   76.82
   76.64   76.13   75.93   75.92   75.86   75.37   75.36   75.21   75.46   75.42
    75.5   75.69   74.94   75.15    74.8   75.13    75.3    74.9   74.49   74.26
   74.45    74.2   74.65   74.52   74.08   74.03   73.92   73.97   73.89   73.88
   73.96   73.55   73.56   73.61   73.38   73.68   73.59   72.24   73.02   73.37
   73.43   73.52   73.75   73.58   73.85   73.72   74.22   74.03   74.17      74
   73.96   74.38   74.38   74.66   74.56   74.42   74.71   74.74   75.04   73.97
   74.65   74.96   75.17   74.67   72.79   73.26   73.15   74.99   75.43   75.81
   76.01   76.07   79.07   78.97   78.86    78.7    75.7   75.47   75.27    74.9
   74.69   74.47   74.32   74.07   74.15   74.39   74.36   75.03   75.28   75.27
   75.74   75.52   75.71   76.29   76.24   76.72   76.63   76.79   77.26    77.3
   77.45   77.61   77.86   78.27   78.34   78.72   78.89   78.99   79.15   79.37
   79.78   80.23   80.36   80.42   80.71    80.8   81.03   81.61   81.19   81.69
   81.69   82.24   82.01   82.23   82.39   82.56   83.04   82.79   82.92   82.97
    83.2   82.91   84.03   83.99   83.89   83.78   83.73   84.11   84.56   84.57
                                                                                
                                                                                
                                                                                
                                                                                
                                                                                
                                                                                
                                                                                
                                                                                
                                                                                
                                                                                
                   74.37   74.27   74.16      74
                                                                                
                                                                                
                                                                                
                                                                                
                                                                                
                                                                                
  37.532  56.692  75.062  94.902 114.662 134.842 156.722 179.122 192.052 202.852
 225.832 251.112 269.632 296.232 314.472 331.382 344.602 365.312 382.192 395.602
 418.602 433.042 455.252 477.762 500.182 525.352 564.462 575.672 588.512 599.282
 625.162 638.672 669.402 692.482 705.072 730.042 752.002 766.692 781.392 796.242
 827.682 839.022 862.482 878.552 895.052 917.522 935.672 959.962 971.052 990.772
1014.8521029.0121043.0721057.6521069.8321085.6121099.3221113.6921127.3821140.612
1157.8721169.8521181.0721203.1421218.0321231.5321242.9221267.8321287.6621301.332
1314.7521328.1221350.0821372.1021385.9621399.9421413.5321424.0821437.3921448.542
1461.9621478.7121491.9121509.0121521.0021534.6921552.2421564.2321575.4021586.172
1599.2921617.7321629.1721943.7922397.9622762.4523301.2824944.2545001.6225058.808
5116.521 5146.65 5146.655196.6915246.4155295.7645295.7645356.1945405.9115463.807
5523.5085582.6585641.1176813.9626825.6326838.7426856.1226875.0326890.4826903.422
6917.6626932.1426944.7226957.6026973.4726986.4627001.4227013.5527025.2127040.092
7050.8327064.8027080.0727093.9927109.0027123.0427135.6627147.4227163.6027176.682
7191.0927208.1327221.8427235.0027246.9427259.2827270.2427287.6227303.5027323.292
7339.4127353.2327366.8127378.5727392.8227411.1827425.2227440.5127451.9727464.132
7475.8927487.9227510.8027521.4427534.2427550.8027563.7027580.5227595.5927598.452
   87.42   86.74   86.61   85.93   85.33   84.71   84.69   83.98   83.76    83.5
   82.68   82.48    81.8   80.97   81.58   80.57    80.4   80.37   79.48   79.23
   79.31   78.36    78.3   77.92   77.66   76.73   77.06   76.94   77.08   76.82
   76.64   76.13   75.93   75.92   75.86   75.37   75.36   75.21   75.46   75.42
    75.5   75.69   74.94   75.15    74.8   75.13    75.3    74.9   74.49   74.26
   74.45    74.2   74.65   74.52   74.08   74.03   73.92   73.97   73.89   73.88
   73.96   73.55   73.56   73.61   73.38   73.68   73.59   72.24   73.02   73.37
   73.43   73.52   73.75   73.58   73.85   73.72   74.22   74.03   74.17      74
   73.96   74.38   74.38   74.66   74.56   74.42   74.71   74.74   75.04   73.97
   74.65   74.96   75.17   74.67   72.79   73.26   73.15   74.99   75.43   75.81
   76.01   76.07   79.07   78.97   78.86    78.7    75.7   75.47   75.27    74.9
   74.69   74.47   74.32   74.07   74.15   74.39   74.36   75.03   75.28   75.27
   75.74   75.52   75.71   76.29   76.24   76.72   76.63   76.79   77.26    77.3
   77.45   77.61   77.86   78.27   78.34   78.72   78.89   78.99   79.15   79.37
   79.78   80.23   80.36   80.42   80.71    80.8   81.03   81.61   81.19   81.69
   81.69   82.24   82.01   82.23   82.39   82.56   83.04   82.79   82.92   82.97
    83.2   82.91   84.03   83.99   83.89   83.78   83.73   84.11   84.56   84.57
                                                                                
                                                                                
                                                                                
                                                                                
                                                                                
                                                                                
                                                                                
                                                                                
                                                                                
                                                                                
                   74.37   74.27   74.16      74
                                                                                
                                                                                
                                                                                
                                                                                
                                                                                
                                                                                
Pier Skew, UpSta & Num, DnSta & Num=  ,5102.789, 2 ,5196.691, 2 , 0 , 0 , 0 ,,
     2.5     2.5
      55   74.37
     2.5     2.5
      55   74.37
Pier Skew, UpSta & Num, DnSta & Num=  ,5152.513, 2 ,5246.415, 2 , 0 , 0 , 0 ,,
     2.5     2.5
      55   74.37
     2.5     2.5
      55   74.37
BR Coef=-1 , 0 , 0 ,, 0 ,,,0.8,0,,0,
WSPro=,,,, 1 ,,,, 0 ,,,, 0 ,,,,-1 ,-1 ,-1 , 0 , 0 , 0 , 0 , 0
BC Design=,, 0 ,, 0 ,,,,,,
BC Use User HTab Curves=0
BC User HTab FreeFlow(D)= 0

Type RM Length L Ch R = 1 ,391061  ,834.99,2194.71,1068.37
BEGIN DESCRIPTION:
Surveyed Section
END DESCRIPTION:
XS GIS Cut Line= 6
2334190.32039726693464.9585788852333864.54112582693129.959139362
2332914.86381564692613.6297279892330884.26680304691196.892003432
2327834.64128084689931.3924807912327590.48438406689884.362258866
#Sta/Elev= 30
       0    87.1  463.68   74.68  831.05   76.06 1053.84   72.23 1748.21    75.4
 2831.69    73.3 3204.62   67.69  4107.2   71.75 4239.24   66.99  4386.6   69.23
 4448.61   65.81 4669.86   70.02  4809.3   65.32 4892.39    70.45182.269   71.13
5195.336    64.8 5252.13   57.625269.627   64.845273.851   69.475378.761   73.21
 6288.82   68.22  6698.6   69.03 6954.56   75.31 6987.43   71.64 7136.98   70.53
 7216.35   74.22 7342.06   70.75 7428.16   72.49 7472.09   84.24 7595.48   84.35
#Mann= 4 ,-1 , 0
       0     .15       0 4892.39     .06       05195.336     .05       0
5269.627     .15       0
#XS Ineff= 5 ,-1
       0 2010.89         2010.89    2600      78    2600 5136.65    71.5
 5305.76 6954.56    71.5 6954.56 7595.48      78
Permanent Ineff=
       F       F       F       F       F
Bank Sta=5195.336,5269.627
XS Rating Curve= 0 ,0
Exp/Cntr=0.5,0.3

Type RM Length L Ch R = 1 ,388867  ,1323.97,2378.34,1919.15
XS GIS Cut Line= 3
2334583.18897733692971.5529791412333848.53422619 692187.64763017
2328360.25432865688820.414549172
#Sta/Elev= 30
       0   92.51  130.73   87.78  515.21   74.04 1243.02   75.79 1439.83   68.84
 1851.21   74.83  2071.4   67.15 2302.81   67.59 2493.31   71.88 2853.74   72.13
  3352.8   71.46  3479.6   66.62 3599.03   70.64 3794.45   65.81 3958.73   67.01
 4189.53   68.35 4280.89   63.19  4320.2    57.4 4329.14   63.39 4806.69   68.93
  5574.4    69.3 5777.03   65.92 6062.54   69.88 6268.06   68.19 6396.78   72.15
  6504.2   68.44 6654.49   69.29 7160.87   76.14 7326.28    89.1 7513.25   93.02
#Mann= 9 ,-1 , 0
       0     .06       0  130.73     .08       0  2071.4    .075       0
 2302.81     .08       0 3958.73     .09       0 4280.89     .05       0
 4329.14     .09       0 6396.78     .08       0 6654.49     .09       0
#XS Ineff= 2 , 0
         2420.45   75.56
Permanent Ineff=
       F       F
Bank Sta=4280.89,4329.14
XS Rating Curve= 0 ,0
Exp/Cntr=0.3,0.1

Type RM Length L Ch R = 1 ,386488  ,1427.97,2740.64,1690.16
XS GIS Cut Line= 3
2335682.78551647692322.6333724712334466.45778868691155.450199366
 2329785.4389575687604.756125316
#Sta/Elev= 30
       0   88.91  261.81   85.13  319.03   81.37  425.12   82.45  780.73   75.66
 1150.64   75.69 1199.19   68.43  1498.6   67.85 1707.45   66.83 1793.08   71.57
 3027.69   72.71 4141.92   65.55 4373.98   68.75  4444.4   65.26 4485.26   57.17
 4503.99   57.17 4506.47   62.45  4513.1   64.47 4815.49    67.9 5083.49   64.02
 5199.47   72.74 5306.14   66.74 5583.55   66.17 5999.95   66.98 6262.66   74.36
 7162.75   70.37 7271.78   72.47  7428.1   81.51 7484.01   80.16 7561.07   85.99
#Mann= 5 ,-1 , 0
       0     .08       0 1199.19    .032       0  1498.6     .08       0
  4444.4     .05       0  4513.1     .09       0
#XS Ineff= 2 , 0
         1810.38   75.12 6468.69           75.43
Permanent Ineff=
       F       F
Bank Sta=4444.4,4513.1
XS Rating Curve= 0 ,0
Exp/Cntr=0.3,0.1

Type RM Length L Ch R = 1 ,383748  ,1333.3,1629.87,1085.41
BEGIN DESCRIPTION:
Surveyed Section
END DESCRIPTION:
XS GIS Cut Line= 6
2336233.93279554690972.1216485352333174.41036403688085.925168976
2333121.28550002687972.301499993    2333061.5808687774.657900006
2331685.61213769687080.6342484952330733.43391274686686.629465774
#Sta/Elev= 30
       0   88.57  170.01    84.9  367.07   74.52     833   71.94  884.05   68.59
 1072.09   73.91 1357.27   70.88 2190.98   71.41 2341.08   72.61 3341.96    71.4
 3781.05   74.76 3862.61   72.32 3951.99   74.24 4105.24   69.62 4154.76   64.59
 4361.52   65.12 4411.25   63.94 4472.43    56.9 4481.13   61.25 4482.65   64.61
 5284.67   63.79 5646.04   65.07 6171.17   65.98 6375.66    69.7 6547.96   65.64
 6615.39   69.08 6635.57   73.51 6678.37   92.08 6701.89   98.54 6996.31  101.68
#Mann= 12 ,-1 , 0
       0    .045       0  170.01     .08       0     833     .04       0
 1357.27    .045       0 2190.98    .055       0 2341.08    .045       0
 3341.96    .075       0 4105.24     .09       0 4361.52     .05       0
 4482.65     .05       0 5284.67    .075       0 5646.04     .09       0
#XS Ineff= 2 , 0
         1127.01    76.5
Permanent Ineff=
       F       F
Bank Sta=4361.52,4482.65
XS Rating Curve= 0 ,0
Exp/Cntr=0.3,0.1

Type RM Length L Ch R = 1 ,382118  ,2596.89,3259.97,1945.1
XS GIS Cut Line= 3
2337661.35134241690462.508633569 2334204.4015808687262.596647277
2331565.22178741685723.506663546
#Sta/Elev= 30
       0   95.36  195.78   86.19  576.28   79.93 1223.89   79.69 1339.01   81.86
 1792.34   71.41 2840.73   70.16 2894.31   72.46 3144.72   71.57 3275.61   66.98
 4264.97   64.95  4403.1   60.67 4478.47   56.49 4503.59   62.82 4701.45   66.08
 4765.19   63.06 4920.71   68.89 5009.48   66.33 5088.45   69.49 5158.21   66.06
 5520.84   68.57 5648.98   65.03 5801.51   71.14 6614.73   67.47 7045.04   69.73
 7147.57   65.96  7331.8   68.84 7397.07   85.12 7505.85   97.65 7765.79   98.16
#Mann= 9 ,-1 , 0
       0    .045       0 1223.89    .055       0 1792.34    .045       0
 2840.73     .08       0 2894.31    .055       0 3275.61    .032       0
 4264.97     .09       0  4403.1     .05       0 4503.59     .09       0
#XS Ineff= 2 , 0
         2147.46   73.78
Permanent Ineff=
       F       F
Bank Sta=4403.1,4503.59
XS Rating Curve= 0 ,0
Exp/Cntr=0.3,0.1

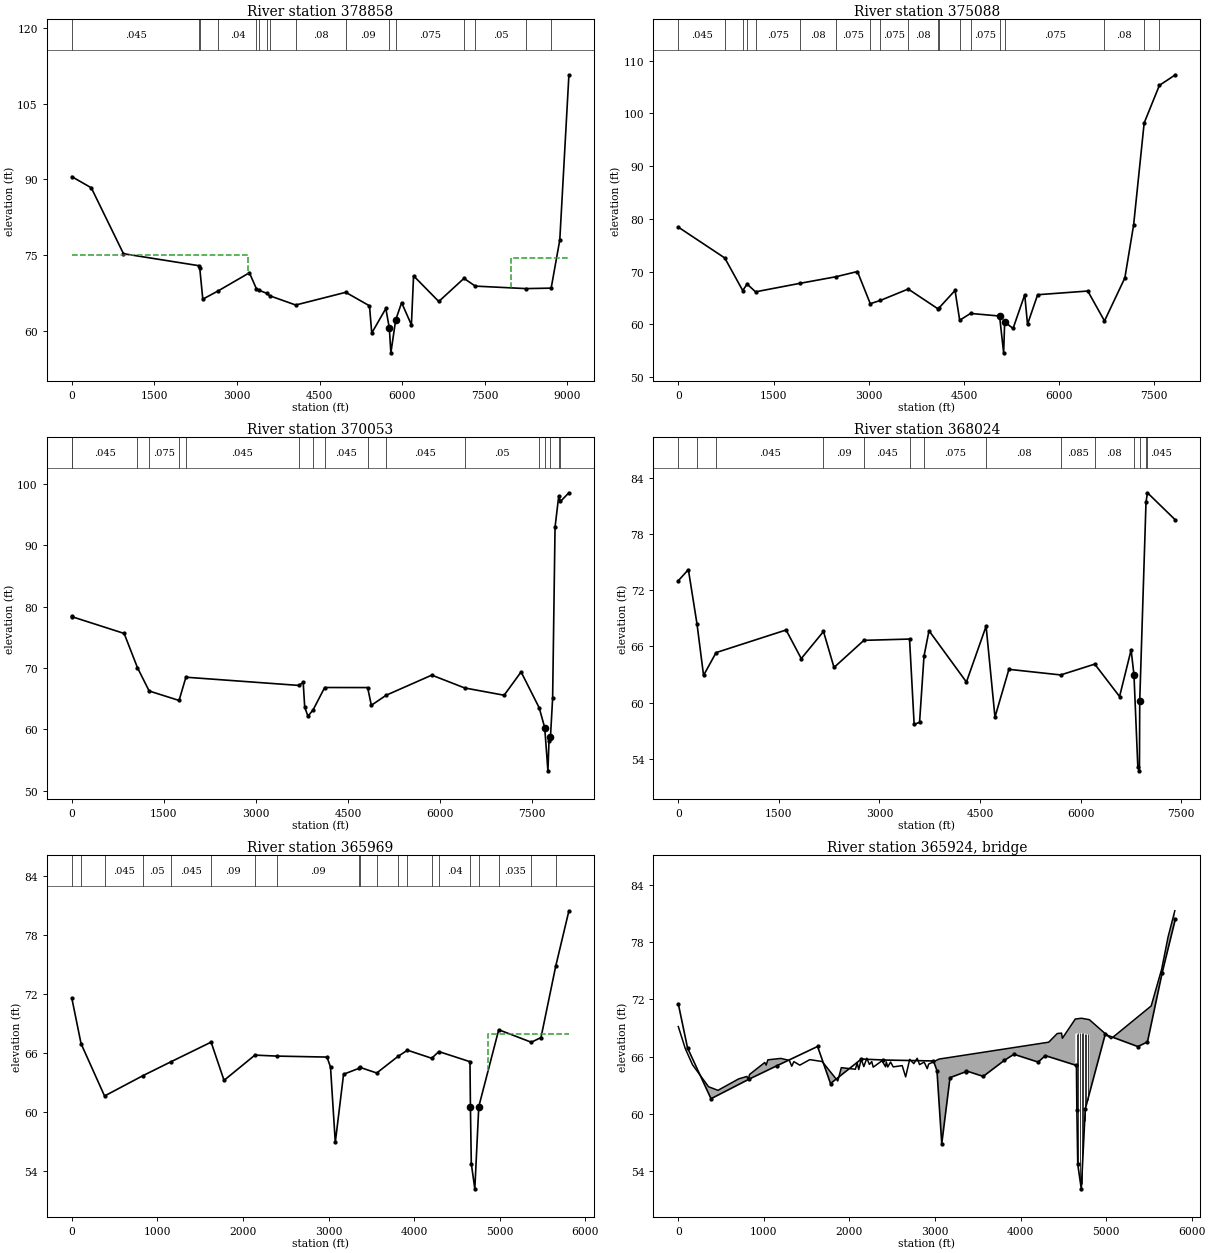
Type RM Length L Ch R = 1 ,378858  ,1307.44,3770.09,2341.5
XS GIS Cut Line= 3
2339224.91331992688321.6108422432337945.91035214686872.687279835
 2331561.1901319683771.274957165
#Sta/Elev= 30
       0   90.55  353.57   88.34  938.23   75.26  2316.4   72.87 2323.62   72.46
 2379.31   66.24 2663.1867.91086 3226.23   71.48 3354.04   68.28 3409.13   67.97
 3544.59   67.39 3593.36   66.92 4067.47   65.08 4975.97    67.6 5407.87   64.92
 5448.71   59.51 5704.61   64.39 5767.97   60.52 5796.27   55.59 5883.57   62.11
 5991.28   65.55  6169.1   61.14 6208.56   70.87 6666.56   65.78  7124.4   70.37
  7329.4   68.83 8248.73   68.34  8708.4   68.43 8864.82   77.98  9030.8  110.77
#Mann= 16 ,-1 , 0
       0    .045       0  2316.4     .08       0 2323.62     .08       0
 2663.18     .04       0 3354.04    .032       0 3409.13     .04       0
 3544.59     .08       0 3593.36    .075       0 4067.47     .08       0
 4975.97     .09       0 5767.97     .05       0 5883.57    .075       0
  7124.4     .09       0  7329.4     .05       0 8248.73    .075       0
  8708.4    .085       0
#XS Ineff= 2 , 0
         3196.19    75.1 7971.88           74.34
Permanent Ineff=
       F       F
Bank Sta=5767.97,5883.57
XS Rating Curve= 0 ,0
Exp/Cntr=0.3,0.1

Type RM Length L Ch R = 1 ,375088  ,2813.11,5034.75,2296.55
XS GIS Cut Line= 3
2338804.84121095686827.1204691232335724.16116066683260.976771474
 2332873.1602627681994.970623508
#Sta/Elev= 30
       0   78.42  732.29   72.57 1015.03   66.39 1083.95   67.62 1217.09   66.15
 1912.57   67.75 2487.44   69.02 2822.37      70 3024.72    63.9 3182.14   64.51
  3622.3   66.68 4090.65   62.93  4102.4   63.02 4360.07   66.41 4433.69   60.76
 4604.43   62.05 5061.82   61.56 5126.04   54.58 5142.38   60.45 5274.36    59.2
  5458.3   65.59 5502.15   59.99 5661.77    65.6 6451.56    66.3 6715.15   60.62
 7035.93   68.79 7173.68    78.8 7340.14   98.17  7579.8 105.299 7831.99  107.31
#Mann= 19 ,-1 , 0
       0    .045       0  732.29     .04       0 1015.03     .08       0
 1083.95    .032       0 1217.09    .075       0 1912.57     .08       0
 2487.44    .075       0 3024.72    .032       0 3182.14    .075       0
  3622.3     .08       0 4090.65     .09       0  4102.4     .08       0
 4433.69     .09       0 4604.43    .075       0 5061.82     .05       0
 5142.38    .075       0 6715.15     .08       0 7340.14     .06       0
  7579.8    .045       0
Bank Sta=5061.82,5142.38
XS Rating Curve= 0 ,0
Exp/Cntr=0.3,0.1

Type RM Length L Ch R = 1 ,370053  ,1951.88,2028.86,2005.69
XS GIS Cut Line= 6
2341185.50523236684486.769428849    2334654.9201680606.759000018
    2334612.3248680517.485800013    2334588.3311680488.428499997
2334491.27790001680327.5201999992334446.93599111680148.956062436
#Sta/Elev= 30
       0   78.44    1.62   78.37   852.3   75.64 1070.04   70.05 1260.54   66.25
 1747.73   64.71  1859.6    68.5 3701.36   67.16 3771.14   67.66 3796.02    63.6
 3848.68   62.14 3931.58   63.15 4121.27   66.82 4821.66   66.81 4881.99   63.92
 5125.64   65.57 5867.23   68.84  6403.2   66.75 7046.23   65.56 7323.08   69.36
 7618.35   63.51 7707.92   60.27 7760.35   53.23 7777.73   58.12 7802.24   58.83
 7837.05    65.1 7876.54   92.97 7936.12   98.01  7965.3   97.17 8102.52   98.58
#Mann= 17 ,-1 , 0
       0     .09       0    1.62    .045       0 1070.04     .08       0
 1260.54    .075       0 1747.73    .075       0  1859.6    .045       0
 3701.36     .09       0 3931.58    .085       0 4121.27    .045       0
 4821.66    .075       0 5125.64    .045       0  6403.2     .05       0
 7618.35     .08       0 7707.92     .05       0 7802.24    .085       0
 7936.12    .035       0  7965.3    .045       0
Bank Sta=7707.92,7802.24
XS Rating Curve= 0 ,0
Exp/Cntr=0.3,0.1

Type RM Length L Ch R = 1 ,368024  ,662.93,2055.53,1056.14
XS GIS Cut Line= 3
2341367.11711296682265.6456549912336314.03717361679463.212079361
2335157.63664311678306.811548859
#Sta/Elev= 30
       0   73.03  150.22   74.22  279.49   68.38  376.74    62.9  563.43   65.34
  1607.6   67.76 1833.66    64.7  2165.5    67.6 2322.37   63.75 2767.48   66.65
 3448.79   66.79 3517.59   57.65 3598.26   57.89 3664.53   64.96 3739.09   67.68
 4297.18   62.19 4590.48   68.16 4722.93   58.44 4930.68   63.55 5703.26   62.95
 6211.09   64.11 6581.16   60.64  6753.5   65.63 6796.02   62.95  6853.5    53.1
 6877.57   52.69 6881.97    60.2 6975.43   81.43 6996.92   82.44 7413.57   79.53
#Mann= 14 ,-1 , 0
       0    .045       0  279.49    .075       0  563.43    .045       0
  2165.5     .09       0 2767.48    .045       0 3448.79     .09       0
 3664.53    .075       0 4590.48     .08       0 5703.26    .085       0
 6211.09     .08       0 6796.02     .05       0 6881.97    .085       0
 6975.43    .035       0 6996.92    .045       0
Bank Sta=6796.02,6881.97
XS Rating Curve= 0 ,0
Exp/Cntr=0.5,0.3

Type RM Length L Ch R = 1 ,365969  ,150.7,105.14,215.65
BEGIN DESCRIPTION:
Surveyed Section
END DESCRIPTION:
XS GIS Cut Line= 6
2341309.79685421680806.099170506 2339203.4334314680556.959410816
2338861.43248855680029.2361016572338111.74830258 679730.26839003
 2337683.6808973679064.3857595922336388.26881346678454.823104158
#Sta/Elev= 30
       0   71.54  108.07   66.91   382.3   61.59  829.09   63.65 1157.94   65.07
 1627.97   67.07 1779.05   63.18 2139.83   65.75 2398.38   65.65  2982.6   65.55
  3023.4   64.53 3079.33   56.87 3176.05    63.8 3357.03   64.41 3365.16   64.51
 3563.86   63.93 3810.79   65.61 3922.92   66.25 4206.45   65.43 4289.54   66.11
4653.602   65.08 4658.89   60.464669.056   54.714710.309   52.144756.635   60.51
 4989.64   68.33 5370.78   67.06 5483.62   67.54 5656.05   74.81 5810.02   80.44
#Mann= 20 ,-1 , 0
       0    .065       0  108.07    .075       0   382.3    .045       0
  829.09     .05       0 1157.94    .045       0 1627.97     .09       0
 2139.83    .045       0 2398.38     .09       0 3357.03     .04       0
 3365.16    .075       0 3563.86     .04       0 3810.79    .055       0
 3922.92     .07       0 4206.45     .08       0 4289.54     .04       0
4653.602     .05       04756.635     .08       0 4989.64    .035       0
 5370.78     .08       0 5656.05    .035       0
#XS Ineff= 2 , 0
       0  4640.2      64 4864.81       0   67.88
Permanent Ineff=
       F       F
Bank Sta=4658.89,4756.635
XS Rating Curve= 0 ,0
Exp/Cntr=0.5,0.3

Type RM Length L Ch R = 3 ,365924  ,,,
BEGIN DESCRIPTION:
Woodbridge Rd
END DESCRIPTION:
Bridge Culvert--1,0,-1,-1, 0
Deck Dist Width WeirC Skew NumUp NumDn MinLoCord MaxHiCord MaxSubmerge Is_Ogee
32,23,2.6,0, 60, 60, , , 0.98, 0, 1,1,,
       0    81.2  166.28  353.23   463.4  705.35  802.44  816.75  833.33 1010.42
 1026.85 1047.35 1197.89 1297.94 1325.91 1350.75 1419.74 1537.28 1681.54 1863.97
 1905.36 2069.16 2091.46 2109.01 2137.74 2168.63  2203.2 2233.81 2261.17 2278.08
 2380.88 2422.44  2430.8 2448.08 2481.34  2511.8 2617.03 2657.16 2704.66  2752.6
 2791.88 2820.06 2873.88 2909.92 2925.91 3047.594329.5434429.5144479.6674489.048
4640.1984640.1984713.246 4804.81 4804.815058.095 5527.14 5649.69 5724.29 5803.37
   69.16   66.86   65.15   62.85   62.47   63.67   63.93   63.57   64.14   65.39
   65.12   65.67   65.82   65.61      65   65.48   65.11   65.69   65.49   63.45
   64.85   64.68   65.32   64.65   65.74   64.96   65.84   65.19   65.48    64.9
   65.57   64.94   65.46   64.92   65.44   64.93   65.06   63.88   65.72   65.27
   65.83   65.17   65.43   64.74   65.22   65.75   67.52   68.43   68.47   67.93
   69.95   69.95   70.03   69.88   69.88   67.88   71.32   75.18   78.55    81.3
                                                                                
                                                                                
                                                                                
                                                                                
                                                                                
            68.4   68.48   68.33
       0    81.2  166.28  353.23   463.4  705.35  802.44  816.75  833.33 1010.42
 1026.85 1047.35 1197.89 1297.94 1325.91 1350.75 1419.74 1537.28 1681.54 1863.97
 1905.36 2069.16 2091.46 2109.01 2137.74 2168.63  2203.2 2233.81 2261.17 2278.08
 2380.88 2422.44  2430.8 2448.08 2481.34  2511.8 2617.03 2657.16 2704.66  2752.6
 2791.88 2820.06 2873.88 2909.92 2925.91 3047.594329.5434429.5144479.6674489.048
4640.1984640.1984713.246 4804.81 4804.815058.095 5527.14 5649.69 5724.29 5803.37
   69.16   66.86   65.15   62.85   62.47   63.67   63.93   63.57   64.14   65.39
   65.12   65.67   65.82   65.61      65   65.48   65.11   65.69   65.49   63.45
   64.85   64.68   65.32   64.65   65.74   64.96   65.84   65.19   65.48    64.9
   65.57   64.94   65.46   64.92   65.44   64.93   65.06   63.88   65.72   65.27
   65.83   65.17   65.43   64.74   65.22   65.75   67.52   68.43   68.47   67.93
   69.95   69.95   70.03   69.88   69.88   67.88   71.32   75.18   78.55    81.3
                                                                                
                                                                                
                                                                                
                                                                                
                                                                                
            68.4   68.48   68.33
Pier Skew, UpSta & Num, DnSta & Num=  ,4658.759, 2 ,4658.759, 2 , 0 , 0 , 0 ,,
       1       1
      50   68.48
       1       1
      50   68.48
Pier Skew, UpSta & Num, DnSta & Num=  ,4676.993, 2 ,4676.993, 2 , 0 , 0 , 0 ,,
       1       1
      50   68.48
       1       1
      50   68.48
Pier Skew, UpSta & Num, DnSta & Num=  ,4695.03, 2 ,4695.03, 2 , 0 , 0 , 0 ,,
       1       1
      50   68.48
       1       1
      50   68.48
Pier Skew, UpSta & Num, DnSta & Num=  ,4713.246, 2 ,4713.246, 2 , 0 , 0 , 0 ,,
       1       1
      50   68.48
       1       1
      50   68.48
Pier Skew, UpSta & Num, DnSta & Num=  ,4731.318, 2 ,4731.318, 2 , 0 , 0 , 0 ,,
       1       1
      50   68.48
       1       1
      50   68.48
Pier Skew, UpSta & Num, DnSta & Num=  ,4749.666, 2 ,4749.666, 2 , 0 , 0 , 0 ,,
       1       1
      50   68.48
       1       1
      50   68.48
Pier Skew, UpSta & Num, DnSta & Num=  ,4767.925, 2 ,4767.925, 2 , 0 , 0 , 0 ,,
       1       1
      50   68.48
       1       1
      50   68.48
Pier Skew, UpSta & Num, DnSta & Num=  ,4786.186, 2 ,4786.186, 2 , 0 , 0 , 0 ,,
       1       1
      50   68.48
       1       1
      50   68.48
BR Coef=-1 , 0 , 0 ,, 0 ,,,0.8,0,,0,
WSPro=,,,, 1 ,,,, 0 ,,,, 0 ,,,,-1 ,-1 ,-1 , 0 , 0 , 0 , 0 , 0
BC Design=,, 0 ,, 0 ,,,,,,
BC Use User HTab Curves=0
BC User HTab FreeFlow(D)= 0