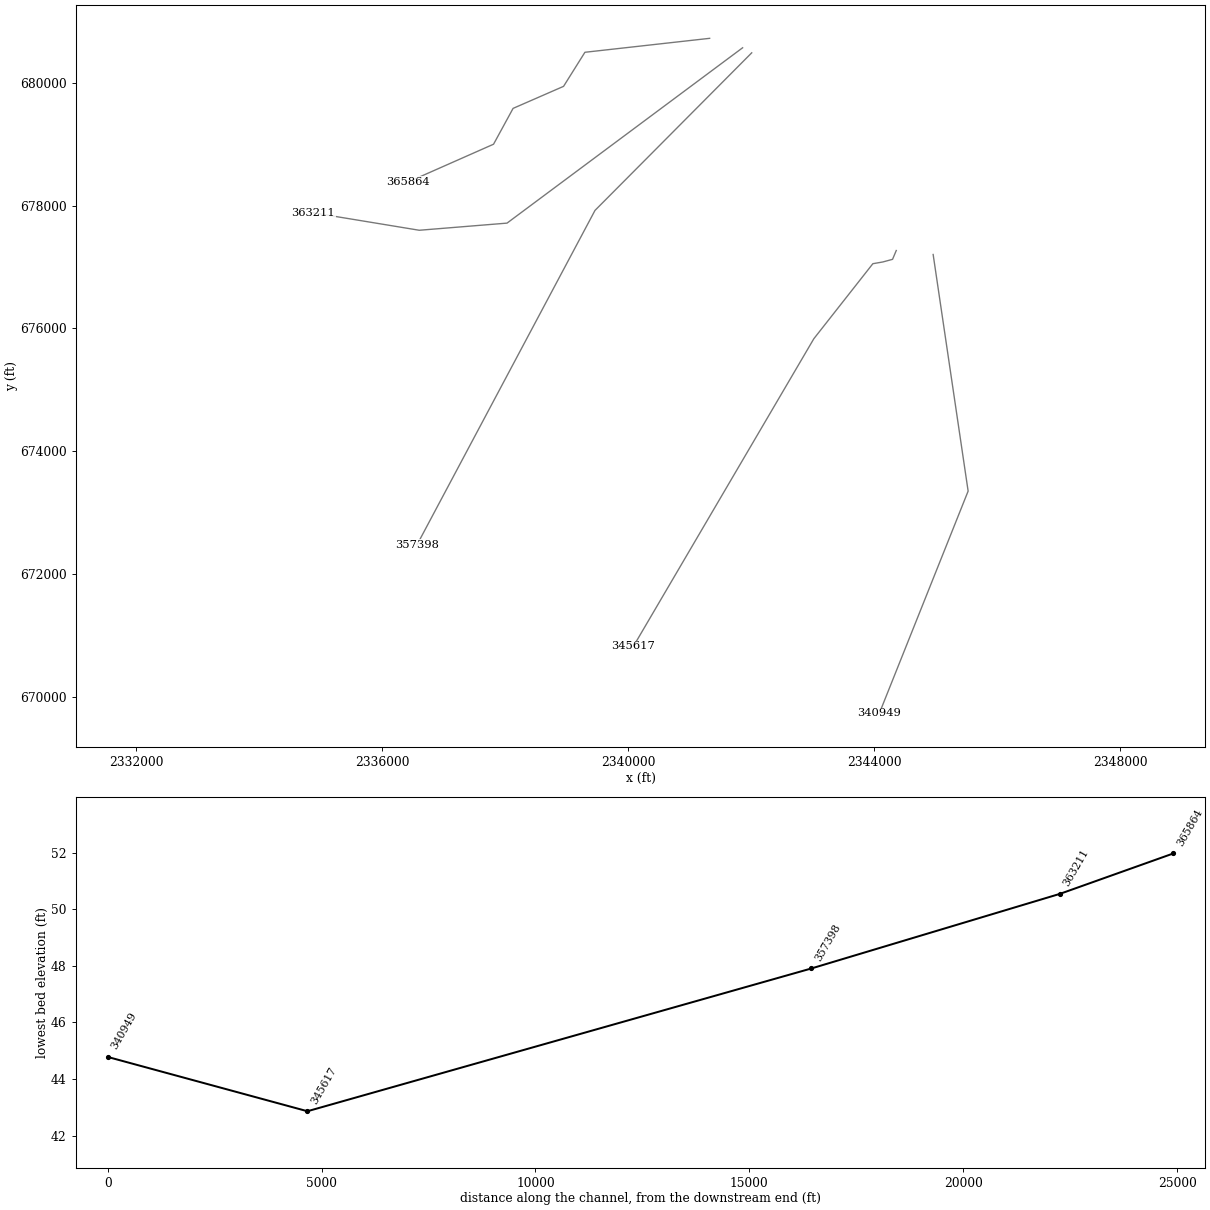
HEC-RAS study dtl_contentnea_crk_ds.prj: dtl_contentnea_crk_ds

--- dtl_contentnea_crk_ds.g01 (geometry) --- (continued)

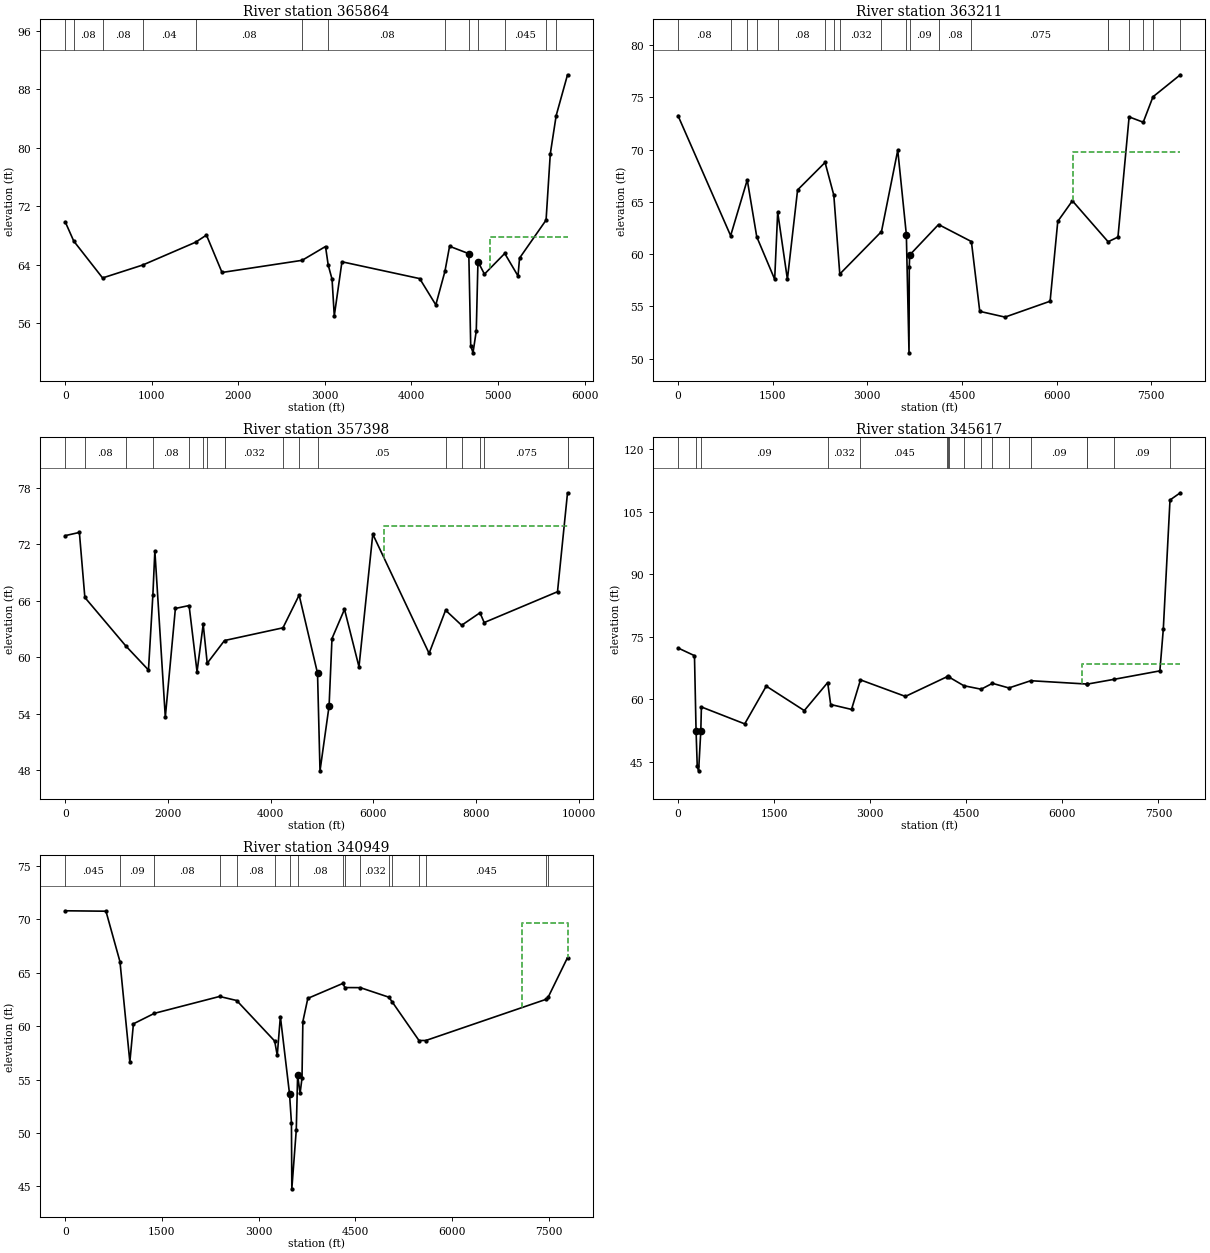
Type RM Length L Ch R = 1 ,365864  ,1499.42,2652.63,1213.45
BEGIN DESCRIPTION:
Surveyed Section
END DESCRIPTION:
XS GIS Cut Line= 6
2341323.78327212680722.5131307542339295.08379778680495.545371875
2338947.62698174679940.7352946552338126.62015027  679582.0701942
2337808.83633028678998.7028391962336422.02873817678384.790953681
#Sta/Elev= 30
       0   69.89   98.64   67.26   431.7   62.22   895.9   63.99 1505.16    67.1
 1631.47   68.08  1811.4   62.97 2736.44   64.63 3006.78   66.52 3038.17   63.97
 3082.41   62.05 3108.11   57.04 3196.68   64.43 4094.79   62.13    4281   58.54
 4386.08   63.11 4439.99   66.554662.146   65.54 4684.12   52.96 4710.51   51.98
4748.307   54.974767.821   64.464842.714   62.74 5077.16   65.57 5230.54   62.49
 5248.25   64.93  5554.7   70.13 5603.24   79.17 5671.33   84.42 5802.47      90
#Mann= 13 ,-1 , 0
       0    .055       0   98.64     .08       0   431.7     .08       0
   895.9     .04       0 1505.16     .08       0 2736.44     .07       0
 3038.17     .08       0 4386.08     .07       04662.146     .05       0
4767.821     .08       0 5077.16    .045       0  5554.7    .085       0
 5671.33     .04       0
#XS Ineff= 2 , 0
       0    4552      60 4904.81       0   67.88
Permanent Ineff=
       F       F
Bank Sta=4662.146,4767.821
XS Rating Curve= 0 ,0
Exp/Cntr=0.5,0.3

Type RM Length L Ch R = 1 ,363211  ,674.32,5812.85,3485.25
XS GIS Cut Line= 4
2341860.16754788680568.7824523752338027.99468189677713.900177583
2336600.74945848677597.6362336282334873.04435727677882.422788784
#Sta/Elev= 30
       0   73.25  834.38   61.76 1097.92    67.1 1248.39   61.65 1532.44   57.59
 1580.15   64.01 1734.03   57.59 1895.61   66.14 2331.18   68.77 2469.72   65.64
 2564.46   58.09 3225.2862.15506 3483.35   69.94 3619.47   61.87 3661.76   50.55
 3665.65   58.73 3672.24   59.91 4129.73   62.83 4650.42    61.2 4783.07   54.52
 5183.59   53.97 5898.16   55.49 6019.57   63.13 6251.14    65.1 6817.59   61.18
 6973.59   61.63 7150.39   73.13 7374.11   72.62 7528.57   75.05 7961.69   77.16
#Mann= 19 ,-1 , 0
       0     .08       0  834.38    .055       0 1097.92     .08       0
 1248.39    .032       0 1580.15     .08       0 2331.18     .07       0
 2469.72     .04       0 2564.46    .032       0 3225.28     .04       0
 3619.47     .05       0 3672.24     .09       0 4129.73     .08       0
 4650.42    .075       0 6817.59    .075       0 6817.59    .085       0
 7150.39    .045       0 7374.11    .085       0 7528.57    .045       0
 7961.69    .085       0
#XS Ineff= 2 , 0
                         6254.02            69.8
Permanent Ineff=
       F       F
Bank Sta=3619.47,3672.24
XS Rating Curve= 0 ,0
Exp/Cntr=0.3,0.1

Type RM Length L Ch R = 1 ,357398  ,4328.5,11781.18,5541.58
XS GIS Cut Line= 3
2342008.18077476680486.5528818972339459.06408946677920.990282506
2336564.58320808672477.392715827
#Sta/Elev= 30
       0   72.94  275.77   73.28  382.47   66.36 1176.77   61.22 1621.28   58.64
 1706.95   66.62 1745.67   71.32 1949.19   53.62 2145.45   65.19 2412.22    65.5
 2567.11   58.45  2687.1   63.51 2765.35   59.36 3101.8561.77705 4240.47   63.13
 4555.45   66.61 4913.46    58.3 4961.75   47.91  5138.5   54.81 5195.18   61.99
 5438.67    65.1 5720.87   58.98 5989.47    73.1 7086.04   60.41 7407.39      65
  7719.9    63.4 8076.94   64.73 8159.11   63.69 9586.79   66.97 9781.93    77.5
#Mann= 18 ,-1 , 0
       0    .045       0  382.47     .08       0 1176.77    .032       0
 1706.95     .08       0 2412.22     .07       0  2687.1     .04       0
 2765.35    .032       0 3101.85     .04       0 3101.85    .032       0
 4240.47     .04       0 4555.45     .08       0 4913.46     .05       0
 7407.39     .09       0  7719.9     .07       0 8076.94     .09       0
 8159.11    .075       0 9781.93    .075       0 9781.93    .035       0
#XS Ineff= 2 , 0
                         6216.46              74
Permanent Ineff=
       F       F
Bank Sta=4913.46,5138.5
XS Rating Curve= 0 ,0
Exp/Cntr=0.3,0.1

Type RM Length L Ch R = 1 ,345617  ,1579.31,4667.93,4013.66
XS GIS Cut Line= 6
2344359.69860892677268.029201776    2344299.0979677124.270700008
2344140.01719999677081.1993999932343978.84600002677053.168500021
2343018.72192977675831.4328823392340085.57521391670826.112864703
#Sta/Elev= 30
       0   72.35  257.28    70.5  282.13  52.415  300.26   44.04  321.96   42.86
  356.22   52.46  365.28   58.19 1041.57   54.13 1377.65   63.19 1971.52   57.32
 2336.78   64.05  2383.5   58.78  2708.8    57.6 2848.83   64.69 3550.16   60.72
 4199.14   65.44 4210.12  65.588 4231.29   65.36 4461.83   63.29 4732.37   62.45
  4908.8   63.86 5165.22   62.75 5507.11   64.49 6381.44   63.69 6387.71   63.67
 6814.29   64.84 7522.68   66.85 7576.33   76.89 7680.78  107.86 7841.54  109.59
#Mann= 17 ,-1 , 0
       0    .045       0  282.13     .05       0  356.22     .09       0
 2336.78    .032       0 2848.83    .045       0 4199.14    .045       0
 4210.12    .035       0 4231.29    .055       0 4461.83     .08       0
 4732.37    .045       0  4908.8     .08       0 5165.22    .045       0
 5507.11     .09       0 6381.44    .075       0 6387.71     .09       0
 6814.29     .09       0 7680.78    .045       0
#XS Ineff= 2 , 0
       0                    6300       0   68.52
Permanent Ineff=
       F       F
Bank Sta=282.13,356.22
XS Rating Curve= 0 ,0
Exp/Cntr=0.3,0.1

Type RM Length L Ch R = 1 ,340949  ,3645.58,7342.25,712.31
XS GIS Cut Line= 3
2344959.56030397677203.1532370152345528.67832346673350.662028104
2344083.99412014669731.655134901
#Sta/Elev= 30
       0   70.78  631.92   70.74  849.22   66.02 1002.58   56.64 1057.85   60.21
  1382.9   61.19 2394.1862.76802 2659.07   62.39 3248.85    58.6 3288.76   57.26
  3337.2   60.89  3479.1   53.66 3508.77   50.96  3514.8   44.78 3583.72   50.28
  3604.8   55.42    3643   53.71 3672.58   55.13 3685.93   60.42 3762.94   62.59
 4306.87   63.99 4338.04    63.6 4577.22 63.5922 5019.75    62.7 5075.06   62.23
 5487.21   58.65 5593.17   58.65 7464.5762.51367 7494.17   62.74 7791.01    66.4
#Mann= 17 ,-1 , 0
       0    .045       0  849.22     .09       0  1382.9     .08       0
 2394.18    .045       0 2659.07     .08       0 3248.85     .09       0
  3479.1     .05       0  3604.8     .08       0 4306.87    .035       0
 4338.04     .04       0 4577.22    .032       0 5019.75     .04       0
 5075.06    .045       0 5487.21     .08       0 5593.17    .045       0
 7464.57     .09       0 7494.17    .045       0
#XS Ineff= 2 , 0
                         7084.08           69.63
Permanent Ineff=
       F       F
Bank Sta=3479.1,3604.8
XS Rating Curve= 0 ,0
Exp/Cntr=0.5,0.3