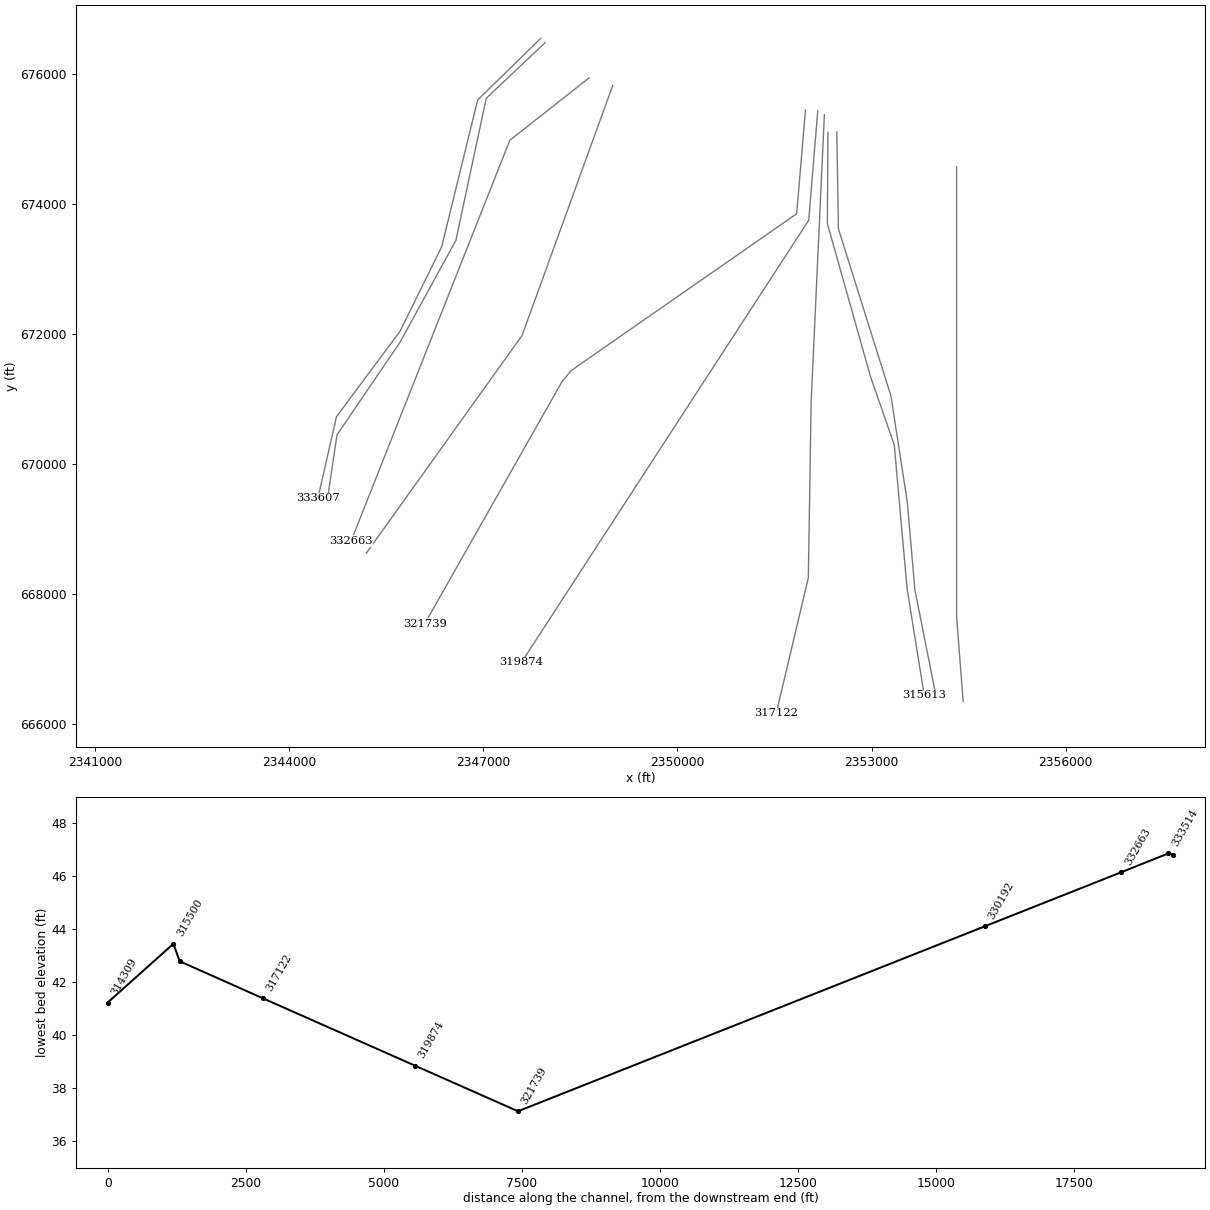
HEC-RAS study dtl_contentnea_crk_ds.prj: dtl_contentnea_crk_ds

--- dtl_contentnea_crk_ds.g01 (geometry) --- (continued)

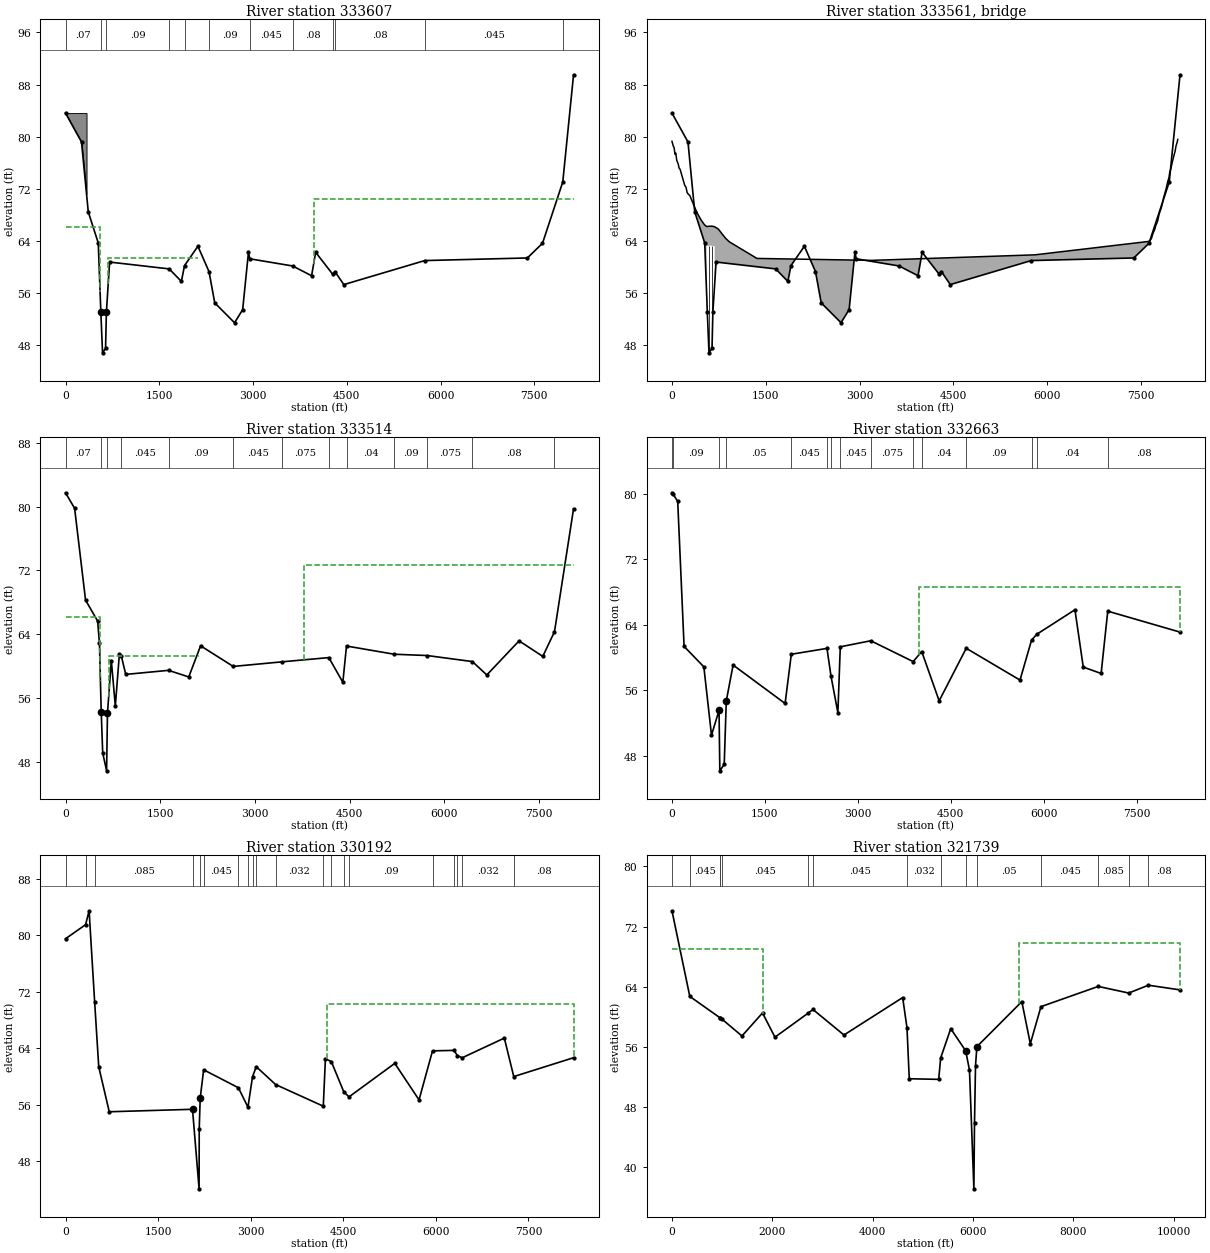
Type RM Length L Ch R = 1 ,333607  ,87.25,92.18,110.81
BEGIN DESCRIPTION:
Surveyed Section
END DESCRIPTION:
XS GIS Cut Line= 6
 2347889.0182268676555.6069916932346913.97494379675605.660193294
2346358.53662141673344.5838367342345716.25985925672045.284162238
2344733.18318245670726.3229542232344446.45248507669469.623269081
#Sta/Elev= 30
       0   83.62  255.98   79.18  364.07   68.45 523.971   63.67  565.53      53
 592.229    46.8 640.639   47.49 654.266   53.07 705.438   60.74 1658.71   59.69
 1853.64   57.77 1904.15    60.2 2117.96   63.17 2295.87   59.27 2387.27   54.47
 2704.26   51.42 2834.03   53.44 2927.09   62.27 2947.65   61.24 3632.75   60.14
  3936.4   58.64  4001.7   62.24 4275.59   58.85 4310.54   59.27 4452.32   57.28
 5747.38   60.97 7388.35   61.37 7630.16   63.62 7954.67   73.04 8126.96    89.5
#Mann= 12 ,-1 , 0
       0     .07       0  565.53     .05       0 654.266     .09       0
 1658.71     .09       0 1904.15    .045       0 2295.87     .09       0
 2947.65    .045       0 3632.75     .08       0 4275.59    .035       0
 4310.54     .08       0 5747.38    .045       0 7954.67     .05       0
#XS Ineff= 3 ,-1
       0   553.1    66.2     683    2118    61.3  3969.5 9978.4470.44416
Permanent Ineff=
       F       F       F
#Block Obstruct= 1 ,-1
       0  336.3183.62001
Bank Sta=565.53,654.266
XS Rating Curve= 0 ,0
Exp/Cntr=0.5,0.3

Type RM Length L Ch R = 3 ,333561  ,,,
BEGIN DESCRIPTION:
Rt 222/111, S. Main St
END DESCRIPTION:
Bridge Culvert--1,0,-1,-1, 0
Deck Dist Width WeirC Skew NumUp NumDn MinLoCord MaxHiCord MaxSubmerge Is_Ogee
32,32,2.6,0, 61, 61, , , 0.98, 0, 0,0,,
       0   20.29    34.3   47.78   61.58      76  100.31  114.28  131.36  152.19
  182.68  204.41  224.72  242.25  264.22 284.688 342.396 400.471 460.019 517.339
 553.101 553.101 596.439 639.447 683.539 683.539 742.333 802.696 860.601 917.401
 1358.86  3194.4 5806.81 7608.23  7623.9 7637.65 7656.59 7670.34 7687.05 7704.51
 7719.07 7740.19 7755.14 7771.12 7790.31 7808.02 7822.24 7836.98 7863.58  7887.5
 7902.99 7931.33 7949.33    7963 7979.84 8001.85 8031.29 8047.78 8063.82 8082.86
 8090.97
   79.28   78.57   78.31    77.3   77.46   76.37   75.79   75.17   74.96   74.24
   73.23   72.52   72.23   71.42   71.13   70.97   69.63   68.32   67.29    66.5
    66.2    66.2   66.24   66.25   66.16   66.16    65.8   65.05   64.36   63.85
    61.3      61   61.85   63.89   63.93   63.85   64.18   64.36   64.93   65.38
   65.65   66.38   66.68   67.11      68   68.56   68.91   69.42   70.56    71.4
   71.92   73.14   73.65   74.57   75.03   76.02   77.16   77.75   78.59   79.19
   79.57
                                                                                
                                                                                
            63.2   63.24   63.25   63.16
                                                                                
                                                                                
                                                                                
        
       0   20.29    34.3   47.78   61.58      76  100.31  114.28  131.36  152.19
  182.68  204.41  224.72  242.25  264.22 284.688 342.396 400.471 460.019 517.339
 553.101 553.101 596.439 639.447 683.539 683.539 742.333 802.696 860.601 917.401
 1358.86  3194.4 5806.81 7608.23  7623.9 7637.65 7656.59 7670.34 7687.05 7704.51
 7719.07 7740.19 7755.14 7771.12 7790.31 7808.02 7822.24 7836.98 7863.58  7887.5
 7902.99 7931.33 7949.33    7963 7979.84 8001.85 8031.29 8047.78 8063.82 8082.86
 8090.97
   79.28   78.57   78.31    77.3   77.46   76.37   75.79   75.17   74.96   74.24
   73.23   72.52   72.23   71.42   71.13   70.97   69.63   68.32   67.29    66.5
    66.2    66.2   66.24   66.25   66.16   66.16    65.8   65.05   64.36   63.85
    61.3      61   61.85   63.89   63.93   63.85   64.18   64.36   64.93   65.38
   65.65   66.38   66.68   67.11      68   68.56   68.91   69.42   70.56    71.4
   71.92   73.14   73.65   74.57   75.03   76.02   77.16   77.75   78.59   79.19
   79.57
                                                                                
                                                                                
            63.2   63.24   63.25   63.16
                                                                                
                                                                                
                                                                                
        
Pier Skew, UpSta & Num, DnSta & Num=  ,596.439, 2 ,596.439, 2 , 0 , 0 , 0 ,,
       3       3
      45   63.25
       3       3
      45   63.25
Pier Skew, UpSta & Num, DnSta & Num=  ,639.447, 2 ,639.447, 2 , 0 , 0 , 0 ,,
       3       3
      45   63.25
       3       3
      45   63.25
BR Coef=-1 , 0 , 0 ,, 0 ,,,0.8,0,,0,
WSPro=,,,, 1 ,,,, 0 ,,,, 0 ,,,,-1 ,-1 ,-1 , 0 , 0 , 0 , 0 , 0
BC Design=,, 0 ,, 0 ,,,,,,
BC Use User HTab Curves=0
BC User HTab FreeFlow(D)= 0

Type RM Length L Ch R = 1 ,333514  ,851.19,851.77,380.63
BEGIN DESCRIPTION:
Surveyed Section
END DESCRIPTION:
XS GIS Cut Line= 6
2347956.48139718676488.6725018022347046.92830822675632.334615648
2346577.92211422 673443.134412872345715.82724503671875.358511493
2344740.96891193670445.8087916672344593.64890264 669458.21909976
#Sta/Elev= 30
       0   81.74  144.22   79.79  317.55   68.27 508.823   65.64 537.903   62.84
  565.53   54.23 589.069   49.09 650.779   46.85  664.27   54.08 725.363   60.69
 788.773   54.97 852.726   61.47  883.23   61.27  953.88   58.95 1631.31   59.46
 1951.46   58.63 2138.84   62.54 2655.31   59.95 3431.55   60.53 4169.18   61.06
 4390.98   57.96 4449.11   62.51 5205.24   61.48 5724.07   61.32  6442.4   60.56
 6670.67   58.88 7181.59   63.16 7556.69   61.21  7742.3   64.31 8043.95   79.73
#Mann= 13 ,-1 , 0
       0     .07       0  565.53     .05       0  664.27    .055       0
  883.23    .045       0 1631.31     .09       0 2655.31    .045       0
 3431.55    .075       0 4169.18     .09       0 4449.11     .04       0
 5205.24     .09       0 5724.07    .075       0  6442.4     .08       0
  7742.3    .055       0
#XS Ineff= 3 ,-1
       0   553.1    66.2  683.54    2120    61.3 3783.72  9707.672.62386
Permanent Ineff=
       F       F       F
Bank Sta=565.53,664.27
XS Rating Curve= 0 ,0
Exp/Cntr=0.5,0.3

Type RM Length L Ch R = 1 ,332663  ,850.11,2470.71,1179.17
XS GIS Cut Line= 3
 2348636.9382761675948.1750401852347411.14561872674985.052237958
2344959.56030397 668812.31064187
#Sta/Elev= 30
       0   80.15   12.27   80.06   92.67   79.09  195.58   61.36  514.51   58.86
  637.95    50.5  759.69   53.54   772.5   46.14   843.4   46.93  876.65   54.69
  986.84   59.08 1825.98   54.38 1926.34    60.4 2502.02 61.1161 2566.81   57.73
 2678.01   53.26 2716.88   61.31 3208.92   62.05 3893.67    59.5 4031.45   60.73
 4312.68    54.7 4749.82   61.13 5617.67   57.24 5803.61   62.11 5885.62   62.83
 6504.78   65.84 6638.85   58.83 6927.34   58.05 7034.25   65.67 8200.66   63.11
#Mann= 15 ,-1 , 0
       0     .09       0   12.27     .09       0  759.69     .05       0
  876.65     .05       0 1926.34    .045       0 2502.02     .09       0
 2566.81    .032       0 2716.88    .045       0 3208.92    .075       0
 3893.67     .09       0 4031.45     .04       0 4749.82     .09       0
 5803.61     .04       0 5885.62     .04       0 7034.25     .08       0
#XS Ineff= 2 , 0
                         3989.27           68.65
Permanent Ineff=
       F       F
Bank Sta=759.69,876.65
XS Rating Curve= 0 ,0
Exp/Cntr=0.3,0.1

Type RM Length L Ch R = 1 ,330192  ,3727.35,8452.91,1281.95
XS GIS Cut Line= 3
2349001.75751936675831.4328823392347600.85162522671978.941673443
2345193.04461966668622.604635373
#Sta/Elev= 30
       0    79.5  325.08   81.49  382.38   83.46   472.4   70.51  538.23   61.38
  708.73   55.01 2057.49   55.36 2163.95    44.1 2166.16   52.57 2181.72   56.92
 2237.73   60.95 2800.66   58.41 2955.39   55.66 3029.46   59.97 3090.36   61.39
 3403.92   58.86 4175.8955.79959 4210.34    62.5 4305.93   62.12 4508.38   57.82
 4593.15   57.12  5334.3   61.86 5727.06   56.69 5945.34 63.6291 6292.64    63.7
 6347.78   62.97 6425.97   62.65 7108.55   65.44 7261.31   59.99 8229.98   62.66
#Mann= 20 ,-1 , 0
       0    .045       0  325.08     .09       0   472.4    .085       0
 2057.49     .05       0 2181.72     .09       0 2237.73    .045       0
 2800.66    .075       0 2955.39     .09       0 3029.46    .075       0
 3090.36    .045       0 3403.92    .032       0 4175.89     .04       0
 4305.93     .09       0 4508.38    .032       0 4593.15     .09       0
 5945.34    .045       0 6292.64     .09       0 6347.78     .08       0
 6425.97    .032       0 7261.31     .08       0
#XS Ineff= 2 , 0
                         4230.77           70.27
Permanent Ineff=
       F       F
Bank Sta=2057.49,2181.72
XS Rating Curve= 0 ,0
Exp/Cntr=0.3,0.1

Type RM Length L Ch R = 1 ,321739  ,556.56,1864.64,1854.88
BEGIN DESCRIPTION:
Surveyed Section
END DESCRIPTION:
XS GIS Cut Line= 6
2351978.68254444675452.0208693442351842.71357055 673853.47495313
2348351.23960002671432.496600002    2348264.6556671318.565200001
    2348217.9232671268.0283000022346096.69683252667537.224234566
#Sta/Elev= 30
       0    74.1  355.29   62.71  955.03   59.88  956.07   59.88  991.28   59.72
 1394.81   57.45 1804.34   60.51 2052.68   57.29 2714.89   60.49 2809.1560.97702
 3427.97   57.58 4597.73   62.56    4684   58.53 4729.17   51.76 5315.58   51.68
 5355.21   54.53 5555.91   58.42 5853.57   55.48 5929.27   52.92 6017.13   37.12
  6029.5   45.92 6049.82   53.52 6077.23   56.03 6972.66   62.02 7141.84   56.42
 7354.35   61.35 8494.7964.03983 9102.82   63.16  9495.4    64.210125.35   63.58
#Mann= 15 ,-1 , 0
       0     .08       0  355.29    .045       0  955.03     .04       0
  956.07    .035       0  991.28    .045       0 2714.89     .09       0
 2809.15    .045       0    4684    .032       0 5355.21    .045       0
 5853.57     .05       0 6077.23     .05       0 7354.35    .045       0
 8494.79    .085       0 9102.82     .05       0  9495.4     .08       0
#XS Ineff= 2 , 0
         1813.95   69.06 6923.08           69.82
Permanent Ineff=
       F       F
Bank Sta=5853.57,6077.23
XS Rating Curve= 0 ,0
Exp/Cntr=0.3,0.1

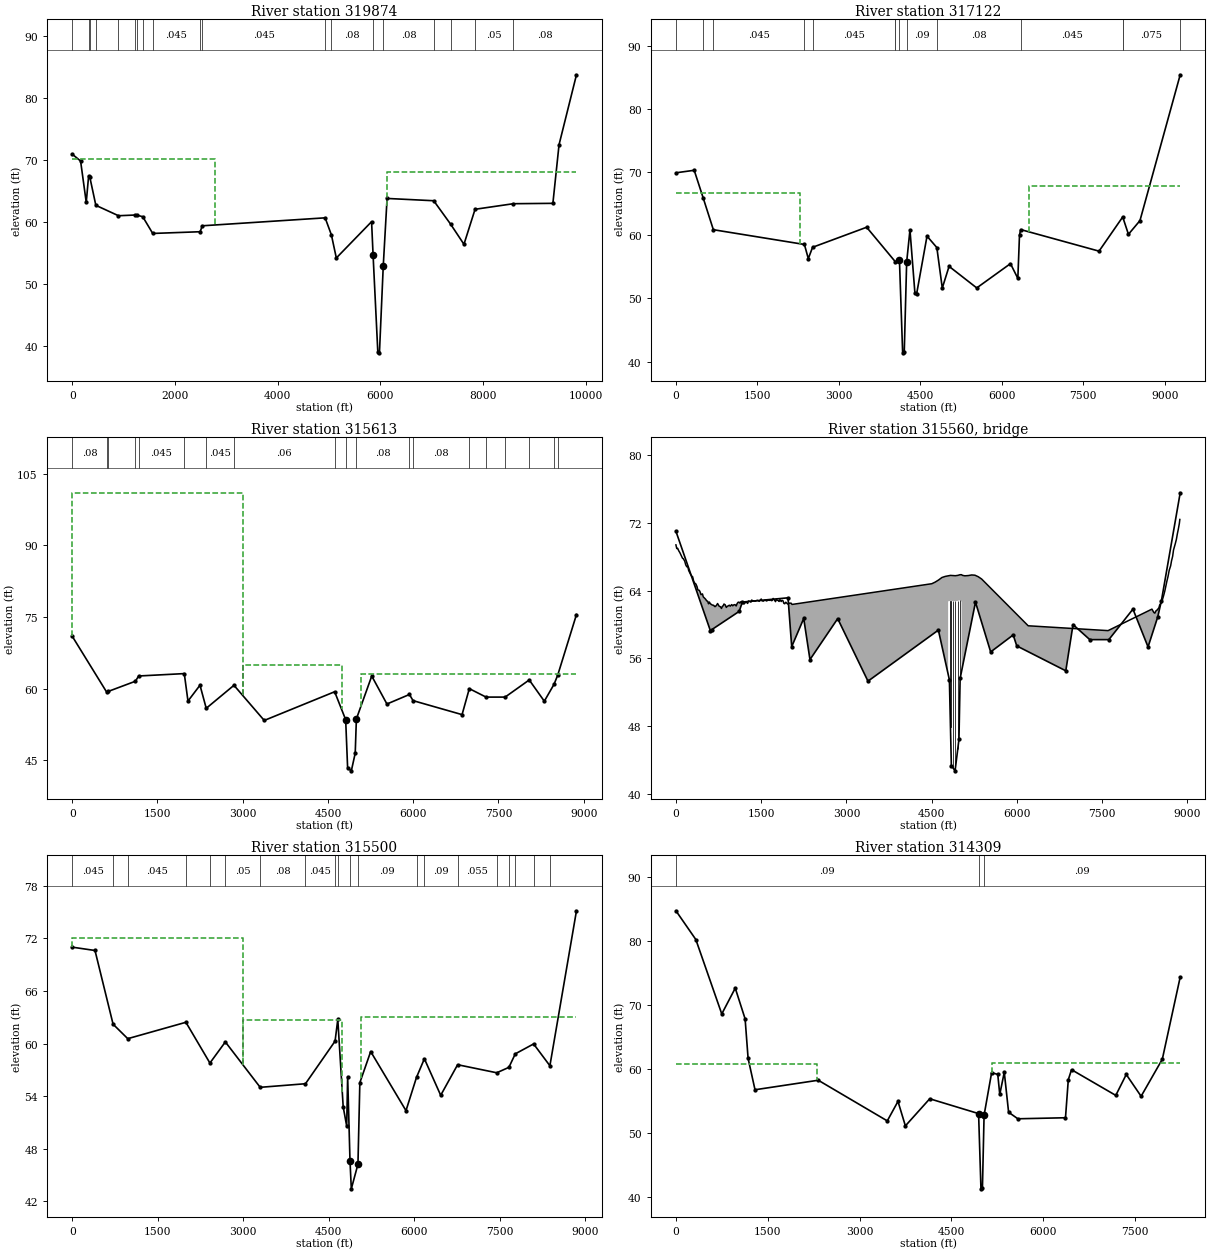
Type RM Length L Ch R = 1 ,319874  ,659.65,2752.25,3421.56
XS GIS Cut Line= 3
2352168.38855094675437.4280996022352028.56062025673752.454285204
 2347591.9670316666943.706032217
#Sta/Elev= 30
       0   70.91  163.59    69.8  273.57   63.12  320.05   67.42  342.63   67.22
  460.44   62.65  901.24   60.97 1217.36   61.08 1256.63   61.07 1373.46   60.81
 1567.84   58.11 2490.6858.38724 2533.8759.34591 4924.41   60.63 5046.15   57.88
 5142.24   54.15  5828.5   60.01 5858.05   54.57 5950.27   38.92 5981.75   38.84
 6055.87   52.87 6130.14   63.76  7038.1   63.39 7366.99   59.61 7626.97   56.36
 7843.13   62.01 8588.27   62.91 9358.21   62.97 9478.17   72.44 9817.41   83.72
#Mann= 19 ,-1 , 0
       0     .08       0  320.05    .045       0  342.63     .08       0
  460.44     .04       0  901.24    .045       0 1217.36    .035       0
 1256.63    .045       0 1373.46     .05       0 1567.84    .045       0
 2490.68     .09       0 2533.87    .045       0 4924.41    .085       0
 5046.15     .08       0 5858.05     .05       0 6055.87     .08       0
  7038.1     .05       0 7366.99    .085       0 7843.13     .05       0
 8588.27     .08       0
#XS Ineff= 2 , 0
         2772.81    70.2 6121.52           67.96
Permanent Ineff=
       F       F
Bank Sta=5858.05,6055.87
XS Rating Curve= 0 ,0
Exp/Cntr=0.3,0.1

Type RM Length L Ch R = 1 ,317122  ,682.33,1508.86,1447.51
XS GIS Cut Line= 4
2352270.53793906675379.0570206792352066.23916283670957.447792277
2352022.46085364668243.192622378 2351526.3066828666156.426550865
#Sta/Elev= 30
       0   69.92  336.67   70.32  501.44   65.95  689.15    60.9 2366.04   58.56
 2437.65   56.32 2516.4758.11177 3511.92   61.29 4040.28   55.82 4115.91    56.1
 4174.95   41.38 4204.48   41.51  4248.9   55.78 4309.71   60.87 4401.26    50.8
 4432.07   50.71 4623.58   59.88 4804.5158.07154 4904.74   51.65 5029.76   55.09
 5539.29   51.67 6160.27   55.52  6296.1   53.18 6326.67   60.06 6348.75   60.92
 7791.34    57.5 8227.28   62.92 8332.71   60.17 8544.76   62.34 9285.87   85.46
#Mann= 14 ,-1 , 0
       0    .045       0  501.44     .08       0  689.15    .045       0
 2366.04     .09       0 2516.47    .045       0 4040.28     .04       0
 4040.28     .09       0 4115.91     .05       0  4248.9     .09       0
 4804.51     .08       0 6348.75    .045       0 8227.28    .045       0
 8227.28    .075       0 9285.87    .045       0
#XS Ineff= 2 , 0
         2280.86   66.65 6502.68           67.79
Permanent Ineff=
       F       F
Bank Sta=4115.91,4248.9
XS Rating Curve= 0 ,0
Exp/Cntr=0.5,0.3

Type RM Length L Ch R = 1 ,315613  ,501.33,113.47,142.82
BEGIN DESCRIPTION:
Surveyed Section
END DESCRIPTION:
XS GIS Cut Line= 6
2352325.41401578675108.7372244152352316.44985914673702.094617903
2352983.74737646671343.2754868872353349.73729999670293.546000004
2353548.88911927668073.2625262742353813.06414734666436.276424199
#Sta/Elev= 30
       0   70.97  607.75   59.24  634.37   59.41 1112.59   61.54 1169.37   62.64
 1972.31   63.14 2036.98   57.39 2248.56   60.71 2358.26   55.87 2846.24   60.69
 3378.89   53.33 4617.72   59.34 4811.49   53.494845.914    43.44911.287   42.78
4979.577   46.485000.167   53.65 5270.37   62.63 5537.62   56.77  5933.8   58.77
 5996.79   57.48 6859.41   54.55 6986.94   59.99  7281.5   58.22 7616.88   58.22
 8040.97   61.81 8306.55   57.36 8477.49    60.9 8542.26   62.81 8872.31    75.5
#Mann= 19 ,-1 , 0
       0     .08       0  607.75     .04       0  634.37    .045       0
 1112.59    .035       0 1169.37    .045       0 1972.31     .09       0
 2358.26    .045       0 2846.24     .06       0 4617.72     .08       0
 4811.49     .05       05000.167     .08       0  5933.8    .035       0
 5996.79     .08       0 6986.94    .045       0  7281.5     .08       0
 7616.88    .065       0 8040.97    .045       0 8477.49    .035       0
 8542.26    .045       0
#XS Ineff= 3 ,-1
       0    3000     101    3000    4739   64.99    5075    8873      63
Permanent Ineff=
       F       F       F
Bank Sta=4811.49,5000.167
XS Rating Curve= 0 ,0
Exp/Cntr=0.5,0.3

Type RM Length L Ch R = 3 ,315560  ,,,
BEGIN DESCRIPTION:
SR 58
END DESCRIPTION:
Bridge Culvert--1,0,-1,-1, 0
Deck Dist Width WeirC Skew NumUp NumDn MinLoCord MaxHiCord MaxSubmerge Is_Ogee
53.7,30,2.6,0, 161, 161, , , 0.98, 0, 1,1,,
       0   14.38   31.05   49.19   69.63   99.64  115.67  129.12  155.24  171.84
  191.39   210.8  224.18  257.86  275.21  293.68  312.31  329.22  350.71  371.84
  385.58   411.2  425.58  441.35  466.93  481.36  505.16  521.91  541.78  558.49
   573.7  588.85  605.75  619.23  639.87  664.83  679.78  693.72  716.09  732.67
  762.19  783.27  801.13  818.29  831.61  845.21  866.37  886.79   900.1  939.39
  955.39  981.22 1000.39 1014.17 1039.05 1059.72 1077.23 1095.88 1109.83 1123.23
 1138.46 1157.55 1183.47 1197.42 1217.29 1248.35    1262 1275.16 1302.09 1319.49
  1333.3 1357.46 1370.62 1392.15 1409.76 1432.31 1465.85 1481.39 1500.55 1515.52
 1539.97 1559.63 1574.27 1590.67 1610.59 1627.48 1647.67 1662.96 1678.73 1693.27
 1710.33 1736.92 1752.78 1766.17 1785.05 1801.11 1814.98 1829.55  1852.2  1865.3
 1884.76 1898.68 1914.43 1933.29 1957.96 1974.98 1990.81 2003.99 2027.35 2042.74
 4502.084561.1244619.2154679.9784738.2894789.0314789.0314830.622 4872.39 4915.37
4958.2065000.756    50255042.8955084.0345084.0345145.2965203.5335261.4945319.664
5379.111 6197.67 7603.19 8374.79 8388.47 8408.61 8426.15 8442.94 8463.47 8477.04
 8497.93 8511.46 8527.26 8549.48 8564.24 8578.55  8601.3 8622.04 8638.56 8656.67
 8679.34 8704.42 8718.64 8739.19 8754.81 8786.77 8805.82 8822.04 8838.03 8857.54
 8865.75
   69.37   68.94   68.96   68.68   68.45   68.04    67.8   67.75   67.45   67.03
   66.79   66.78   66.35    65.9   65.71   65.62    65.1   64.88   64.77   64.45
   64.07   64.02   63.83   63.51    63.6   63.25    63.1   62.98   62.78   62.74
   62.44   62.64   62.44   62.38   62.29   62.26   62.12   62.11   62.28   62.47
   62.14   62.09   61.89   62.15    62.2   62.41   62.32   62.01   62.12   62.27
   62.16   62.34    62.2    62.3   62.34   62.18   62.47   62.63   62.62   62.53
   62.66    62.6    62.6    62.4   62.57    62.6   62.48   62.77   62.72   62.63
   62.88   62.76   62.79   62.73   62.79   62.85   62.73   62.86      63   62.78
   62.75   62.85   62.87   62.77   62.82   62.88   62.84   62.91   62.81   62.82
   63.07   62.83   62.69   62.97   62.84   62.83   62.71   62.93    62.7   62.85
   62.78   62.49   62.44   62.62   62.46   62.38   62.52   62.51   62.51   62.36
    64.8   64.99   65.23   65.53   65.66   65.73   65.73   65.78   65.76   65.74
   65.78   65.86   65.86   65.78   65.73   65.73   65.76   65.83    65.8   65.62
   65.35   59.85   59.28   61.81   61.64   61.41   61.34   61.58   61.69   61.79
   61.97    62.3   62.45    62.6   63.03   63.35   63.93   64.62   65.11   65.61
   66.39   66.91   67.46   68.02   68.77   69.53   70.04   70.66   71.18    71.9
   72.36
                                                                                
                                                                                
                                                                                
                                                                                
                                                                                
                                                                                
                                                                                
                                                                                
                                                                                
                                                                                
                                                                                
                                                   62.73   62.78   62.76   62.74
   62.78   62.86   62.68
                                                                                
                                                                                
                                                                                
        
       0   14.38   31.05   49.19   69.63   99.64  115.67  129.12  155.24  171.84
  191.39   210.8  224.18  257.86  275.21  293.68  312.31  329.22  350.71  371.84
  385.58   411.2  425.58  441.35  466.93  481.36  505.16  521.91  541.78  558.49
   573.7  588.85  605.75  619.23  639.87  664.83  679.78  693.72  716.09  732.67
  762.19  783.27  801.13  818.29  831.61  845.21  866.37  886.79   900.1  939.39
  955.39  981.22 1000.39 1014.17 1039.05 1059.72 1077.23 1095.88 1109.83 1123.23
 1138.46 1157.55 1183.47 1197.42 1217.29 1248.35    1262 1275.16 1302.09 1319.49
  1333.3 1357.46 1370.62 1392.15 1409.76 1432.31 1465.85 1481.39 1500.55 1515.52
 1539.97 1559.63 1574.27 1590.67 1610.59 1627.48 1647.67 1662.96 1678.73 1693.27
 1710.33 1736.92 1752.78 1766.17 1785.05 1801.11 1814.98 1829.55  1852.2  1865.3
 1884.76 1898.68 1914.43 1933.29 1957.96 1974.98 1990.81 2003.99 2027.35 2042.74
 4502.084561.1244619.2154679.9784738.2894789.0314789.0314830.622 4872.39 4915.37
4958.2065000.756    50255042.8955084.0345084.0345145.2965203.5335261.4945319.664
5379.111 6197.67 7603.19 8374.79 8388.47 8408.61 8426.15 8442.94 8463.47 8477.04
 8497.93 8511.46 8527.26 8549.48 8564.24 8578.55  8601.3 8622.04 8638.56 8656.67
 8679.34 8704.42 8718.64 8739.19 8754.81 8786.77 8805.82 8822.04 8838.03 8857.54
 8865.75
   69.37   68.94   68.96   68.68   68.45   68.04    67.8   67.75   67.45   67.03
   66.79   66.78   66.35    65.9   65.71   65.62    65.1   64.88   64.77   64.45
   64.07   64.02   63.83   63.51    63.6   63.25    63.1   62.98   62.78   62.74
   62.44   62.64   62.44   62.38   62.29   62.26   62.12   62.11   62.28   62.47
   62.14   62.09   61.89   62.15    62.2   62.41   62.32   62.01   62.12   62.27
   62.16   62.34    62.2    62.3   62.34   62.18   62.47   62.63   62.62   62.53
   62.66    62.6    62.6    62.4   62.57    62.6   62.48   62.77   62.72   62.63
   62.88   62.76   62.79   62.73   62.79   62.85   62.73   62.86      63   62.78
   62.75   62.85   62.87   62.77   62.82   62.88   62.84   62.91   62.81   62.82
   63.07   62.83   62.69   62.97   62.84   62.83   62.71   62.93    62.7   62.85
   62.78   62.49   62.44   62.62   62.46   62.38   62.52   62.51   62.51   62.36
    64.8   64.99   65.23   65.53   65.66   65.73   65.73   65.78   65.76   65.74
   65.78   65.86   65.86   65.78   65.73   65.73   65.76   65.83    65.8   65.62
   65.35   59.85   59.28   61.81   61.64   61.41   61.34   61.58   61.69   61.79
   61.97    62.3   62.45    62.6   63.03   63.35   63.93   64.62   65.11   65.61
   66.39   66.91   67.46   68.02   68.77   69.53   70.04   70.66   71.18    71.9
   72.36
                                                                                
                                                                                
                                                                                
                                                                                
                                                                                
                                                                                
                                                                                
                                                                                
                                                                                
                                                                                
                                                                                
                                                   62.73   62.78   62.76   62.74
   62.78   62.86   62.68
                                                                                
                                                                                
                                                                                
        
Pier Skew, UpSta & Num, DnSta & Num=  ,4830.622, 2 ,4830.622, 2 , 0 , 0 , 0 ,,
     1.5     1.5
      40   62.86
     1.5     1.5
      40   62.86
Pier Skew, UpSta & Num, DnSta & Num=  ,4872.39, 2 ,4872.39, 2 , 0 , 0 , 0 ,,
     1.5     1.5
      40   62.86
     1.5     1.5
      40   62.86
Pier Skew, UpSta & Num, DnSta & Num=  ,4915.37, 2 ,4915.37, 2 , 0 , 0 , 0 ,,
     1.5     1.5
      40   62.86
     1.5     1.5
      40   62.86
Pier Skew, UpSta & Num, DnSta & Num=  ,4958.206, 2 ,4958.206, 2 , 0 , 0 , 0 ,,
     1.5     1.5
      40   62.86
     1.5     1.5
      40   62.86
Pier Skew, UpSta & Num, DnSta & Num=  ,5000.756, 2 ,5000.756, 2 , 0 , 0 , 0 ,,
     1.5     1.5
      40   62.86
     1.5     1.5
      40   62.86
BR Coef=-1 , 0 , 0 ,, 0 ,,,0.8,0,,0,
WSPro=,,,, 1 ,,,, 0 ,,,, 0 ,,,,-1 ,-1 ,-1 , 0 , 0 , 0 , 0 , 0
BC Design=,, 0 ,, 0 ,,,,,,
BC Use User HTab Curves=0
BC User HTab FreeFlow(D)= 0

Type RM Length L Ch R = 1 ,315500  ,2094.9,1191,749.54
BEGIN DESCRIPTION:
Surveyed Section
END DESCRIPTION:
XS GIS Cut Line= 6
2352462.87049893675114.4645778982352487.49440034673621.036991328
2353298.63406093671048.0265330372353551.40255912669413.589421868
2353668.46899094668062.0042546842353987.74107766666460.322619572
#Sta/Elev= 30
       0   71.01  400.08   70.63  717.46   62.22   974.9   60.57 1994.92   62.44
 2416.03   57.79 2686.73    60.2 3298.04   55.02 4092.47   55.43 4611.77   60.29
 4659.54   62.774754.071    52.84815.762    50.64832.491   56.244873.442   46.67
4896.721   43.445013.203   46.255046.373   55.55 5236.49    59.1 5855.89   52.36
 6040.51   56.16 6178.51   58.28  6464.8   54.11 6761.51    57.6 7448.01   56.68
 7661.22    57.3 7773.57   58.84  8094.7   59.97 8380.45   57.48 8846.67   75.16
#Mann= 20 ,-1 , 0
       0    .045       0  717.46     .08       0   974.9    .045       0
 1994.92     .09       0 2416.03    .045       0 2686.73     .05       0
 3298.04     .08       0 4092.47    .045       0 4611.77    .075       0
 4659.54     .08       04873.442     .05       05013.203     .09       0
 6040.51    .035       0 6178.51     .09       0 6761.51    .055       0
 7448.01    .045       0 7661.22    .045       0 7773.57    .055       0
  8094.7    .045       0 8380.45    .045       0
#XS Ineff= 3 ,-1
       0    3000      72    3000 4739.61   62.73    5075    8850      63
Permanent Ineff=
       F       F       F
Bank Sta=4873.442,5013.203
XS Rating Curve= 0 ,0
Exp/Cntr=0.5,0.3

Type RM Length L Ch R = 1 ,314309  ,824.74,643,439.11
BEGIN DESCRIPTION:
Tie In to Greene County Model
END DESCRIPTION:
XS GIS Cut Line= 3
2354313.52570134674576.4546854942354313.52570134667644.889063418
2354414.73929533666339.720631957
#Sta/Elev= 30
       0   84.72  325.44   80.22  749.22   68.58  969.57   72.62 1130.61   67.81
 1179.44   61.63 1292.38   56.72 2325.75   58.21 3453.97   51.85 3628.72    54.9
 3749.74   51.07 4147.69   55.31 4946.04   52.99 4984.81   41.22 5008.71   41.29
 5035.67   52.73 5159.19   59.41 5259.55   59.11 5291.98   55.99 5365.77   59.46
 5436.45    53.2 5587.61   52.18 6366.06   52.34 6411.97   58.29 6464.76   59.86
 7187.86   55.84 7359.16   59.11 7601.78    55.7 7948.35    61.5 8240.65   74.35
#Mann= 3 , 0 , 0
       0     .09       0 4946.04     .05       0 5035.67     .09       0
#XS Ineff= 2 , 0
       0 2305.61   60.74 5162.75       0    60.9
Permanent Ineff=
       F       F
Bank Sta=4946.04,5035.67
XS Rating Curve= 0 ,0
Exp/Cntr=0.3,0.1
Stream Node=Contentnea Crk  ,Downstream      , 0 , 0 ,Upstream end
Stream Node=Contentnea Crk  ,Downstream      , 0 , 1 ,Downstream end

Chan Stop Cuts=-1
Use User Specified Reach Order=0