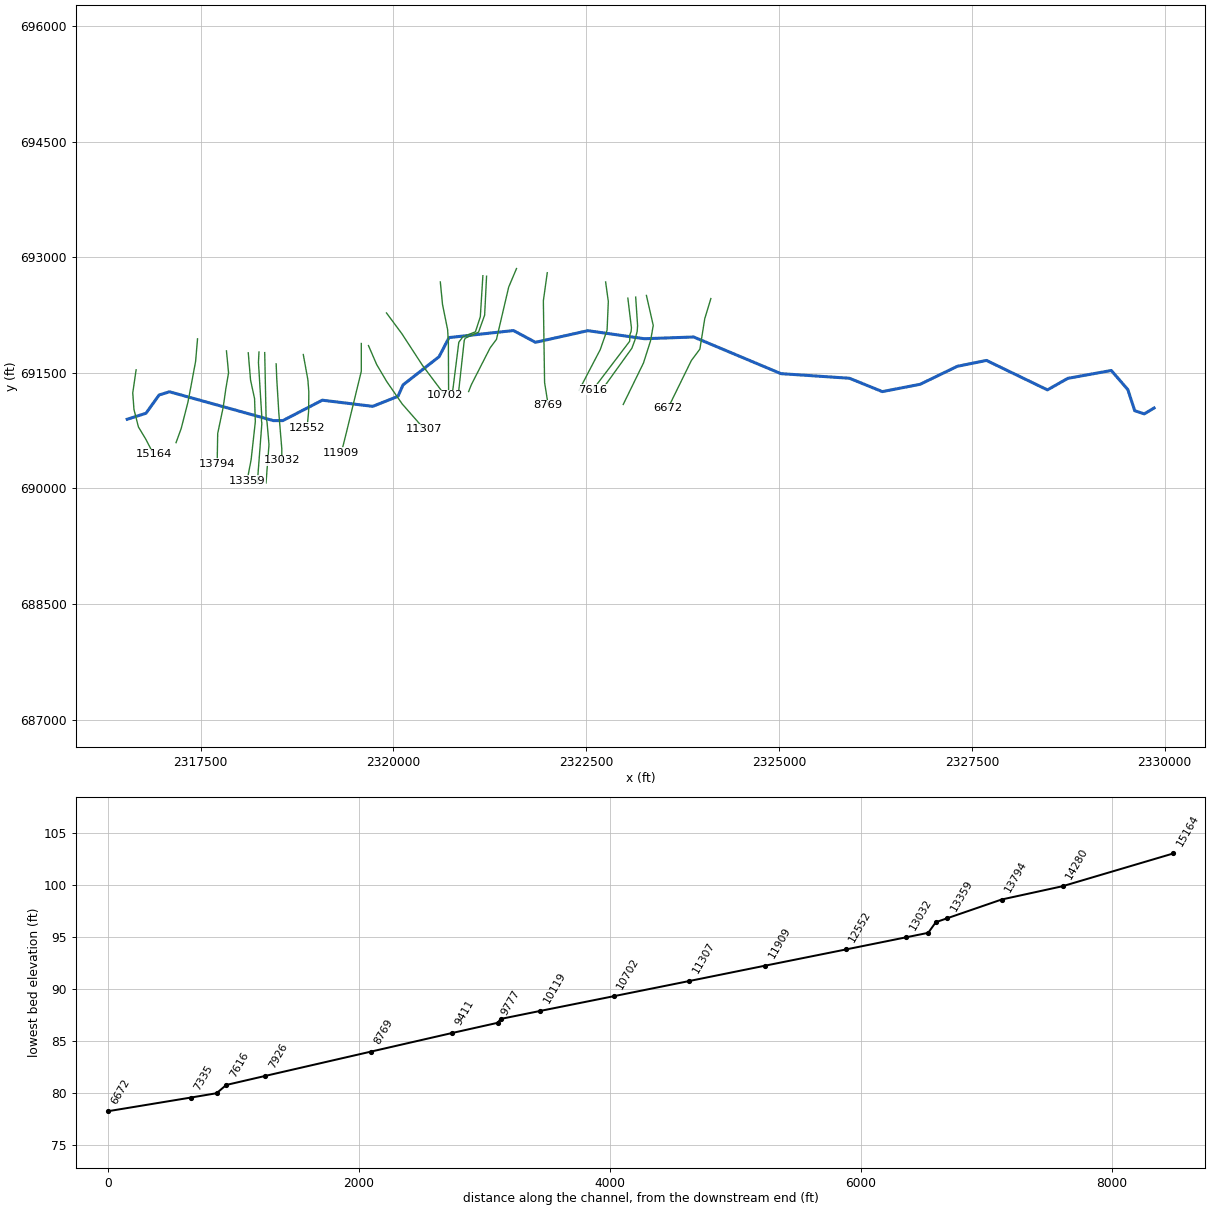
--- dtl_contentnea_crk_trib.prj (project) ---

Proj Title=dtl_contentnea_crk_trib
Current Plan=p01
Default Exp/Contr=0.3,0.1
English Units
Geom File=g01
Flow File=f01
Flow File=f02
Plan File=p01
Plan File=p03
Y Axis Title=Elevation
X Axis Title(PF)=Main Channel Distance
X Axis Title(XS)=Station
BEGIN DESCRIPTION:
END DESCRIPTION:
DSS Export Rating Curves= 0
DSS Export Rating Curve Sorted= 0
DSS Export Volume Flow Curves= 0
DXF OffsetX= 0
DXF OffsetY= 0
DXF ScaleX= 1
DXF ScaleY= 10

--- dtl_contentnea_crk_trib.p01 (plan) ---

Plan Title=dtl_contentnea_crk_trib
Program Version=4.00
Short Identifier=Plan 01
Geom File=g01
Flow File=f01
Subcritical Flow
K Sum by GR= 0
Std Step Tol= 0.01
Critical Tol= 0.01
Num of Std Step Trials= 20
Max Error Tol= 0.3
Flow Tol Ratio= 0.001
Split Flow NTrial= 30
Split Flow Tol= 0.02
Split Flow Ratio= 0.02
Log Output Level= 0
Friction Slope Method= 1
Unsteady Friction Slope Method= 2
Unsteady Bridges Friction Slope Method= 1
Parabolic Critical Depth
Global Vel Dist= 0 , 0 , 0
Global Log Level= 0
CheckData=True
Encroach Param=-1 ,10,10, 2
Encroach River=Contentnea Creek
Encroach Reach=Tributary
Encroach Node=15164
       1     602     654
Encroach Node=14280
       4       1
Encroach Node=13794
       4       1
Encroach Node=13359
       4       1
Encroach Node=13270
       1     835     870
Encroach Node=13210
       1  838.79  865.92
Encroach Node=13032
       1     690     770
Encroach Node=12552
       1     640     685
Encroach Node=11909
       4       1
Encroach Node=11307
       1     745     830
Encroach Node=10702
       4       1
Encroach Node=10119
       1     701     783
Encroach Node=9803
       4       1
Encroach Node=9777
       1     730     900
Encroach Node=9411
       1     800   868.5
Encroach Node=8769
       1     866    1025
Encroach Node=7926
       1     620     825
Encroach Node=7616
       1     456  505.76
Encroach Node=7538
       1     493   520.5
Encroach Node=7335
       1     530     630
Encroach Node=6672
       1   502.5   606.5
Encroach Node=5988
       1   733.5     845
Encroach Node=5258
       1 1001.71    1145
Encroach Node=4057
       4       1
Encroach Node=2893
       4       1
Computation Interval=1HOUR
Output Interval=1HOUR
Run HTab= 0
Run UNet= 0
Run PostProcess= 0
Run WQNet= 0
UNET Theta= 1
UNET Theta Warmup= 1
UNET ZTol= 0.02
UNET ZSATol= 0.05
UNET MxIter= 20
UNET MaxInSteps= 0
UNET DtIC= 0
UNET DtMin= 0
UNET MaxCRTS= 20
UNET WFStab= 2
UNET SFStab= 1
UNET WFX= 1
UNET SFX= 1
UNET DSS MLevel= 4
UNET DZMax Abort= 100
UNET Convert EG Bridges= 0
UNET Use Existing IB Tables=-1
UNET Froude Reduction=False
UNET Froude Limit= 1
UNET Froude Power= 10
UNET Time Slicing=0,0, 5
Instantaneous Interval=1HOUR
Write IC File= 0
Echo Input=False
Echo Output=False
Write Detailed= 0
Detailed Automatic Start=False, 10
WQ ULTIMATE=-1
WQ Max Comp Step=1HOUR
WQ Output Interval=15MIN
WQ Output Selected Increments= 0
WQ Output face flow=0
WQ Output face velocity=0
WQ Output face area=0
WQ Output face dispersion=0
WQ Output cell volume=0
WQ Output cell surface area=0
WQ Output cell continuity=0
WQ Output face conc=0
WQ Output face dconc_dx=0
WQ Output face courant=0
WQ Output face peclet=0
WQ Output face adv mass=0
WQ Output face disp mass=0
WQ Output cell mass=0
WQ Output cell source sink temp=0
WQ Output cell source sink nsm=0
WQ Output MaxMinRange=-1
WQ Daily Max Min Mean=-1
WQ Daily Range=0
WQ Daily Time=0
WQ Create Restart=0
WQ Fixed Restart=0
WQ System Summary=False
Sorting and Armoring Iterations= 10
XS Update Threshold= 0.02
Hydraulics Update Threshold= 0.02
Energy Slope Method= 1
Volume Change Method= 0
XS Weighting Method= 0
Number of US Weighted Cross Sections= 1
Number of DS Weighted Cross Sections= 1
Upstream XS Weight=0.25
Main XS Weight=0.5
Downstream XS Weight=0.25
Number of DS XS's Weighted with US Boundary= 1
Upstream Boundary Weight= 1
Weight of XSs Associated with US Boundary= 0
Number of US XS's Weighted with DS Boundary= 1
Downstream Boundary Weight= 0.5
Weight of XSs Associated with DS Boundary= 0.5
Sediment Output Level= 4
Mass or Volume Output= 0
Output Increment Type= 1
Profile and TS Output Increment= 10
XS Output Flag= 0
XS Output Increment= 10
Disregard all LS=0
Disregard all Conn=0
Disregard all Breaches=0
Disregard all Pumps=0

--- dtl_contentnea_crk_trib.p03 (plan) ---

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Plan Title=dtl_contentnea_crk_trib_future
Geom File=g01
Flow File=f02
Encroach Param=-1 ,,, 2

--- dtl_contentnea_crk_trib.f01 (steady flow) ---

Flow Title=dtl_contentnea_crk_trib
Program Version=4.00
Number of Profiles= 6
Profile Names=100-yr,FW,10-yr,25-yr,50-yr,500-yr
River Rch & RM=Contentnea Creek,Tributary       ,15164
     710     710     290     430     560    1140
River Rch & RM=Contentnea Creek,Tributary       ,7335
     890     890     380     550     710    1430
Boundary for River Rch & Prof#=Contentnea Creek,Tributary       , 1
Up Type= 0
Dn Type= 3
Dn Slope=0.002
DSS Import GetInterval= 0
DSS Import GetPeak= 0
DSS Import FillOption= 0

--- dtl_contentnea_crk_trib.f02 (steady flow) ---

Flow Title=dtl_contentnea_crk_trib_future
Program Version=4.00
Number of Profiles= 3
Profile Names=100-yr-10%,100-yr-20%,100-yr-35%
River Rch & RM=Contentnea Creek,Tributary       ,15164
    1230    1580    1930
River Rch & RM=Contentnea Creek,Tributary       ,7335
    1550    1980    2420
Boundary for River Rch & Prof#=Contentnea Creek,Tributary       , 1
Up Type= 0
Dn Type= 3
Dn Slope=0.002
Boundary for River Rch & Prof#=Contentnea Creek,Tributary       , 2
Up Type= 0
Dn Type= 3
Dn Slope=0.002
Boundary for River Rch & Prof#=Contentnea Creek,Tributary       , 3
Up Type= 0
Dn Type= 3
Dn Slope=0.002
DSS Import GetInterval= 0
DSS Import GetPeak= 0
DSS Import FillOption= 0

--- dtl_contentnea_crk_trib.g01 (geometry) ---

Geom Title=dtl_contentnea_crk_trib
Program Version=4.00

River Reach=Contentnea Creek,Tributary
Reach XY= 30
2316549.39177717690896.7182814482316792.06733732690974.251805663
 2316962.6769572691212.0398809462317097.65480825691253.068390742
2318443.15642779690879.0266332332318566.06358801690879.026633233
2319077.97787663691143.9333280322319731.89169994691063.984010234
2320058.84861155691194.050810844 2320124.4786486691342.016712472
2320592.24182142691708.3516462892320721.11534858691956.366064563
2321556.40672861692047.7260592432321841.67365091691894.837904856
2322520.34789717692045.8615695392323254.95683415691941.450147048
2323892.61230728691963.8240232772325024.35754766691488.379152939
2325911.85463901691428.7154829352326338.82277748691255.317941993
2326829.18356527691350.4069160522327310.22190468691583.468126997
2327688.71331131691659.9122042062328479.25693892691277.691818222
2328742.14998487691426.8509932462329307.09036024691529.397926062
2329521.50667429691281.4207976012329611.00217929691007.340813532
2329734.05849867690966.3220404092329861.75487393691042.754634306

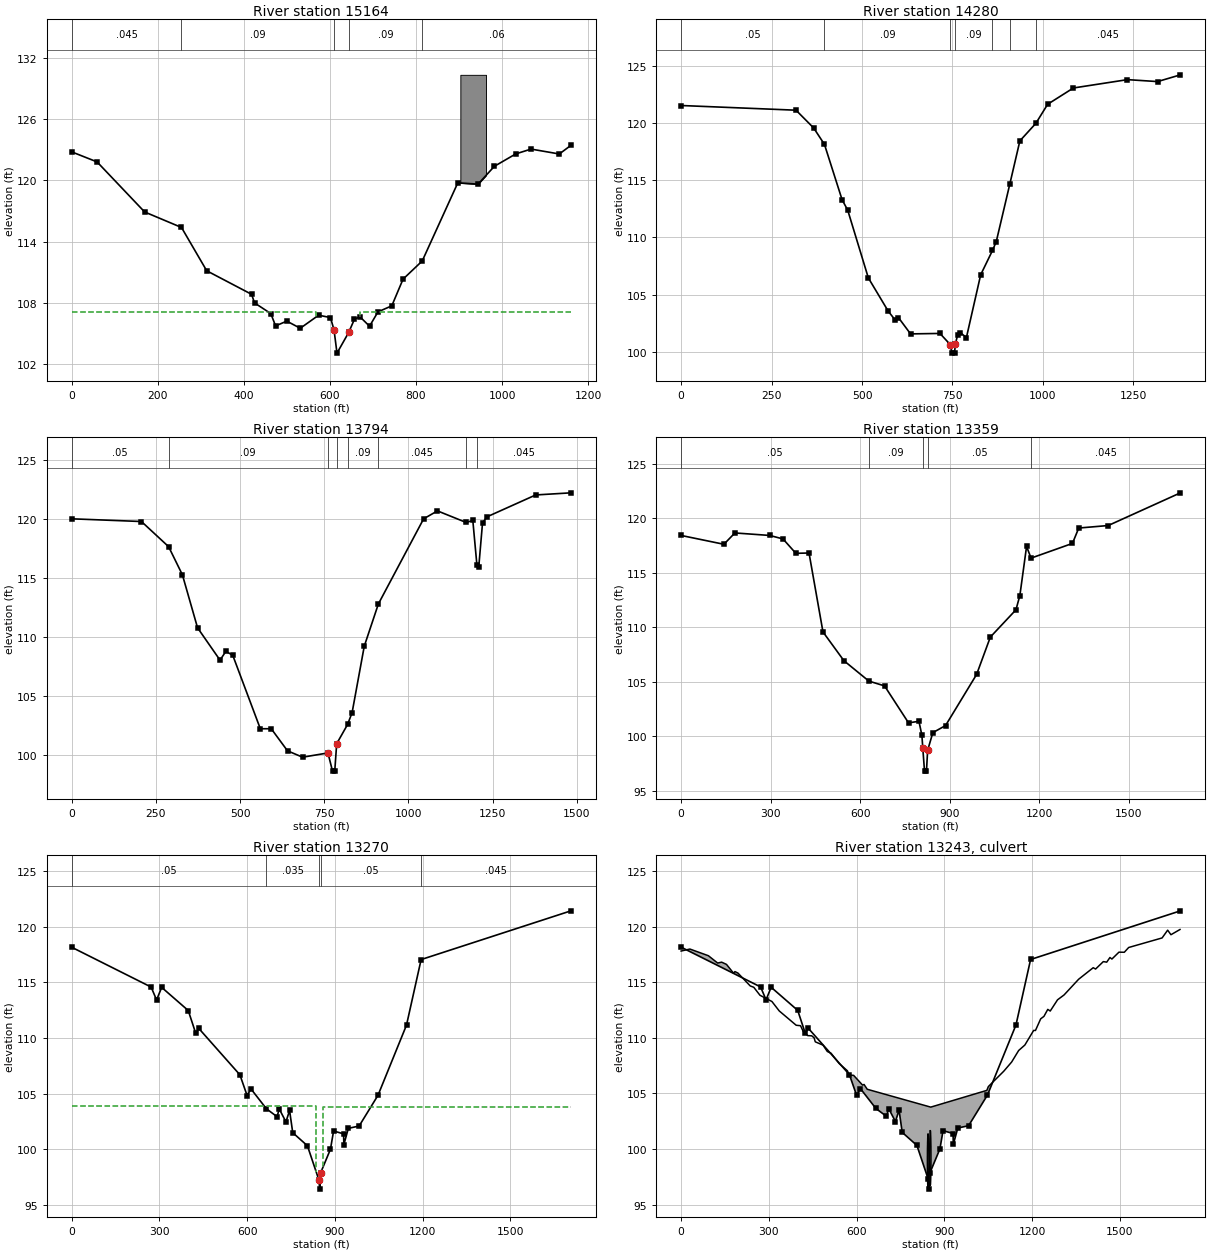
Type RM Length L Ch R = 1 ,15164   ,953.97,884.21,755.06
XS GIS Cut Line= 6
2316664.13423428691538.1913138932316620.57823606691237.258962527
2316636.41678086691023.4386075882316693.83150576 690797.73934406
2316788.86277461690639.3538959772316891.81331587690441.372085884
#Sta/Elev= 30
       0   122.8   59.15  121.81  169.58   116.9  255.17  115.38  313.79  111.13
  418.02  108.82  424.78  107.98  462.63  106.93  473.72  105.72  499.77  106.19
  531.03  105.49   573.7  106.77  601.21  106.54   609.5  105.32  616.37  103.05
  643.57  105.08  656.91  106.38   669.6  106.62  691.97  105.69  711.57   107.1
  743.65  107.69  769.82  110.31  814.33  112.09     897  119.76  943.97  119.63
  981.89  121.38 1031.74   122.6 1067.12  123.07 1132.75  122.59 1159.85  123.44
#Mann= 5 ,-1 , 0
       0    .045       0  255.17     .09       0   609.5    .045       0
  643.57     .09       0  814.33     .06       0
#XS Ineff= 2 , 0
       0     568   107.1     670       0   107.1
Permanent Ineff=
       F       F
#Block Obstruct= 1 ,-1
   902.9  962.49 130.356
Bank Sta=609.5,643.57
XS Rating Curve= 0 ,0
Exp/Cntr=0.3,0.1

Type RM Length L Ch R = 1 ,14280   ,465.92,485.6,471.02
XS GIS Cut Line= 6
   2317460.50189  691940.0886094 2317435.5546408  691649.0373676
 2317385.6601422  691378.7755003 2317335.7656436  691116.8293827
  2317248.450271  690775.8836423  2317181.924273  690592.9371475
#Sta/Elev= 30
       0  121.52  317.64  121.11  366.61  119.55  396.26  118.12  444.98  113.29
  460.51  112.38  517.51  106.46  572.39  103.56  591.69  102.78  600.78  102.99
  634.22  101.57  715.49  101.61  743.77  100.64   748.4   99.89  755.79   99.89
  757.86  100.67  764.42  101.48  771.81  101.68  788.59  101.25     828  106.73
   860.7  108.86  871.11  109.63  908.87   114.7  936.36  118.43  980.51  119.96
  1013.2  121.63 1084.29  123.05 1233.82  123.78 1317.05  123.61 1380.22   124.2
#Mann= 7 ,-1 , 0
       0     .05       0  396.26     .09       0  743.77    .045       0
  757.86     .09       0   860.7     .07       0  908.87     .09       0
  980.51    .045       0
Bank Sta=743.77,757.86
XS Rating Curve= 0 ,0
Exp/Cntr=0.3,0.1

Type RM Length L Ch R = 1 ,13794   ,420.83,435.08,444.69
XS GIS Cut Line= 6
 2317835.4640161  691784.2123085 2317862.7069622  691499.3996898
 2317828.0341217  691296.3159095 2317793.3612811  691053.6060257
 2317721.9521488   690711.866617 2317714.8737444  690315.4759687
#Sta/Elev= 30
       0  119.98   207.3  119.75  287.98  117.62  329.02  115.23  373.92  110.75
  440.66  108.01  457.95  108.75  478.36  108.43  560.33   102.2   592.8   102.2
  641.07  100.33  685.84   99.79  761.16  100.15  774.74   98.61  781.36   98.61
  787.11  100.93  819.44  102.56  832.93  103.57  869.02  109.19  910.94  112.77
 1045.34  119.98 1086.43  120.65 1171.63  119.67 1191.38  119.84 1203.66  116.03
 1209.04  115.91 1220.25  119.64 1233.69  120.15  1378.1     122 1482.88  122.18
#Mann= 8 ,-1 , 0
       0     .05       0  287.98     .09       0  761.16    .045       0
  787.11     .05       0  819.44     .09       0  910.94    .045       0
 1171.63     .09       0 1203.66    .045       0
Bank Sta=761.16,787.11
XS Rating Curve= 0 ,0
Exp/Cntr=0.3,0.1

Type RM Length L Ch R = 1 ,13359   ,86.75,88.96,84.98
XS GIS Cut Line= 6
 2318118.2000984   691758.734913  2318147.919676  691404.5766132
 2318199.9289368  691164.3433609 2318209.8354627  690864.6709534
 2318155.3495704  690371.8212914 2318103.3403096  690101.8684615
#Sta/Elev= 30
       0  118.42  143.36  117.61  180.27  118.65  296.96  118.42  341.52   118.1
  384.55  116.78  428.73  116.81  475.43  109.57  545.63  106.93  629.24  105.06
  681.76  104.62  762.16  101.23   797.1  101.37  806.96  100.09  810.08   98.88
  815.76    96.8   822.3    96.8  826.23    98.7   843.6  100.33  886.24  100.98
  990.33  105.67 1036.41   109.1 1122.19   111.6 1135.32  112.91 1157.77  117.41
 1172.79  116.34 1311.55  117.69  1332.6   119.1 1431.46  119.33  1673.5  122.33
#Mann= 5 ,-1 , 0
       0     .05       0  629.24     .09       0  810.08    .045       0
  826.23     .05       0 1172.79    .045       0
Bank Sta=810.08,826.23
XS Rating Curve= 0 ,0
Exp/Cntr=0.5,0.3

Type RM Length L Ch R = 1 ,13270   ,63.54,60.58,70.26
BEGIN DESCRIPTION:
Surveyed Section
END DESCRIPTION:
XS GIS Cut Line= 6
 2318256.8993948  691769.4975301 2318250.2848274  691632.7964719
    2318293.9444     690926.4417    2318289.0781      690887.257
    2318294.4129     690842.6939 2318235.3284069  690067.6972385
#Sta/Elev= 30
       0  118.17  271.67  114.59  290.37  113.43   307.8  114.56  398.59  112.48
  424.37  110.42  434.71  110.87  575.23   106.7  599.91  104.83  612.88  105.44
  665.86  103.65  702.07  102.94  709.81  103.63  732.58  102.47  744.98   103.5
 755.809   101.5 805.991 100.325 844.737  97.289 848.151  96.428 851.053  97.887
 884.679 100.011 895.432 101.654  929.57 101.397  930.57  100.43  945.82  101.89
  982.73   102.1 1047.22  104.86 1144.68  111.17 1194.65  117.06 1706.89  121.44
#Mann= 5 ,-1 , 0
       0     .05       0  665.86    .035       0 844.737    .045       0
 851.053     .05       0 1194.65    .045       0
#XS Ineff= 2 , 0
       0 836.615   103.9  859.38       0  103.81
Permanent Ineff=
       F       F
Bank Sta=844.737,851.053
XS Rating Curve= 0 ,0
Exp/Cntr=0.5,0.3

Type RM Length L Ch R = 2 ,13243   ,,,
BEGIN DESCRIPTION:
Yank Rd
END DESCRIPTION:
Bridge Culvert--1,0,-1,-1, 0
Deck Dist Width WeirC Skew NumUp NumDn MinLoCord MaxHiCord MaxSubmerge Is_Ogee
17.5,18,2.6,0, 60, 60, , , 0.95, 0, 1,1,,
       0   30.07   93.25   124.9  138.58  155.06  179.21     184  194.16  236.24
  248.33  269.62  310.38  335.41  393.41   408.2  416.95  432.74  446.46  454.59
  458.64  485.23  499.76  512.57  540.14  568.53  574.21  589.78  620.12  625.43
  636.22  853.37 1045.07 1050.19 1102.78 1129.84 1153.88 1175.03 1205.19 1211.29
 1229.16 1240.25  1253.4 1261.77 1286.71  1309.1 1358.79 1408.65 1416.79 1443.27
 1454.85 1465.88 1472.59 1496.68 1514.93 1529.92 1644.14 1663.17 1674.39 1705.37
  117.82     118   117.4  116.74  116.82  116.62  115.83  115.97  115.84  114.68
  114.56  113.84  113.28  112.43  111.14   111.1  110.61  110.21  110.19  110.01
  109.65  109.35  108.78  108.62   107.7  107.04  106.67  106.63  105.76  105.81
  105.38 103.773  105.28  105.62     107  107.83  108.87  109.36  110.68  110.67
  111.72  111.94  112.57  112.42  113.43  113.87  115.28  116.32   116.2  116.87
  116.82  117.24   117.1  117.72  117.71  118.14     119   119.7  119.29  119.76
                                                                                
                                                                                
                                                                                
                                                                                
                                                                                
                                                                                
       0   30.07   93.25   124.9  138.58  155.06  179.21     184  194.16  236.24
  248.33  269.62  310.38  335.41  393.41   408.2  416.95  432.74  446.46  454.59
  458.64  485.23  499.76  512.57  540.14  568.53  574.21  589.78  620.12  625.43
  636.22  853.37 1045.07 1050.19 1102.78 1129.84 1153.88 1175.03 1205.19 1211.29
 1229.16 1240.25  1253.4 1261.77 1286.71  1309.1 1358.79 1408.65 1416.79 1443.27
 1454.85 1465.88 1472.59 1496.68 1514.93 1529.92 1644.14 1663.17 1674.39 1705.37
  117.82     118   117.4  116.74  116.82  116.62  115.83  115.97  115.84  114.68
  114.56  113.84  113.28  112.43  111.14   111.1  110.61  110.21  110.19  110.01
  109.65  109.35  108.78  108.62   107.7  107.04  106.67  106.63  105.76  105.81
  105.38 103.773  105.28  105.62     107  107.83  108.87  109.36  110.68  110.67
  111.72  111.94  112.57  112.42  113.43  113.87  115.28  116.32   116.2  116.87
  116.82  117.24   117.1  117.72  117.71  118.14     119   119.7  119.29  119.76
                                                                                
                                                                                
                                                                                
                                                                                
                                                                                
                                                                                
BR Coef=-1 , 0 , 0 ,, 0 ,,,0.8,0,,0,
WSPro=,,,, 1 ,,,, 0 ,,,, 0 ,,,,-1 ,-1 ,-1 , 0 , 0 , 0 , 0 , 0
Culvert=1,5,,40,0.024,0.5,1,2,1,96.3914,844.125,96.5231,848.565,Culvert #2  , 0 ,7.5
Culvert Bottom n=0.024
Culvert=1,5,,40,0.021,0.5,1,2,1,96.7055,851.875,97.3449,856.315,Culvert #1  , 0 ,7
Culvert Bottom n=0.021
BC Design=,, 0 ,, 0 ,,,,,,
BC Use User HTab Curves=0
BC User HTab FreeFlow(D)= 0

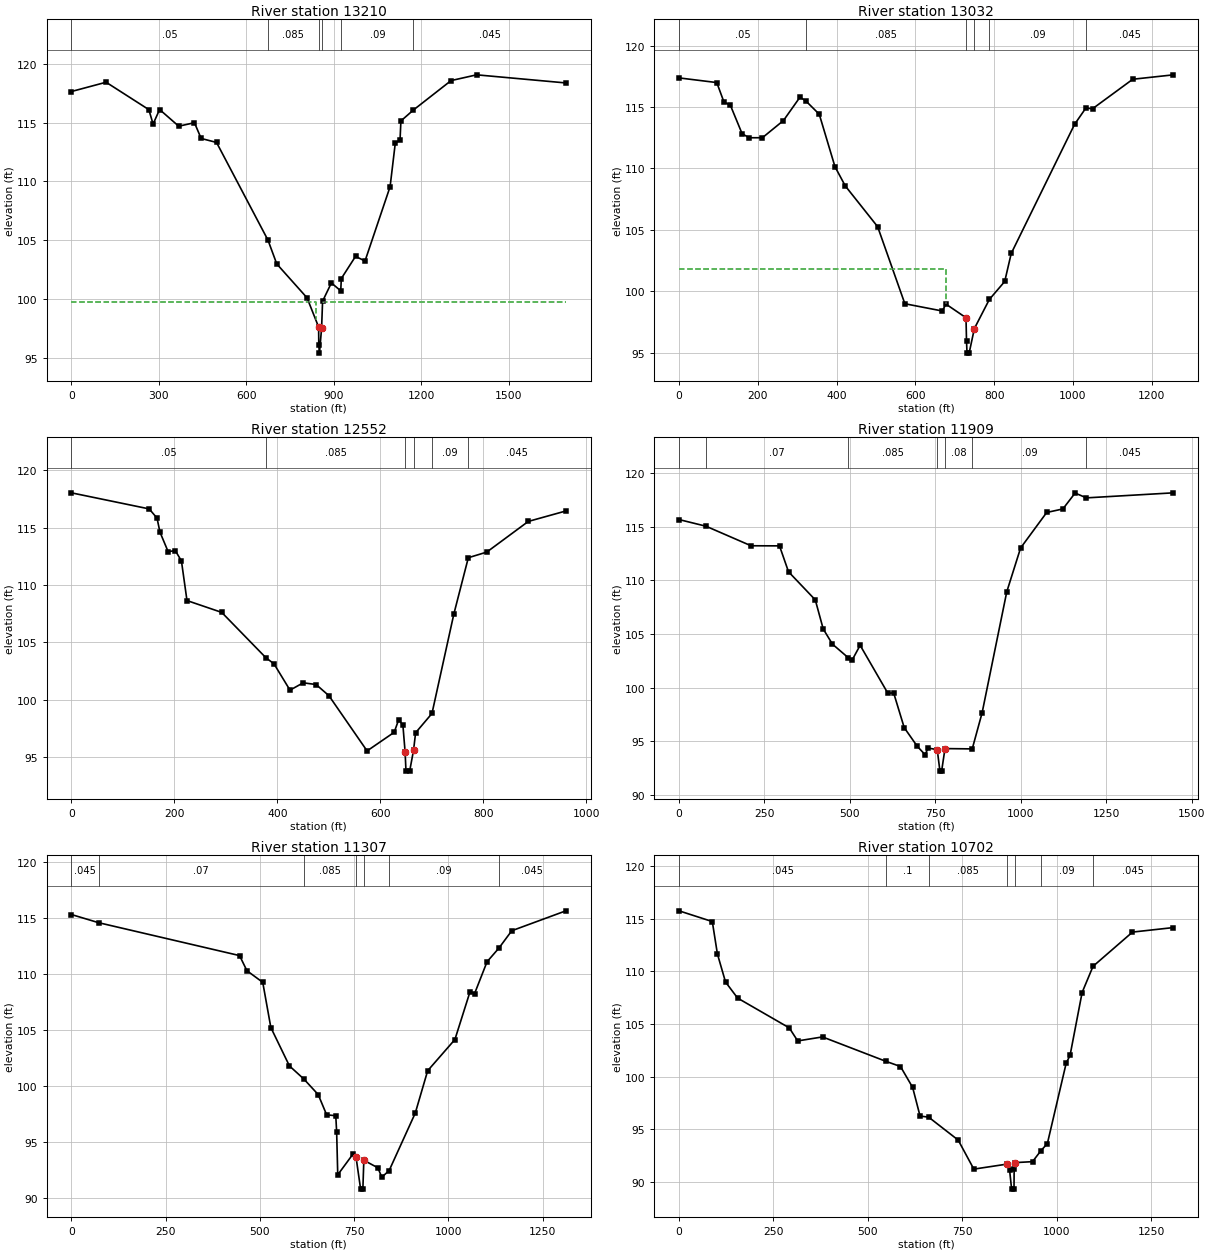
Type RM Length L Ch R = 1 ,13210   ,175.16,177.5,176.24
BEGIN DESCRIPTION:
Surveyed Section
END DESCRIPTION:
XS GIS Cut Line= 6
 2318331.3867071  691761.2468349     2318349.447     690903.2342
    2318359.4128     690871.1445    2318363.3093     690839.4328
 2318387.0096825  690569.0515494  2318348.380008  690069.4410927
#Sta/Elev= 30
       0  117.65  119.07  118.44  265.78  116.11  280.25  114.88  302.66  116.12
  368.35   114.7   422.2     115  445.15  113.66  497.97  113.32  674.55  105.01
  704.62  102.99 808.582 100.106 848.281  97.621  848.79  96.057 851.165  95.405
  858.45   97.54 861.854  99.822 892.053 101.376 924.118 100.701  926.15  101.75
  974.84  103.63 1007.44  103.24 1093.48  109.56 1111.38  113.29 1127.51   113.5
 1130.57  115.15 1173.51  116.08 1302.68  118.58 1390.44  119.07 1696.56  118.38
#Mann= 6 ,-1 , 0
       0     .05       0  674.55    .085       0 848.281    .045       0
  858.45     .08       0  926.15     .09       0 1173.51    .045       0
#XS Ineff= 2 , 0
       0  838.79   99.75  861.66       0   99.75
Permanent Ineff=
       F       F
Bank Sta=848.281,858.45
XS Rating Curve= 0 ,0
Exp/Cntr=0.5,0.3

Type RM Length L Ch R = 1 ,13032   ,428.44,479.91,437.87
XS GIS Cut Line= 5
 2318479.7882926   691615.090288  2318487.218187  691429.3429279
 2318514.4611332  690976.1193694 2318553.0603344  690512.2478493
 2318553.0603344  690362.2163109
#Sta/Elev= 30
       0  117.37   95.88  116.99  114.07  115.41  130.47  115.14  160.16  112.83
  177.98   112.5  211.67   112.5  265.19   113.9   307.1   115.8   321.9   115.5
   356.1  114.41  395.88  110.15   422.1  108.58   504.3  105.26  573.41   98.99
  668.31    98.4  677.77   98.96  728.66   97.85  729.91   95.98   731.2   94.97
   736.8      95  749.88   96.97  787.92   99.34   826.9   100.8  843.42  103.08
 1004.29  113.59 1032.98  114.92 1049.96  114.86 1152.03  117.26 1255.44  117.62
#Mann= 6 ,-1 , 0
       0     .05       0   321.9    .085       0  728.66    .045       0
  749.88     .08       0  787.92     .09       0 1032.98    .045       0
#XS Ineff= 2 , 0
       0  677.77   101.8               0
Permanent Ineff=
       F       F
Bank Sta=728.66,749.88
XS Rating Curve= 0 ,0
Exp/Cntr=0.3,0.1

Type RM Length L Ch R = 1 ,12552   ,620.41,643.48,568.56
XS GIS Cut Line= 5
 2318831.4699609  691736.4452298 2318890.9091162  691409.5298762
 2318903.2922735  691253.5020937  2318900.815642  691003.3623156
 2318881.0025903  690782.9421149
#Sta/Elev= 30
       0  118.03  151.06  116.63  166.31  115.83  171.91  114.62  187.83  112.91
  201.78     113  213.69   112.1  224.47  108.65  291.94  107.62  377.76  103.67
  393.46  103.14  424.52  100.85  450.17  101.49  475.18  101.34  500.06  100.37
   574.2   95.56  626.83   97.18  635.52   98.27  643.75   97.82  648.05   95.46
  649.77    93.8  656.89    93.8  664.46   95.62  668.43   97.14  700.22   98.82
  742.71  107.48   770.8  112.38  806.62  112.87  887.27  115.54  960.25  116.45
#Mann= 6 ,-1 , 0
       0     .05       0  377.76    .085       0  648.05    .045       0
  664.46     .08       0  700.22     .09       0   770.8    .045       0
Bank Sta=648.05,664.46
XS Rating Curve= 0 ,0
Exp/Cntr=0.3,0.1

Type RM Length L Ch R = 1 ,11909   ,479.32,601.66,678.15
XS GIS Cut Line= 4
  2319583.572515  691879.8033486  2319583.572515  691518.8047225
 2319395.9947975  690747.2586392 2319325.2107531  690464.1224618
#Sta/Elev= 30
       0  115.67      79  115.05  210.73  113.23  294.05  113.22  320.37  110.81
  398.72  108.19  421.95  105.48  448.87  104.07  495.26   102.8  507.05  102.61
  529.98  103.96  611.13   99.49     628   99.53  658.96   96.29  697.23   94.55
  720.01   93.77  728.94   94.39  755.56   94.24  763.46   92.24  768.41   92.24
  778.27   94.34  857.99   94.31  886.93   97.68  959.01  108.94  999.44  113.02
 1075.84  116.33 1123.26  116.66 1158.97  118.14 1192.08  117.69 1446.87  118.16
#Mann= 7 ,-1 , 0
       0    .045       0      79     .07       0  495.26    .085       0
  755.56    .045       0  778.27     .08       0  857.99     .09       0
 1192.08    .045       0
Bank Sta=755.56,778.27
XS Rating Curve= 0 ,0
Exp/Cntr=0.3,0.1

Type RM Length L Ch R = 1 ,11307   ,531.54,605.11,526.08
XS GIS Cut Line= 5
 2319676.6298551   691852.529592  2319783.318949  691605.8110623
 2319913.3462823   691385.764806 2320113.3883334  691095.7038318
 2320400.1152735  690768.9684816
#Sta/Elev= 30
       0  115.31   72.13  114.58     446  111.64  465.52  110.29   507.5  109.25
     529  105.21  578.29  101.78  616.51  100.61  654.53   99.22  676.99   97.41
  701.18   97.33  703.48    95.9  706.43   92.05  746.53   93.89  754.74   93.67
  767.11   90.77  773.04   90.77  775.59   93.35  812.62   92.68  823.34   91.84
  842.74   92.43  912.06   97.57  944.89  101.35 1017.15  104.14 1057.32  108.42
 1069.41  108.25 1102.41  111.09 1133.88  112.31 1167.94  113.86 1311.45  115.64
#Mann= 7 ,-1 , 0
       0    .045       0   72.13     .07       0  616.51    .085       0
  754.74     .05       0  775.59     .08       0  842.74     .09       0
 1133.88    .045       0
Bank Sta=754.74,775.59
XS Rating Curve= 0 ,0
Exp/Cntr=0.3,0.1

Type RM Length L Ch R = 1 ,10702   ,519.98,582.78,400.99
XS GIS Cut Line= 4
 2319910.0122481  692275.9519336 2320110.0542993  692005.8951646
 2320376.7770342  691595.8089597 2320666.8380083  691209.0609941
#Sta/Elev= 30
       0  115.74   88.11  114.72  101.65  111.64  123.08  108.98   155.1  107.45
   291.8  104.62  314.15  103.38  379.79  103.76  547.69  101.44   586.1  100.95
  618.25   98.97  637.98   96.24  660.63   96.14  738.85   93.96  780.28    91.2
  868.72   91.68  874.84   91.14  880.25    89.3   886.6    89.3  886.96    91.2
  890.13   91.82   935.6   91.91  957.84   92.95  974.92   93.63 1024.86  101.29
 1034.92     102 1066.85  107.98 1095.78  110.47 1200.21  113.72 1308.71  114.15
#Mann= 7 ,-1 , 0
       0    .045       0  547.69      .1       0  660.63    .085       0
  868.72     .05       0  890.13     .08       0  957.84     .09       0
 1095.78    .045       0
Bank Sta=868.72,890.13
XS Rating Curve= 0 ,0
Exp/Cntr=0.3,0.1

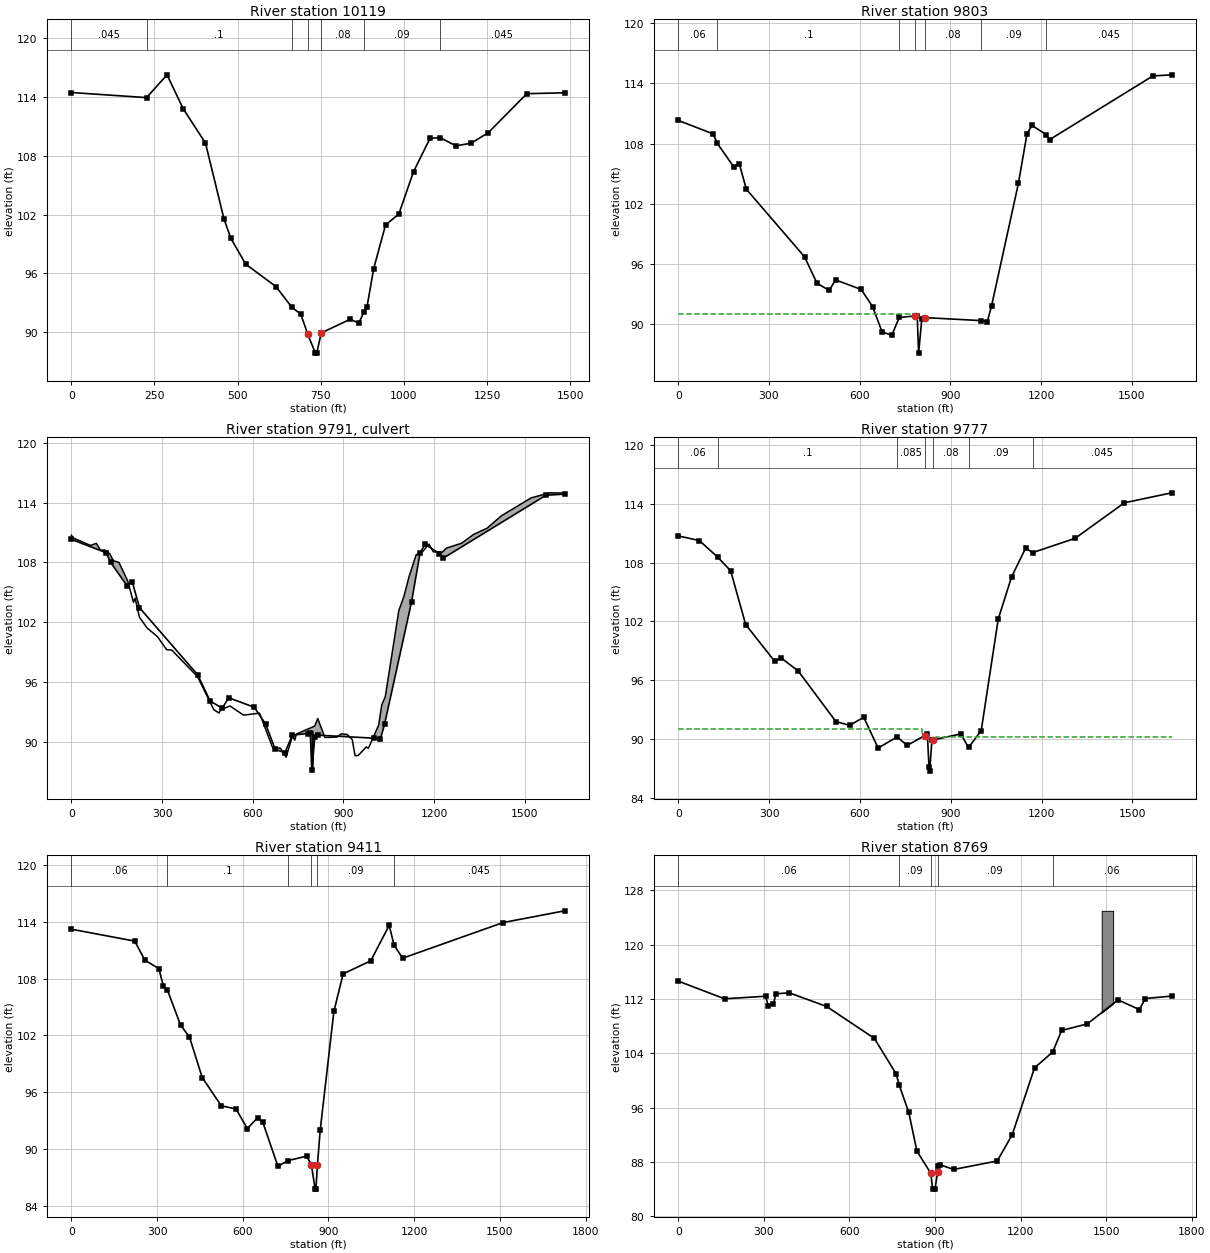
Type RM Length L Ch R = 1 ,10119   ,396.35,315.92,335.77
XS GIS Cut Line= 5
 2320608.1069655  692677.6278935 2320636.5991278  692386.3746785
 2320703.0808399  692057.1319137 2320712.5782274  691892.5105313
 2320715.7440232  691202.3670436
#Sta/Elev= 30
       0  114.42   226.1   113.9  287.85  116.22  336.27  112.77  403.34  109.28
  458.89  101.57  479.35   99.59  524.52   96.94  615.54   94.66  663.16   92.55
  689.81   91.87  711.04   89.81  733.83   87.89  738.15   87.89  751.14   89.94
  838.91   91.34   864.5   90.95  879.17   92.03  889.07    92.6  909.26    96.5
  944.84  100.94  984.77  102.05 1029.09  106.37 1078.63  109.76 1108.97  109.82
  1156.8  108.99 1202.13  109.26 1253.82  110.33 1369.68   114.3 1483.58  114.39
#Mann= 7 ,-1 , 0
       0    .045       0   226.1      .1       0  663.16    .085       0
  711.04     .05       0  751.14     .08       0  879.17     .09       0
 1108.97    .045       0
Bank Sta=711.04,751.14
XS Rating Curve= 0 ,0
Exp/Cntr=0.5,0.3

Type RM Length L Ch R = 1 ,9803    ,26.91,26.16,23.97
BEGIN DESCRIPTION:
Surveyed Section
END DESCRIPTION:
XS GIS Cut Line= 6
 2321159.9458693  692758.9560536 2321126.6974925  692226.9820244
    2321063.4967     692031.3744 2320899.9162046  691965.4297232
 2320847.7872505  691896.3285515 2320769.5625521  691272.0145515
#Sta/Elev= 30
       0  110.31  114.94  108.97  129.56  108.01  183.94  105.67  201.85     106
  225.39  103.45  417.99   96.71  458.83   94.09  499.38   93.36  520.22   94.42
  605.09   93.46  642.85   91.76  674.29   89.23  706.43    88.9     731   90.67
  783.54  90.826 790.397  90.845 795.129  87.118 805.572  90.506  816.34  90.657
 1000.56   90.36 1022.08   90.26 1036.16   91.79 1125.14  104.03 1153.55  108.97
 1170.07  109.81 1217.58  108.88 1228.29  108.39 1569.86  114.74  1631.7  114.85
#Mann= 7 ,-1 , 0
       0     .06       0  129.56      .1       0     731    .085       0
  783.54     .05       0  816.34     .08       0 1000.56     .09       0
 1217.58    .045       0
#XS Ineff= 2 , 0
       0  778.54      91  821.34       0      90
Permanent Ineff=
       F       F
Bank Sta=783.54,816.34
XS Rating Curve= 0 ,0
Exp/Cntr=0.5,0.3

Type RM Length L Ch R = 2 ,9791    ,,,
BEGIN DESCRIPTION:
Sanitary Sewer Easement
END DESCRIPTION:
Bridge Culvert--1,0,-1,-1, 0
Deck Dist Width WeirC Skew NumUp NumDn MinLoCord MaxHiCord MaxSubmerge Is_Ogee
3,20,2.6,0, 60, 60, , , 0.95, 0, 0,0,,
       0    6.92   63.38    82.8   96.46  109.28  127.12  138.52   157.6  186.71
  205.39  210.73   225.2  250.07  284.75  315.07  332.08  417.16  471.37  488.93
  493.59  524.89  569.46  622.45  664.81  691.73  710.33  730.78  739.21 744.199
 804.755 814.983 838.523 878.298  892.49     912  928.96  938.25  949.05  975.46
  982.37 1016.42 1026.69 1038.21 1083.09 1100.46 1116.99 1140.41 1158.45  1182.8
 1197.01 1225.84 1240.48 1290.63 1330.52 1374.48 1423.08 1520.54 1581.82 1623.47
  110.73  110.44   109.7  109.91  109.22  109.25  108.87  108.17     108  106.11
  103.99   104.4  102.51  101.43  100.55   99.24    99.2   96.54   93.21   92.88
    93.2   93.59   92.67   92.87   89.48   89.35   88.45   90.54   90.17  90.769
  91.573  92.331  90.424  90.469   90.79   90.74   90.23    88.6   88.63   89.48
   89.34   91.67   93.71   94.51  103.16  104.63  106.57  108.76  108.96  109.84
  109.06     109  109.43  109.92  110.81  111.42  112.69  114.47  114.98  114.96
                                                                                
                                                                                
                                                                                
                                                                                
                                                                                
                                                                                
       0    6.92   63.38    82.8   96.46  109.28  127.12  138.52   157.6  186.71
  205.39  210.73   225.2  250.07  284.75  315.07  332.08  417.16  471.37  488.93
  493.59  524.89  569.46  622.45  664.81  691.73  710.33  730.78  739.21 744.199
 804.755 814.983 838.523 878.298  892.49     912  928.96  938.25  949.05  975.46
  982.37 1016.42 1026.69 1038.21 1083.09 1100.46 1116.99 1140.41 1158.45  1182.8
 1197.01 1225.84 1240.48 1290.63 1330.52 1374.48 1423.08 1520.54 1581.82 1623.47
  110.73  110.44   109.7  109.91  109.22  109.25  108.87  108.17     108  106.11
  103.99   104.4  102.51  101.43  100.55   99.24    99.2   96.54   93.21   92.88
    93.2   93.59   92.67   92.87   89.48   89.35   88.45   90.54   90.17  90.769
  91.573  92.331  90.424  90.469   90.79   90.74   90.23    88.6   88.63   89.48
   89.34   91.67   93.71   94.51  103.16  104.63  106.57  108.76  108.96  109.84
  109.06     109  109.43  109.92  110.81  111.42  112.69  114.47  114.98  114.96
                                                                                
                                                                                
                                                                                
                                                                                
                                                                                
                                                                                
BR Coef=-1 , 0 , 0 ,, 0 ,,,0.8,0,,0,
WSPro=,,,, 1 ,,,, 0 ,,,, 0 ,,,,-1 ,-1 ,-1 , 0 , 0 , 0 , 0 , 0
Culvert=1,4,,20.01,0.022,0.2,1,55,2,87.0517,798.06,87.1494,828.02,Culvert #1  , 0 ,3.01
Culvert Bottom n=0.022
BC Design=,, 0 ,, 0 ,,,,,,
BC Use User HTab Curves=0
BC User HTab FreeFlow(D)= 0

Type RM Length L Ch R = 1 ,9777    ,341.45,365.99,403.6
BEGIN DESCRIPTION:
Surveyed Section
END DESCRIPTION:
XS GIS Cut Line= 6
  2321207.740411   692752.721983 2321182.8041284    692247.76226
 2321103.8392334  692027.4917635 2320931.0553761  691947.7249802
 2320918.4462473  691919.9848967 2320845.5416516  691256.1855724
#Sta/Elev= 30
       0  110.73    69.9  110.25  130.01  108.57  173.19  107.17  222.76  101.69
  318.16   97.95  340.47   98.27  396.63   96.94  520.81   91.79  566.18   91.41
   612.6   92.23  660.19   89.09  722.54   90.23  756.19   89.36  814.26  90.372
  822.73  90.526 828.106  87.182 830.224  86.739 837.881  89.901  840.98  89.917
  932.85   90.53  958.76   89.15 1000.55   90.87 1056.78  102.24 1100.74  106.54
 1147.35  109.49 1170.07  109.02 1310.69  110.48 1473.08   114.1 1629.17  115.12
#Mann= 7 ,-1 , 0
       0     .06       0  130.01      .1       0  722.54    .085       0
  814.26    .045       0  840.98     .08       0  958.76     .09       0
 1170.07    .045       0
#XS Ineff= 2 , 0
       0  804.26   91.06  850.98       0    90.2
Permanent Ineff=
       F       F
Bank Sta=814.26,840.98
XS Rating Curve= 0 ,0
Exp/Cntr=0.5,0.3

Type RM Length L Ch R = 1 ,9411    ,638.24,642.5,667.77
XS GIS Cut Line= 6
 2321595.8352599  692851.7466634 2321494.5297938  692611.1461814
  2321336.240003  691933.6658769 2321253.9293118  691822.8630234
  2321010.163034  691344.8278552   2320975.33928  691256.1855724
#Sta/Elev= 30
       0  113.21  221.99  111.95  256.85  109.96  306.52  109.03  322.42  107.16
  335.87  106.83  382.25  103.08  413.32  101.83  458.07   97.54  524.91   94.55
  576.46   94.22  616.06   92.15  651.66   93.28  670.23   92.81  723.05   88.16
  758.95   88.77  823.29   89.23  840.27   88.33  853.25   85.75  856.03   85.75
  861.46   88.33  871.02   91.97  918.98  104.53   951.3  108.49 1048.09  109.87
 1112.56  113.62  1129.7  111.51 1159.87  110.15 1511.15  113.91 1726.84  115.15
#Mann= 6 ,-1 , 0
       0     .06       0  335.87      .1       0  758.95    .085       0
  840.27    .045       0  861.46     .09       0  1129.7    .045       0
Bank Sta=840.27,861.46
XS Rating Curve= 0 ,0
Exp/Cntr=0.3,0.1

Type RM Length L Ch R = 1 ,8769    ,841.97,842.44,753.32
XS GIS Cut Line= 5
 2321994.7255326  692797.9281345 2321944.0727996  692433.8616157
 2321950.4043912  692003.3133848 2321959.9017787  691373.3200176
 2322007.3887159  691075.7352109
#Sta/Elev= 30
       0  114.64  162.62  112.03  306.29  112.41  315.58     111  333.51   111.2
  342.69  112.77  389.51  112.91  520.17   110.9  687.53   106.2   764.2  100.95
  774.85   99.31  808.29   95.28  836.88   89.56  885.37   86.32  891.97   83.97
   900.2   83.97  909.34   86.49  910.45   87.36  918.74   87.55  965.91   86.87
 1118.46   88.12  1170.8   91.98 1249.15  101.85 1312.93  104.19 1344.13  107.36
  1434.2  108.33 1541.87  111.87 1616.65  110.44 1637.65  112.07 1729.58  112.43
#Mann= 5 ,-1 , 0
       0     .06       0  774.85     .09       0  885.37     .05       0
  909.34     .09       0 1312.93     .06       0
#Block Obstruct= 1 ,-1
 1484.68 1524.67     125
Bank Sta=885.37,909.34
XS Rating Curve= 0 ,0
Exp/Cntr=0.3,0.1

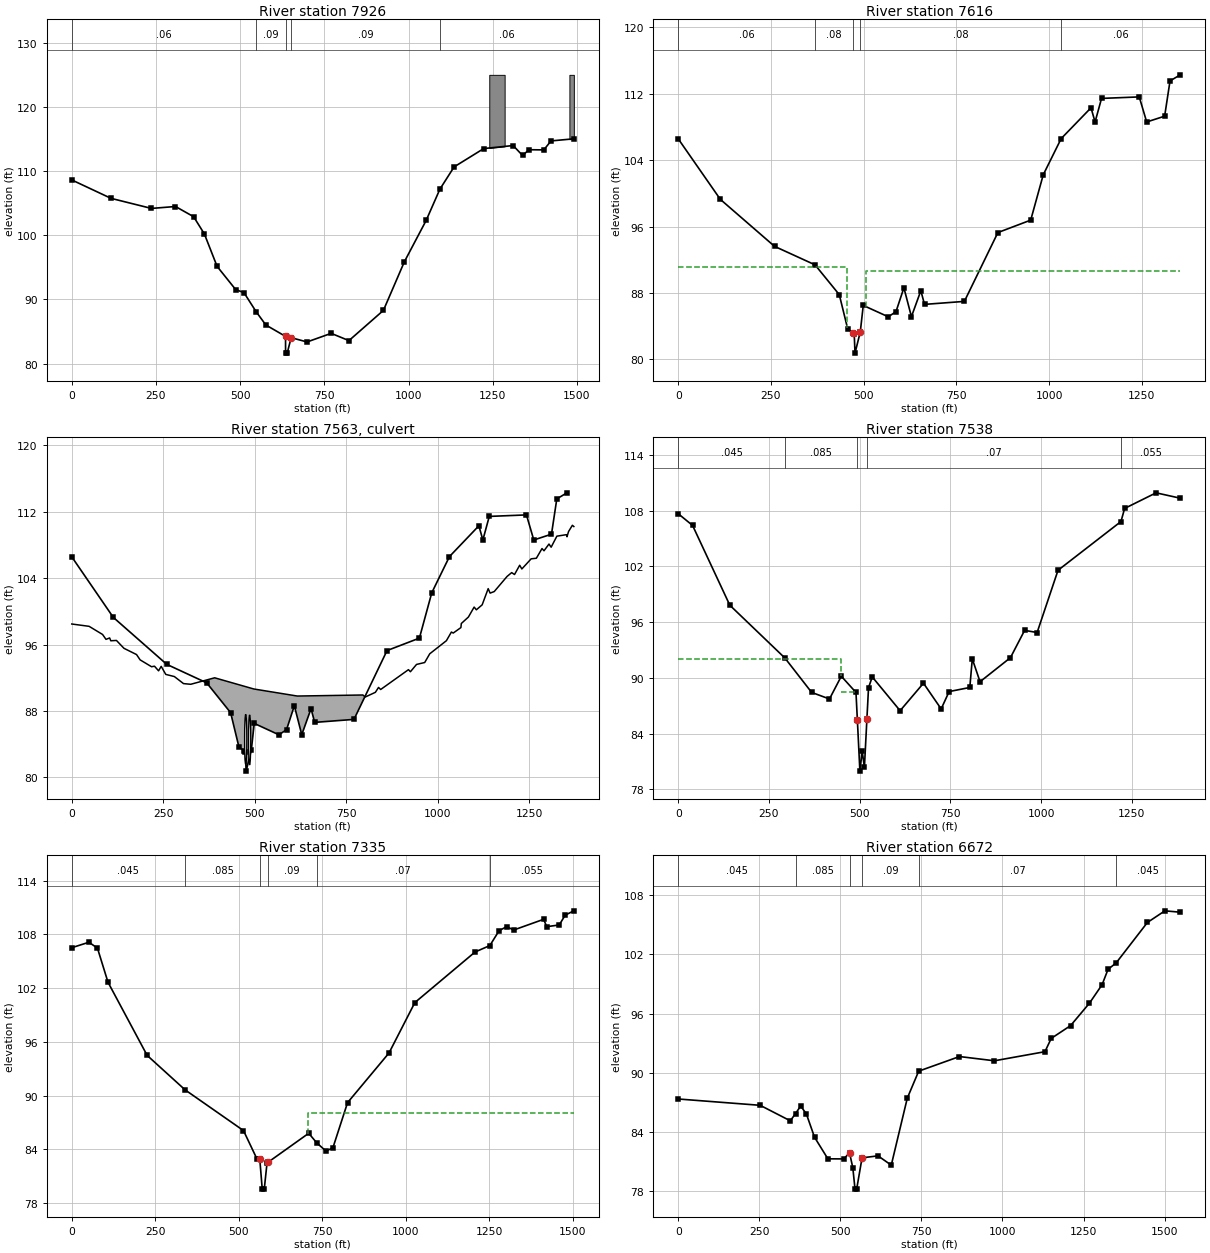
Type RM Length L Ch R = 1 ,7926    ,313.31,310.71,362.99
XS GIS Cut Line= 5
 2322751.3507325  692677.6278935 2322786.1744865  692424.3642283
 2322770.3455074  692053.9661179 2322681.7032246  691800.7024527
 2322406.2789886  691272.0145515
#Sta/Elev= 30
       0  108.62  116.59  105.75  236.55  104.18  307.99  104.48  361.87  102.89
  393.87  100.19  431.49   95.15  486.73   91.53  511.28   91.06  547.29    88.1
  576.15   86.02  634.74   84.24  634.88   81.63  639.71   81.63   651.4   84.04
  698.55   83.37  770.31   84.71  822.98   83.58  925.36   88.29  987.52   95.86
  1052.3  102.31 1093.08  107.18 1135.25  110.65 1223.35  113.51 1310.58  113.98
 1338.62  112.43 1357.54  113.33 1401.58   113.3 1423.09   114.7 1490.84  115.03
#Mann= 5 ,-1 , 0
       0     .06       0  547.29     .09       0  634.74     .05       0
   651.4     .09       0 1093.08     .06       0
#Block Obstruct= 2 ,-1
 1239.71 1285.33     125 1477.63 1490.84     125
Bank Sta=634.74,651.4
XS Rating Curve= 0 ,0
Exp/Cntr=0.5,0.3

Type RM Length L Ch R = 1 ,7616    ,80.99,77.5,66.8
BEGIN DESCRIPTION:
Surveyed Section
END DESCRIPTION:
XS GIS Cut Line= 6
 2323039.4096436  692467.8576564    2323085.7378     692084.6897
    2323082.0606     692036.8921    2323067.0003     691997.7896
    2323062.9158     691908.4601 2322586.7293501  691281.5119389
#Sta/Elev= 30
       0  106.57  113.48   99.28   259.6   93.62  368.83   91.39 434.183  87.798
  456.65  83.706     471  83.184  474.38  83.061 476.546  80.759 490.757  83.319
 498.742  86.507 566.144  85.136  586.98   85.75  608.32   88.63  628.61   85.15
  653.99   88.28  663.87   86.63  771.36   86.99  861.65   95.28  950.17   96.78
  983.94  102.24 1032.27   106.6  1112.7  110.31 1123.64   108.6 1141.12  111.44
 1242.76  111.62 1262.78   108.6 1311.19   109.3 1325.71  113.55 1353.44  114.28
#Mann= 5 ,-1 , 0
       0     .06       0  368.83     .08       0     471     .05       0
 490.757     .08       0 1032.27     .06       0
#XS Ineff= 2 , 0
       0     456   91.15  505.76       0    90.7
Permanent Ineff=
       F       F
Bank Sta=471,490.757
XS Rating Curve= 0 ,0
Exp/Cntr=0.5,0.3

Type RM Length L Ch R = 2 ,7563    ,,,
BEGIN DESCRIPTION:
Frank Price Church Rd
END DESCRIPTION:
Bridge Culvert--1,0,-1,-1, 0
Deck Dist Width WeirC Skew NumUp NumDn MinLoCord MaxHiCord MaxSubmerge Is_Ogee
30,22,2.6,0, 60, 60, , , 0.95, 0, 1,1,,
       0   47.39   84.15   93.55  103.54  106.65   122.1  142.69     177  186.81
  218.16  226.01  237.27   244.4  256.89   280.4  305.46  325.17  390.55 497.725
 616.426  795.65  802.26  829.79  838.44  844.24  920.24  925.59  942.28  964.61
  978.37 1023.96 1037.55 1042.55 1063.61  1064.7 1084.11 1099.77  1105.8 1121.71
 1138.14 1143.43 1154.73 1189.81 1202.34 1210.14 1224.27 1230.14 1255.61 1269.85
 1285.25 1290.73  1304.3 1310.21 1325.88    1352 1353.55 1357.85 1368.24 1372.28
   98.48    98.2   97.22   96.63    96.8   96.46    96.5   95.55    94.8   94.16
   93.33    93.4   92.84   93.38   92.41   92.15    91.3   91.22  92.001  90.652
  89.804   89.93   89.69   90.25   90.84   90.59   92.98   92.73   93.61   93.84
   94.89   96.47   97.51   97.39   98.05   98.54   99.32  100.52  100.19  100.79
  102.74   102.2  102.39  104.21  104.67  104.44  105.56  105.11  106.33   106.4
  107.57   107.3  108.11  107.73  109.06  109.24  108.99  109.62  110.37  110.22
                                                                                
                                                                                
                                                                                
                                                                                
                                                                                
                                                                                
       0   47.39   84.15   93.55  103.54  106.65   122.1  142.69     177  186.81
  218.16  226.01  237.27   244.4  256.89   280.4  305.46  325.17  390.55 497.725
 616.426  795.65  802.26  829.79  838.44  844.24  920.24  925.59  942.28  964.61
  978.37 1023.96 1037.55 1042.55 1063.61  1064.7 1084.11 1099.77  1105.8 1121.71
 1138.14 1143.43 1154.73 1189.81 1202.34 1210.14 1224.27 1230.14 1255.61 1269.85
 1285.25 1290.73  1304.3 1310.21 1325.88    1352 1353.55 1357.85 1368.24 1372.28
   98.48    98.2   97.22   96.63    96.8   96.46    96.5   95.55    94.8   94.16
   93.33    93.4   92.84   93.38   92.41   92.15    91.3   91.22  92.001  90.652
  89.804   89.93   89.69   90.25   90.84   90.59   92.98   92.73   93.61   93.84
   94.89   96.47   97.51   97.39   98.05   98.54   99.32  100.52  100.19  100.79
  102.74   102.2  102.39  104.21  104.67  104.44  105.56  105.11  106.33   106.4
  107.57   107.3  108.11  107.73  109.06  109.24  108.99  109.62  110.37  110.22
                                                                                
                                                                                
                                                                                
                                                                                
                                                                                
                                                                                
BR Coef=-1 , 0 , 0 ,, 0 ,,,0.8,0,,0,
WSPro=,,,, 1 ,,,, 0 ,,,, 0 ,,,,-1 ,-1 ,-1 , 0 , 0 , 0 , 0 , 0
Culvert=1,6,,60,0.024,0.5,1,2,1,81.587,475.405,81.9228,502.935,Culvert #1  , 0 ,9.3
Culvert Bottom n=0.024
Culvert=1,6,,60,0.021,0.5,1,2,1,81.5171,486.155,82.124,513.685,Culvert #2  , 0 ,7.5
Culvert Bottom n=0.021
BC Design=,, 0 ,, 0 ,,,,,,
BC Use User HTab Curves=0
BC User HTab FreeFlow(D)= 0

Type RM Length L Ch R = 1 ,7538    ,198.45,203.25,202.44
BEGIN DESCRIPTION:
Surveyed Section
END DESCRIPTION:
XS GIS Cut Line= 6
 2323141.0309665  692481.7257801    2323165.8201     692109.8355
    2323159.6119     692033.3897    2323129.4772     691919.2755
 2323091.0529904  691817.3907814 2322678.5374288  691243.5223891
#Sta/Elev= 30
       0  107.68    39.5  106.42   142.1   97.83     294   92.14  367.62   88.44
  416.72  87.731 449.371  90.183 489.771  88.436  493.58   85.51 500.562  79.963
 506.926  82.108 513.014   80.37  519.93  85.595 524.359  88.941 534.597   90.11
  611.39   86.47  675.76   89.43  724.51   86.66  746.48   88.53  803.45   88.97
  810.31   92.05  831.64   89.59  915.44   92.18  954.48   95.12  988.95   94.89
 1046.52  101.59    1220  106.84 1230.09  108.25 1316.82  109.93 1383.53  109.35
#Mann= 5 ,-1 , 0
       0    .045       0     294    .085       0  493.58    .055       0
  519.93     .07       0    1220    .055       0
#XS Ineff= 3 ,-1
       0     449      92     449  488.63    88.5     527  567.64  88.518
Permanent Ineff=
       F       F       F
Bank Sta=493.58,519.93
XS Rating Curve= 0 ,0
Exp/Cntr=0.5,0.3

Type RM Length L Ch R = 1 ,7335    ,652.33,662.75,689.8
XS GIS Cut Line= 5
 2323280.0386336  692503.5091237 2323368.6809165  692114.1162384
 2323333.8571625   691914.671102 2323242.0490839  691626.5836828
 2322979.2880312  691088.3983942
#Sta/Elev= 30
       0  106.52   51.42  107.13   76.91  106.47  108.47  102.66  225.66   94.49
  339.25   90.64  514.06   86.09  554.56   82.91  562.91   82.88   570.2   79.55
   576.3   79.57  584.49   82.45   586.8   82.53   709.4   85.79  733.35   84.72
  761.02    83.8  781.82   84.17   825.6   89.21  949.72   94.76  1027.1  100.39
 1207.32  106.04 1251.62  106.76 1279.31  108.42 1301.75  108.87  1323.3   108.5
 1412.45  109.69 1422.06  108.87 1459.35  109.06 1477.21  110.16 1503.08  110.64
#Mann= 6 ,-1 , 0
       0    .045       0  339.25    .085       0  562.91    .055       0
   586.8     .09       0  733.35     .07       0 1251.62    .055       0
#XS Ineff= 2 , 0
       0                     706       0      88
Permanent Ineff=
       F       F
Bank Sta=562.91,586.8
XS Rating Curve= 0 ,0
Exp/Cntr=0.3,0.1

Type RM Length L Ch R = 1 ,6672    ,700.27,683.65,662.02
XS GIS Cut Line= 5
 2324115.8087289  692462.3537781 2324036.6638336  692202.7585212
 2323973.3479172  691807.0340443 2323862.5450637   691658.241641
 2323558.6286654  691037.7456612
#Sta/Elev= 30
       0   87.36   252.7   86.72   345.7   85.15  361.91   85.89  377.71   86.65
  395.28   85.84  420.35   83.49  461.55    81.3  510.91   81.29  528.29   81.92
  538.44    80.4  545.26   78.23  550.37   78.23  566.96    81.4  616.18    81.6
  657.09   80.66  706.46   87.44  741.62   90.18  867.48   91.66  975.16   91.23
 1131.02   92.15 1150.51    93.5 1210.02   94.79 1268.21   97.06 1307.38   98.94
 1325.59  100.49 1350.84  101.15 1447.07  105.24 1501.06  106.42 1548.59  106.28
#Mann= 6 ,-1 , 0
       0    .045       0  361.91    .085       0  528.29    .055       0
  566.96     .09       0  741.62     .07       0 1350.84    .045       0
Bank Sta=528.29,566.96
XS Rating Curve= 0 ,0
Exp/Cntr=0.3,0.1