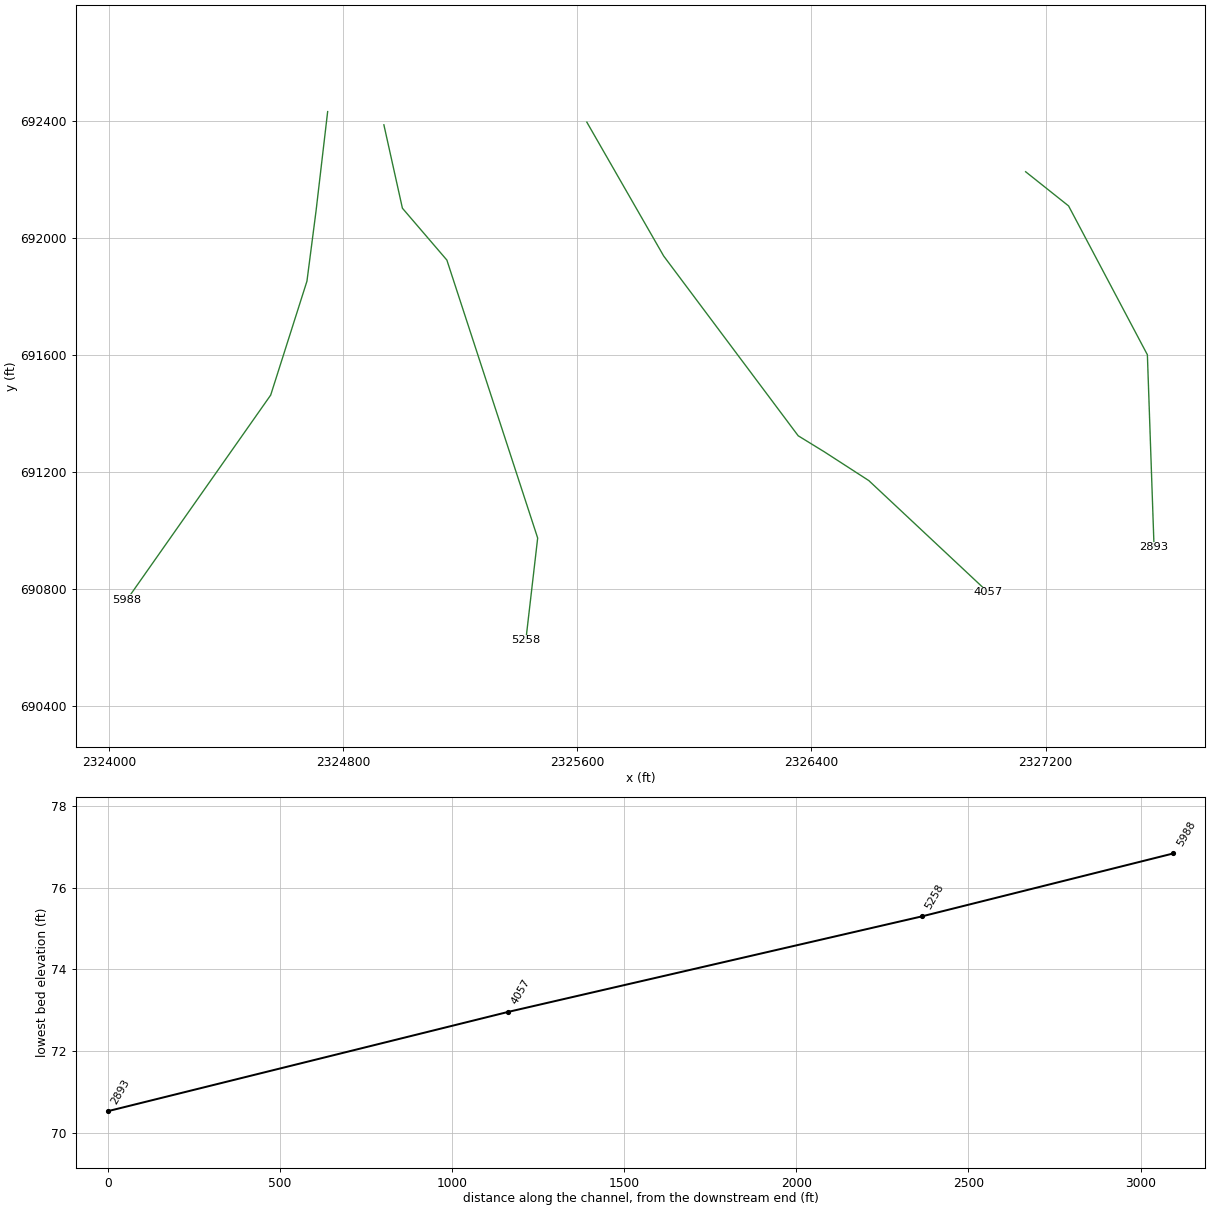
HEC-RAS study dtl_contentnea_crk_trib.prj: dtl_contentnea_crk_trib

--- dtl_contentnea_crk_trib.g01 (geometry) --- (continued)

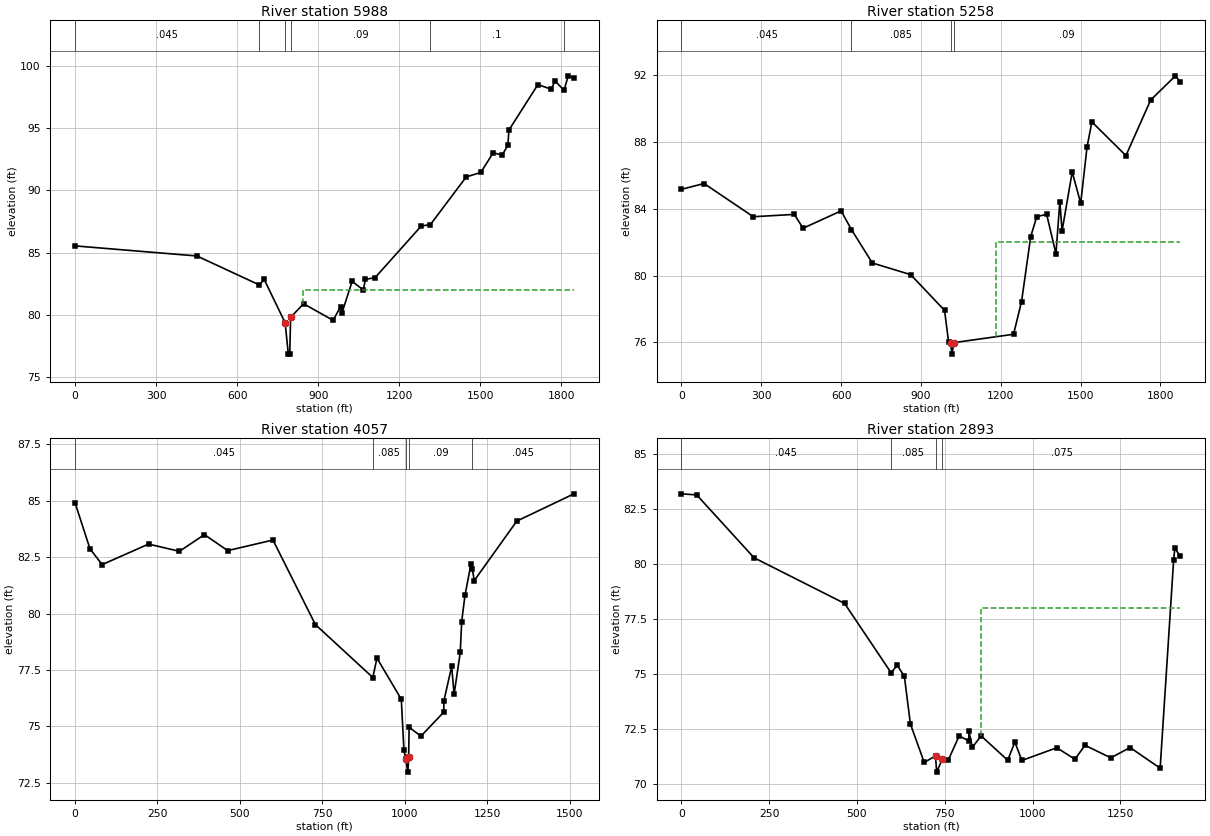
Type RM Length L Ch R = 1 ,5988    ,618.23,730.03,821.25
XS GIS Cut Line= 5
 2324746.8018184  692431.6036702  2324706.993414  692091.0206552
 2324676.0313218  691852.1702292 2324552.1829527  691462.9324978
 2324061.2126325  690764.0738437
#Sta/Elev= 30
       0   85.54  451.04   84.73  682.39    82.4  700.05   82.84   777.6   79.36
  789.26   76.84  794.58   76.84  797.79   79.79  845.48   80.89  954.89   79.56
  982.95   80.66  987.78   80.15 1025.42   82.69  1066.7      82 1074.75   82.85
 1110.37   82.99 1281.29   87.14 1314.93   87.25 1447.41   91.08 1501.72   91.45
 1547.41   93.03  1580.5   92.83 1601.66   93.64 1605.48   94.85 1712.91   98.51
 1761.92   98.13 1776.07    98.8 1809.37   98.05 1825.05   99.21  1846.3   99.03
#Mann= 6 ,-1 , 0
       0    .045       0  682.39    .085       0   777.6     .05       0
  797.79     .09       0 1314.93      .1       0 1809.37     .06       0
#XS Ineff= 2 , 0
       0                     845       0      82
Permanent Ineff=
       F       F
Bank Sta=777.6,797.79
XS Rating Curve= 0 ,0
Exp/Cntr=0.3,0.1

Type RM Length L Ch R = 1 ,5258    ,1191.83,1201.62,1267.92
XS GIS Cut Line= 5
 2324938.9156409  692386.3746785 2325002.2315573  692101.4530551
 2325154.1897564  691924.1684895 2325464.4377463  690974.4297448
 2325424.0438911  690625.6092227
#Sta/Elev= 30
       0   85.17   84.91   85.52  270.11   83.53   424.3   83.67  457.06   82.84
   600.1   83.88  638.95   82.76  717.36   80.76  861.68   80.06  988.97   77.92
  1003.9   76.05 1011.71   75.98 1016.46    75.3 1024.57   75.99 1248.25   76.49
 1278.36   78.45 1312.77   82.34 1335.66   83.54 1372.74   83.67 1407.56   81.31
  1422.3   84.44 1430.64   82.68 1468.73   86.21 1500.65   84.34  1524.5   87.71
 1542.67   89.21 1670.65   87.19 1763.61   90.52 1856.81   91.97 1875.65   91.59
#Mann= 4 ,-1 , 0
       0    .045       0  638.95    .085       0 1011.71     .05       0
 1024.57     .09       0
#XS Ineff= 2 , 0
       0                    1184       0      82
Permanent Ineff=
       F       F
Bank Sta=1011.71,1024.57
XS Rating Curve= 0 ,0
Exp/Cntr=0.3,0.1

Type RM Length L Ch R = 1 ,4057    ,1185.59,1163.81,1025.8
BEGIN DESCRIPTION:
Surveyed Section
END DESCRIPTION:
XS GIS Cut Line= 6
 2325632.4250422  692395.5006626 2325895.0234533  691938.0711723
    2326354.6144     691323.8642    2326443.5371       691269.27
    2326595.9344     691170.7387 2327003.5565969  690788.9130897
#Sta/Elev= 30
       0   84.92  45.417   82.87  82.427   82.17 222.859   83.08 316.558   82.76
 392.416    83.5 462.872   82.79 600.122   83.26 728.674   79.51 902.834   77.16
 915.358  78.021 989.138  76.196 997.121  73.9391002.443  73.5511008.974  72.962
1011.393  73.6271012.845  74.9531048.646  74.558 1117.83  75.6231118.303   76.13
1141.914   77.651149.155   76.411167.872   78.271172.178   79.641182.226   80.81
1200.427    82.2  1204.5   81.98 1210.27   81.461339.218    84.11512.664   85.31
#Mann= 5 ,-1 , 0
       0    .045       0 902.834    .085       01002.443     .05       0
1011.393     .09       0  1204.5    .045       0
Bank Sta=1002.443,1011.393
XS Rating Curve= 0 ,0
Skew Angle= 45
Exp/Cntr=0.3,0.1

Type RM Length L Ch R = 1 ,2893    ,3102.09,2893.02,3016.72
XS GIS Cut Line= 4
 2327131.7772604  692226.0823329 2327278.5387877  692109.3103831
 2327547.8400908  691600.6301439 2327570.6707666  690942.8033668
#Sta/Elev= 30
       0    83.2   43.45   83.15  206.69   80.29  464.67   78.21  597.31   75.05
  614.37    75.4  634.93   74.89  652.14   72.72  691.52   70.97   723.6   71.27
  726.95   70.53   743.5   71.15  760.59    71.1  791.01   72.18  818.45   71.95
   818.8   72.38  828.46   71.66  853.58   72.18  929.24   71.07  949.71    71.9
  969.56   71.06 1068.91   71.64 1120.62   71.12 1149.58   71.75 1222.99   71.18
  1277.8   71.65 1363.48   70.71 1402.01   80.21 1405.25   80.72 1421.34   80.35
#Mann= 4 ,-1 , 0
       0    .045       0  597.31    .085       0   723.6     .05       0
   743.5    .075       0
#XS Ineff= 2 , 0
       0                  853.58       0      78
Permanent Ineff=
       F       F
Bank Sta=723.6,743.5
XS Rating Curve= 0 ,0
Exp/Cntr=0.3,0.1

Chan Stop Cuts=-1
Use User Specified Reach Order=0
User Specified Reach Order=Contentnea Creek,Tributary