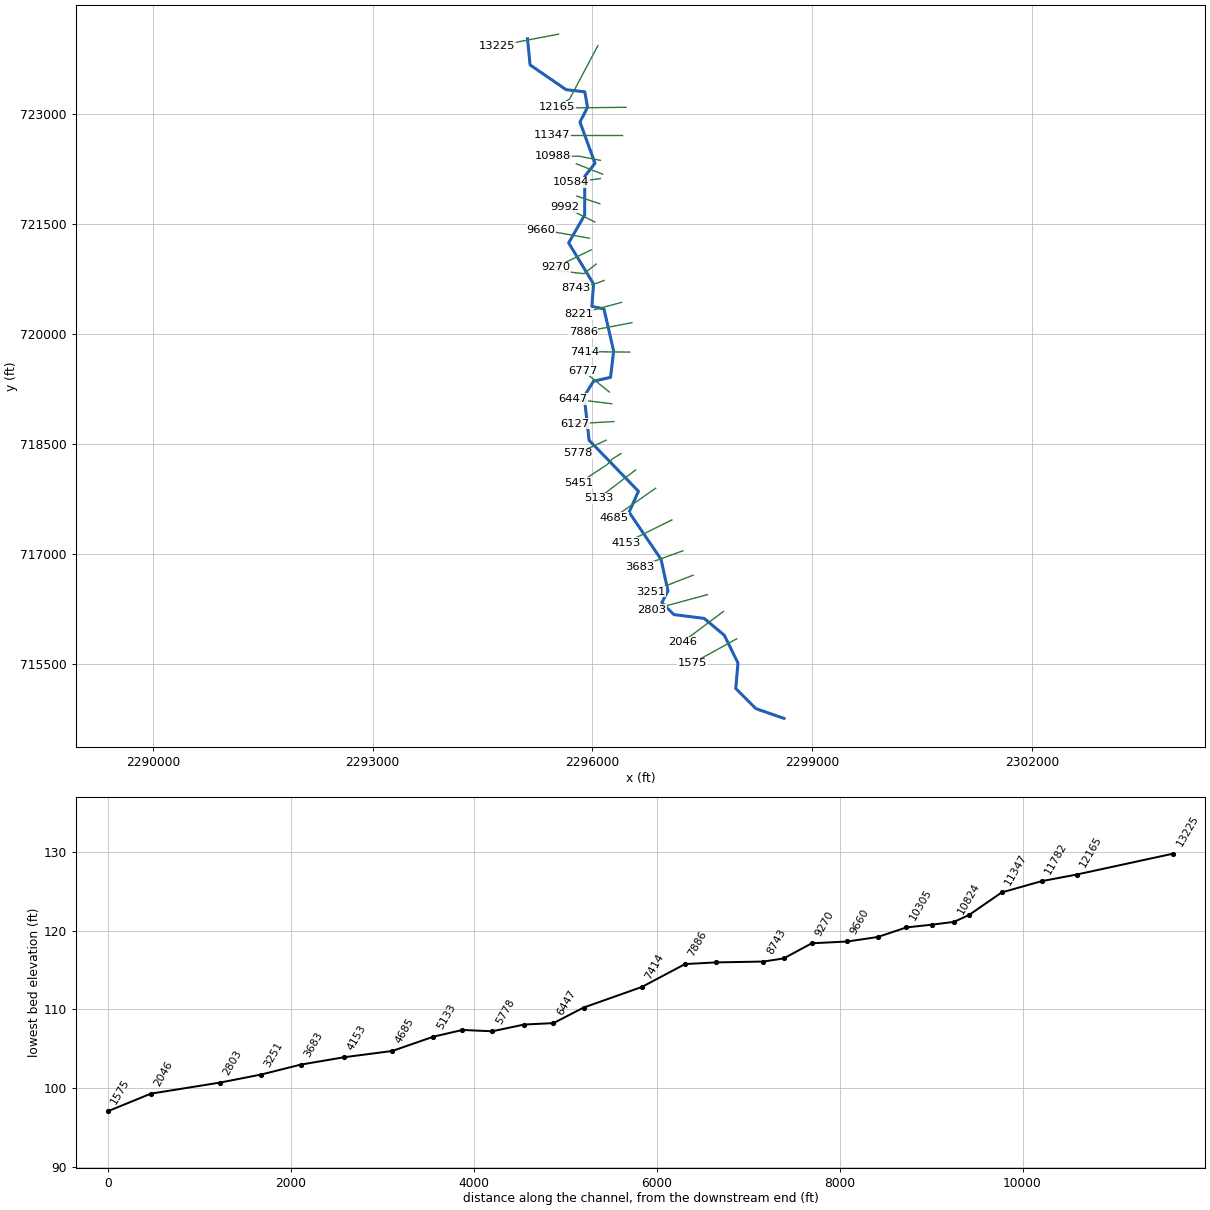
--- dtl_shepard_bch.prj (project) ---

Proj Title=dtl_shepard_bch
Current Plan=p01
Default Exp/Contr=0.3,0.1
English Units
Geom File=g02
Flow File=f01
Flow File=f02
Plan File=p01
Plan File=p02
Y Axis Title=Elevation
X Axis Title(PF)=Main Channel Distance
X Axis Title(XS)=Station
BEGIN DESCRIPTION:
END DESCRIPTION:
DSS Export Rating Curves= 0
DSS Export Rating Curve Sorted= 0
DSS Export Volume Flow Curves= 0
DXF OffsetX= 0
DXF OffsetY= 0
DXF ScaleX= 1
DXF ScaleY= 10

--- dtl_shepard_bch.p01 (plan) ---

Plan Title=dtl_shepard_bch
Program Version=4.00
Short Identifier=multi profil
Geom File=g02
Flow File=f01
Subcritical Flow
K Sum by GR= 0
Std Step Tol= 0.01
Critical Tol= 0.01
Num of Std Step Trials= 20
Max Error Tol= 0.3
Flow Tol Ratio= 0.001
Split Flow NTrial= 30
Split Flow Tol= 0.02
Split Flow Ratio= 0.02
Log Output Level= 0
Friction Slope Method= 1
Unsteady Friction Slope Method= 2
Unsteady Bridges Friction Slope Method= 1
Parabolic Critical Depth
Global Vel Dist= 0 , 0 , 0
Global Log Level= 0
CheckData=True
Encroach Param=-1 ,10,10, 2
Encroach River=Shepards_Branch
Encroach Reach=1
Encroach Node=13225
       1  411.66  505.27
Encroach Node=12165
       1  621.25  760.18
Encroach Node=11782
       1  412.21  542.59
Encroach Node=11347
       1  416.02  533.56
Encroach Node=10988
       1   63.21  182.06
Encroach Node=10824
       1   95.86  210.78
Encroach Node=10584
       1   85.99  221.85
Encroach Node=10305
       4       1
Encroach Node=9992
       1   108.6  268.78
Encroach Node=9660
       1     128     294
Encroach Node=9270
       1     120     294
Encroach Node=8965
       1     100     297
Encroach Node=8743
       1      90     220
Encroach Node=8221
       1  167.07     309
Encroach Node=7886
       4       1
Encroach Node=7414
       1  156.22  333.44
Encroach Node=6777
       1  174.21  326.61
Encroach Node=6447
       1  306.07  464.18
Encroach Node=6127
       1  342.86   508.5
Encroach Node=5778
       1   90.02  252.02
Encroach Node=5451
       1  158.56  340.48
Encroach Node=5133
       1  124.49     310
Encroach Node=4685
       1  300.29 487.791
Encroach Node=4153
       1  304.44  488.89
Encroach Node=3683
       4       1
Encroach Node=3251
       1  304.59  489.19
Encroach Node=2803
       1     386     595
Encroach Node=2046
       1     179     395
Encroach Node=1575
       1      40  212.32
Encroach Node=1276
       1      92     384
Encroach Node=995
       1     210  494.72
Encroach Node=441
       1  227.78  340.11
Encroach Node=108
       4       1
Computation Interval=1HOUR
Output Interval=1HOUR
Run HTab= 0
Run UNet= 0
Run PostProcess= 0
Run WQNet= 0
UNET Theta= 1
UNET Theta Warmup= 1
UNET ZTol= 0.02
UNET ZSATol= 0.05
UNET MxIter= 20
UNET MaxInSteps= 0
UNET DtIC= 0
UNET DtMin= 0
UNET MaxCRTS= 20
UNET WFStab= 2
UNET SFStab= 1
UNET WFX= 1
UNET SFX= 1
UNET DSS MLevel= 4
UNET DZMax Abort= 100
UNET Convert EG Bridges= 0
UNET Use Existing IB Tables=-1
UNET Froude Reduction=False
UNET Froude Limit= 1
UNET Froude Power= 10
UNET Time Slicing=0,0, 5
Instantaneous Interval=1HOUR
Write IC File= 0
Echo Input=False
Echo Output=False
Write Detailed= 0
Detailed Automatic Start=False, 10
WQ ULTIMATE=-1
WQ Max Comp Step=1HOUR
WQ Output Interval=15MIN
WQ Output Selected Increments= 0
WQ Output face flow=0
WQ Output face velocity=0
WQ Output face area=0
WQ Output face dispersion=0
WQ Output cell volume=0
WQ Output cell surface area=0
WQ Output cell continuity=0
WQ Output face conc=0
WQ Output face dconc_dx=0
WQ Output face courant=0
WQ Output face peclet=0
WQ Output face adv mass=0
WQ Output face disp mass=0
WQ Output cell mass=0
WQ Output cell source sink temp=0
WQ Output cell source sink nsm=0
WQ Output MaxMinRange=-1
WQ Daily Max Min Mean=-1
WQ Daily Range=0
WQ Daily Time=0
WQ Create Restart=0
WQ Fixed Restart=0
WQ System Summary=False
Sorting and Armoring Iterations= 10
XS Update Threshold= 0.02
Hydraulics Update Threshold= 0.02
Energy Slope Method= 1
Volume Change Method= 0
XS Weighting Method= 0
Number of US Weighted Cross Sections= 1
Number of DS Weighted Cross Sections= 1
Upstream XS Weight=0.25
Main XS Weight=0.5
Downstream XS Weight=0.25
Number of DS XS's Weighted with US Boundary= 1
Upstream Boundary Weight= 1
Weight of XSs Associated with US Boundary= 0
Number of US XS's Weighted with DS Boundary= 1
Downstream Boundary Weight= 0.5
Weight of XSs Associated with DS Boundary= 0.5
Sediment Output Level= 4
Mass or Volume Output= 0
Output Increment Type= 1
Profile and TS Output Increment= 10
XS Output Flag= 0
XS Output Increment= 10
Disregard all LS=0
Disregard all Conn=0
Disregard all Breaches=0
Disregard all Pumps=0

--- dtl_shepard_bch.p02 (plan) ---

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Plan Title=dtl_shepard_bch_future
Program Version=3.13
Short Identifier=future
Geom File=g02
Flow File=f02
Encroach Param=-1 ,0,0, 0
UNET Convert EG Bridges=-1

--- dtl_shepard_bch.f01 (steady flow) ---

Flow Title=dtl_shepard_bch
Program Version=3.13
Number of Profiles= 6
Profile Names=100yr,FW,10yr,25yr,50yr,500yr
River Rch & RM=Shepards_Branch,1               ,13225
     870     870     370     540     690    1400
River Rch & RM=Shepards_Branch,1               ,9270
    1040    1040     450     650     830    1660
Boundary for River Rch & Prof#=Shepards_Branch,1               , 1
Up Type= 0
Dn Type= 3
Dn Slope=0.00258
Boundary for River Rch & Prof#=Shepards_Branch,1               , 2
Up Type= 0
Dn Type= 3
Dn Slope=0.00258
Boundary for River Rch & Prof#=Shepards_Branch,1               , 3
Up Type= 0
Dn Type= 3
Dn Slope=0.00258
Boundary for River Rch & Prof#=Shepards_Branch,1               , 4
Up Type= 0
Dn Type= 3
Dn Slope=0.00258
Boundary for River Rch & Prof#=Shepards_Branch,1               , 5
Up Type= 0
Dn Type= 3
Dn Slope=0.00258
Boundary for River Rch & Prof#=Shepards_Branch,1               , 6
Up Type= 0
Dn Type= 3
Dn Slope=0.00258
DSS Import GetInterval= 0
DSS Import GetPeak= 0
DSS Import FillOption= 0

--- dtl_shepard_bch.f02 (steady flow) ---

Flow Title=dtl_shepard_bch_future
Program Version=3.13
Number of Profiles= 3
Profile Names=F10%,F20%,F35%
River Rch & RM=Shepards_Branch,1               ,13225
    1510    1930    2360
River Rch & RM=Shepards_Branch,1               ,9270
    1790    2300    2810
Boundary for River Rch & Prof#=Shepards_Branch,1               , 1
Up Type= 0
Dn Type= 3
Dn Slope=0.00258
Boundary for River Rch & Prof#=Shepards_Branch,1               , 2
Up Type= 0
Dn Type= 3
Dn Slope=0.00258
Boundary for River Rch & Prof#=Shepards_Branch,1               , 3
Up Type= 0
Dn Type= 3
Dn Slope=0.00258
DSS Import GetInterval= 0
DSS Import GetPeak= 0
DSS Import FillOption= 0

--- dtl_shepard_bch.g02 (geometry) ---

Geom Title=dtl_shepard_bch
Program Version=4.00

River Reach=Shepards_Branch ,1
Reach XY= 30
 2295114.2642676  724030.0545068 2295149.7476207  723673.8016411
 2295640.8372285   723336.000119 2295896.4090987  723306.6969851
 2295933.2689291  723095.2379581 2295830.4494023  722894.4488822
 2296035.6325384  722331.3979887 2295895.7548462  722152.1002195
 2295894.4832308  721625.6514505 2295676.1088132  721244.7960881
 2296015.8466031  720683.3649946 2295992.8135327  720378.1768104
 2296157.8838713  720343.6272047  2296289.844171  719767.3205865
 2296247.6720429  719408.9869805 2296015.2207763  719356.5714988
 2295888.0128628  719149.5910776 2295954.8667543  718550.9779074
 2296628.2540186  717854.7540019 2296500.8144647  717568.6389201
 2296936.6397943  716925.9983301 2297031.4721576  716494.2084204
 2296947.7371985  716335.8181965 2297110.1628421   716171.374843
 2297525.6540597  716118.8304658 2297800.8060422  715888.6450682
 2297987.0765226  715509.7040847 2297956.8214969  715160.8419166
  2298231.516112  714887.0435319  2298614.882426  714754.4286784

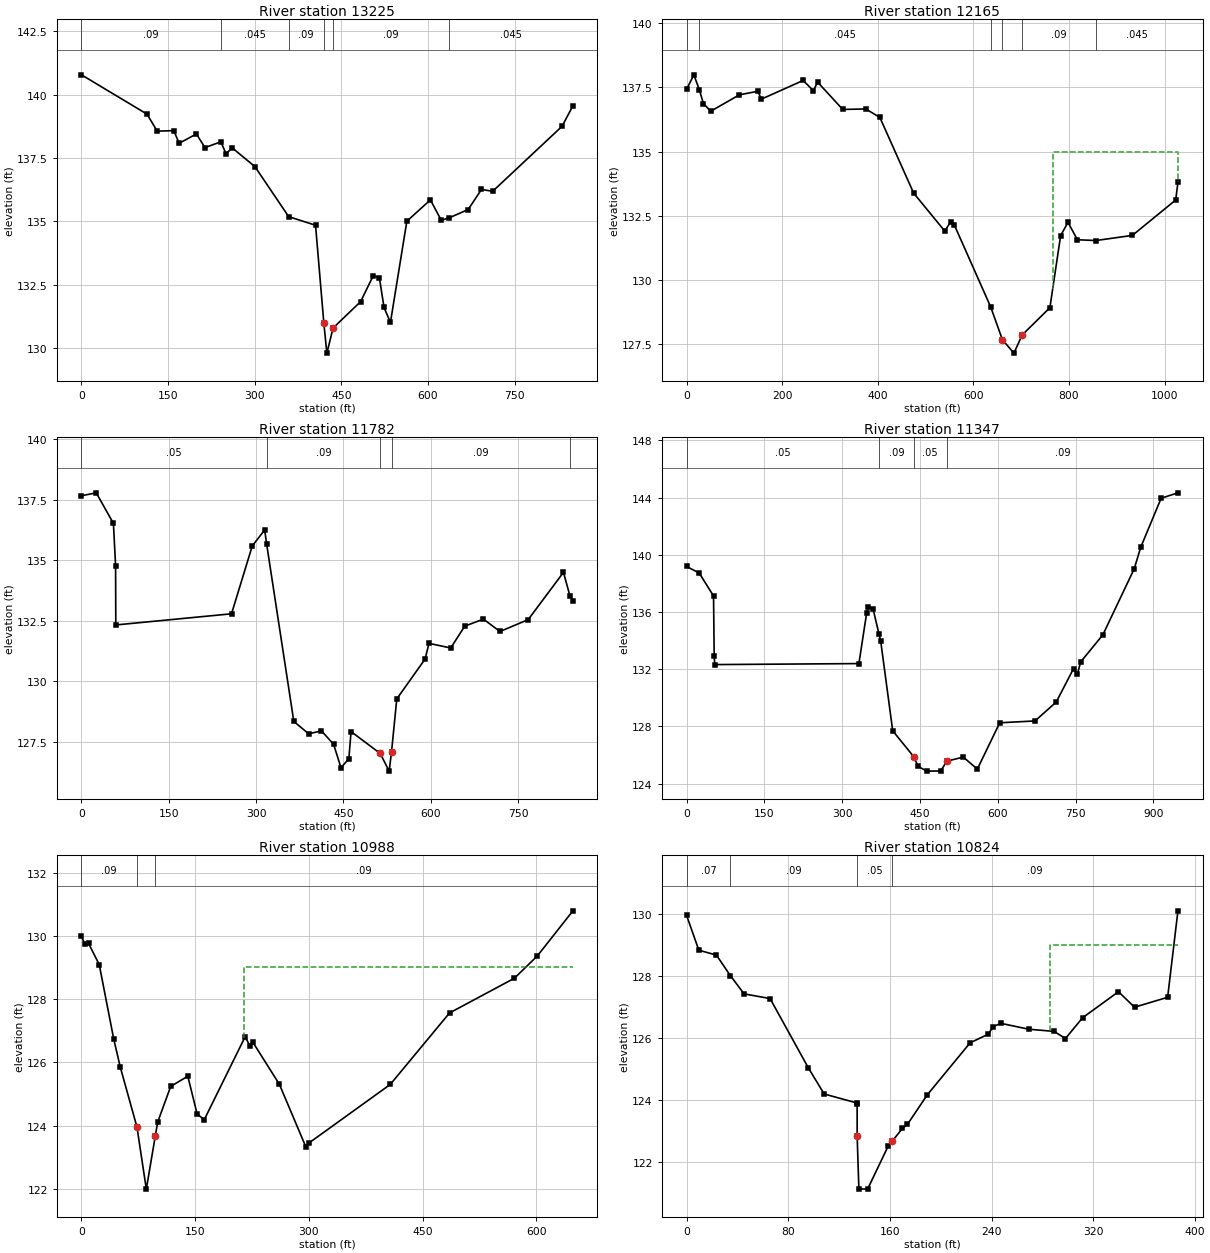
Type RM Length L Ch R = 1 ,13225   ,1042.07,1059.56,1077.05
XS GIS Cut Line= 2
 2295536.9804316   724093.804866  2294701.001492  723933.6660431
#Sta/Elev= 30
       0  140.78  113.52  139.23  131.12  138.56  159.93  138.58  169.11  138.08
  199.05  138.45  213.86  137.91  241.39  138.14  250.32  137.67  261.14   137.9
  300.43  137.16  358.86  135.19  405.39  134.85   419.8  130.98     425  129.81
  435.79   130.8  483.43  131.84  505.27  132.86  515.91  132.79  524.01  131.61
  535.12  131.02  563.53  135.01  604.31  135.85  623.05  135.05  635.83135.1322
   669.7  135.47  692.75  136.26  712.22  136.19   832.3  138.75  851.18  139.56
#Mann= 6 ,-1 , 0
       0     .09       0  241.39    .045       0  358.86     .09       0
   419.8     .05       0  435.79     .09       0  635.83    .045       0
#XS Ineff= 2 , 0
       0                  505.27       0  132.86
Permanent Ineff=
       F       T
Bank Sta=419.8,435.79
XS Rating Curve= 0 ,0
Exp/Cntr=0.3,0.1

Type RM Length L Ch R = 1 ,12165   ,409.05,382.63,356.2
XS GIS Cut Line= 3
 2296074.3954643  723936.3802604 2295688.9766025  723208.9700143
 2295515.2666929  723100.4013208
#Sta/Elev= 30
       0  137.42   15.39  137.99   26.83  137.41   35.41  136.87   50.62  136.57
  110.57  137.21  149.45  137.35  156.41  137.04  243.96  137.77  265.62  137.37
  274.14  137.71  326.82  136.64  374.98  136.66  404.46  136.33  475.14  133.38
   540.2   131.9  552.73  132.26  560.42  132.13  636.37  128.94  660.89  127.66
  684.93  127.14  702.29  127.85  760.18  128.91  782.64  131.72  798.08  132.24
  817.66  131.56  856.37  131.53  932.77  131.73 1023.34  133.11 1028.06   133.8
#Mann= 6 ,-1 , 0
       0     .09       0   26.83    .045       0  636.37     .09       0
  660.89     .05       0  702.29     .09       0  856.37    .045       0
#XS Ineff= 2 , 0
       0                     766       0     135
Permanent Ineff=
       F       F
Bank Sta=660.89,702.29
XS Rating Curve= 0 ,0
Exp/Cntr=0.3,0.1

Type RM Length L Ch R = 1 ,11782   ,438.88,434.92,430.97
XS GIS Cut Line= 2
  2296459.814326  723094.9728861 2295615.6927344  723086.8302341
#Sta/Elev= 30
       0  137.66   25.36  137.78   54.84  136.52   58.56  134.78   58.94  132.33
  257.72  132.79  293.35  135.59  314.68  136.25  318.08  135.66  364.72  128.35
  390.19  127.84  412.21  127.96  433.01  127.41  445.74  126.44  459.21  126.81
  463.07  127.93   513.1  127.03  528.52   126.3  532.59   127.1  541.61  129.28
  590.12  130.92  596.97  131.57  634.29  131.38  658.29  132.28  690.39  132.57
  718.87  132.06  767.31  132.55  827.93   134.5   839.1  133.52  844.16  133.33
#Mann= 5 ,-1 , 0
       0     .05       0  318.08     .09       0   513.1     .05       0
  532.59     .09       0   839.1    .045       0
#XS Ineff= 2 , 0
       0  314.68  136.25               0
Permanent Ineff=
       T       F
Bank Sta=513.1,532.59
XS Rating Curve= 0 ,0
Exp/Cntr=0.3,0.1

Type RM Length L Ch R = 1 ,11347   ,360.96,359.05,357.12
XS GIS Cut Line= 2
 2296400.1015446  722720.4108937 2295452.8396942  722720.4108937
#Sta/Elev= 30
       0  139.18   24.31  138.73   52.13  137.12   53.37  132.91   54.47  132.32
   332.3  132.39  347.31  135.94  350.53  136.36  359.53  136.22  371.04  134.46
  374.38  133.95  397.46  127.69  437.98  125.88  446.48   125.2   463.1  124.87
  489.93  124.88  501.86  125.57  533.56  125.85  560.57  125.01  603.75  128.25
  671.78  128.38  712.66   129.7  746.05  132.04  753.31  131.64  759.85  132.51
  802.53   134.4  863.02  139.02   875.5  140.52  914.86  143.95  947.26  144.33
#Mann= 4 ,-1 , 0
       0     .05       0  371.04     .09       0  437.98     .05       0
  501.86     .09       0
#XS Ineff= 2 , 0
       0  350.53  136.36               0
Permanent Ineff=
       T       F
Bank Sta=437.98,501.86
XS Rating Curve= 0 ,0
Exp/Cntr=0.3,0.1

Type RM Length L Ch R = 1 ,10988   ,167.508,164.55,161.6
XS GIS Cut Line= 5
 2296109.2404599   722371.502546 2295815.4473997  722428.3084549
 2295813.6722151  722428.3084549 2295543.4822127  722428.3084549
 2295466.3522078  722428.3084549
#Sta/Elev= 25
       0  129.98    4.16  129.75    9.36  129.76    23.4  129.09   42.59  126.73
   51.16  125.85   73.21  123.95   85.53  121.99   97.44  123.68  100.53  124.11
  117.73  125.24  140.27  125.56  152.62  124.36  162.06  124.19  215.94  126.81
  222.33  126.51  225.95  126.64  261.17   125.3  296.08  123.32  300.15  123.45
  407.35   125.3  485.52  127.56   571.2  128.66  601.23  129.36  648.33  130.79
#Mann= 3 ,-1 , 0
       0     .09       0   73.21     .05       0   97.44     .09       0
#XS Ineff= 2 , 0
       0                     215       0     129
Permanent Ineff=
       F       F
Bank Sta=73.21,97.44
XS Rating Curve= 0 ,0
Exp/Cntr=0.3,0.1

Type RM Length L Ch R = 1 ,10824   ,230.65,240.21,227.35
XS GIS Cut Line= 2
 2296139.4185991  722182.4453804 2295779.9437067  722324.4601527
#Sta/Elev= 30
       0  129.96    9.69  128.83   23.58  128.67   34.48  128.01    45.3  127.42
   65.72  127.27   95.86  125.03  108.27  124.19  133.99   123.9  134.19  123.88
  134.22  122.82  135.57  121.13  142.44  121.12  158.62  122.51  161.86  122.67
  169.79  123.08   173.8  123.21  189.31  124.16  223.03  125.84  237.34  126.12
  241.12  126.36  247.23  126.47  269.14  126.28  289.09  126.21  298.06  125.98
  311.51  126.65  339.74  127.49  352.35  126.99   378.4  127.31  386.51   130.1
#Mann= 4 ,-1 , 0
       0     .07       0   34.48     .09       0  134.22     .05       0
  161.86     .09       0
#XS Ineff= 2 , 0
       0                     286       0     129
Permanent Ineff=
       F       F
Bank Sta=134.22,161.86
XS Rating Curve= 0 ,0
Exp/Cntr=0.3,0.1

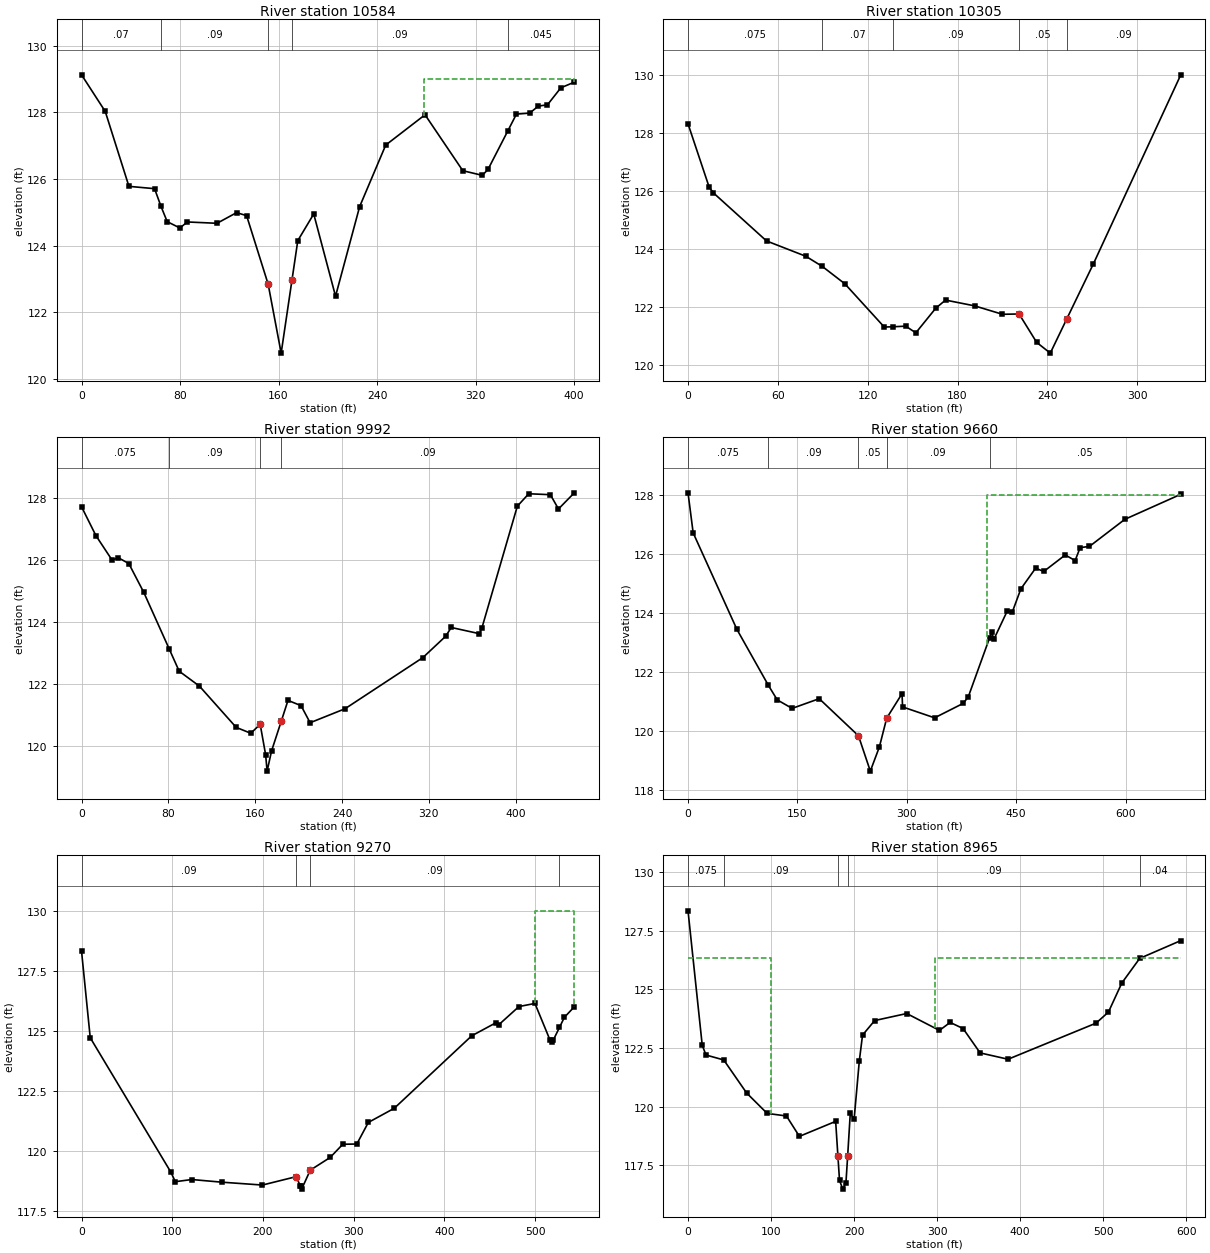
Type RM Length L Ch R = 1 ,10584   ,289.02,278.3,288.81
XS GIS Cut Line= 2
 2296109.2404599  722122.0891021 2295712.4866898  722069.7211548
#Sta/Elev= 30
       0  129.13   19.24  128.03   38.48  125.78    59.3  125.71   64.51  125.18
   69.54  124.72   79.82  124.53   85.99  124.71     110  124.67  125.92  124.99
  134.05   124.9  151.55  122.84  162.11  120.77  170.91  122.97  175.62  124.15
  188.56  124.95  206.27  122.48  225.84  125.17  247.03  127.02  278.96  127.93
  309.63  126.25  325.49  126.11  330.11  126.29  346.25  127.45  353.17  127.95
  363.97  127.98  370.92  128.19  378.39  128.23  389.26  128.74  400.19  128.91
#Mann= 5 ,-1 , 0
       0     .07       0   64.51     .09       0  151.55     .05       0
  170.91     .09       0  346.25    .045       0
#XS Ineff= 2 , 0
       0                     278       0     129
Permanent Ineff=
       F       F
Bank Sta=151.55,170.91
XS Rating Curve= 0 ,0
Exp/Cntr=0.3,0.1

Type RM Length L Ch R = 1 ,10305   ,315.31,313.76,311.74
XS GIS Cut Line= 2
 2296101.0032784  721779.3205804 2295788.7718883  721883.3977104
#Sta/Elev= 21
       0  128.33   14.09  126.15    16.9  125.95   52.43  124.29   78.74  123.76
   89.72  123.41  104.78  122.81  131.07  121.32  137.21  121.33  145.44  121.35
  152.15  121.12  165.48  121.97     172  122.25  191.46  122.05  209.99  121.76
  221.12  121.77  232.88  120.79  241.96  120.42  253.06  121.61  270.75   123.5
  329.12  130.02
#Mann= 5 ,-1 , 0
       0    .075       0   89.72     .07       0  137.21     .09       0
  221.12     .05       0  253.06     .09       0
Bank Sta=221.12,253.06
XS Rating Curve= 0 ,0
Exp/Cntr=0.3,0.1

Type RM Length L Ch R = 1 ,9992    ,326.21,331.23,336.13
XS GIS Cut Line= 2
   2296032.75598  721530.2179413 2295626.6845546   721733.253654
#Sta/Elev= 30
       0  127.72   13.25  126.79   28.15     126   33.76  126.08   43.54  125.89
   57.35  124.96   80.86  123.13   89.96  122.42   108.6  121.94  142.47  120.61
  155.95  120.42  164.57  120.71  169.59  119.73  170.96   119.2  175.05  119.85
  184.01  120.81   190.2  121.48  202.23  121.31  210.59  120.76  242.73  121.21
  314.51  122.86  335.55  123.55   340.6  123.83  366.56  123.63  368.82  123.81
  401.51  127.74  412.02  128.14  431.94  128.11   439.4  127.65     454  128.17
#Mann= 4 ,-1 , 0
       0    .075       0   80.86     .09       0  164.57     .05       0
  184.01     .09       0
Bank Sta=164.57,184.01
XS Rating Curve= 0 ,0
Exp/Cntr=0.3,0.1

Type RM Length L Ch R = 1 ,9660    ,378.63,390.21,398.41
XS GIS Cut Line= 2
 2295959.3901343  721308.4142215 2295293.9789749  721426.1408112
#Sta/Elev= 30
       0  128.08    7.05  126.72    67.1  123.44  110.28  121.54  122.33  121.05
  142.76  120.76  179.92  121.09  233.74  119.83     250  118.63  262.41  119.45
  272.49  120.43  293.48  121.26  294.23  120.81  338.16  120.44  377.32  120.93
  384.31  121.15  413.62  123.16  416.56  123.36  419.33   123.1  437.83  124.07
  444.82  124.04  456.47  124.82  476.66  125.52  487.85  125.41  517.32  125.97
  530.86  125.78  537.76  126.22  550.49  126.26  599.04  127.18  675.75  128.03
#Mann= 5 ,-1 , 0
       0    .075       0  110.28     .09       0  233.74     .05       0
  272.49     .09       0  413.62     .05       0
#XS Ineff= 2 , 0
       0                     410       0     128
Permanent Ineff=
       F       F
Bank Sta=233.74,272.49
XS Rating Curve= 0 ,0
Exp/Cntr=0.3,0.1

Type RM Length L Ch R = 1 ,9270    ,299.96,305.35,311.34
XS GIS Cut Line= 2
 2295983.2766887  721149.7392527 2295495.3085052  720910.8737084
#Sta/Elev= 28
       0  128.31    9.57  124.71   98.43  119.11  103.37  118.71  121.63   118.8
  154.49  118.69  199.39  118.57  236.67  118.92  241.09  118.54  241.42  118.51
  242.68   118.4  252.15  119.19  274.11  119.72  288.02  120.27   303.5  120.28
   316.2  121.18  344.79  121.77  430.18  124.79  456.67  125.33  460.27  125.26
  482.26  126.01  499.88  126.14  516.66   124.6  518.42  124.53  520.21  124.62
  526.94  125.14  532.33  125.56   543.3     126
#Mann= 4 ,-1 , 0
       0     .09       0  236.67     .05       0  252.15     .09       0
  526.94     .05       0
#XS Ineff= 1 ,-1
  499.88   543.3     130
Permanent Ineff=
       T
Bank Sta=236.67,252.15
XS Rating Curve= 0 ,0
Exp/Cntr=0.5,0.3

Type RM Length L Ch R = 1 ,8965    ,230.73,222.21,228.19
BEGIN DESCRIPTION:
Surveyed Section
END DESCRIPTION:
XS GIS Cut Line= 6
 2296052.1122669  720955.2676371    2295945.8696     720873.4915
 2295911.8983001     720842.2735    2295891.2523     720828.2847
 2295872.7879558  720825.8302511 2295506.3724115  720867.0408014
#Sta/Elev= 30
       0  128.35    17.1  122.62   21.64   122.2   43.03  121.99   70.61  120.58
   95.31  119.71  118.57   119.6 134.166  118.73 177.844  119.37 180.556  117.89
 182.502  116.85 186.429  116.48 190.249  116.76 192.283  117.88 195.439  119.71
  200.08  119.46 206.372  121.96  210.22  123.05  224.85  123.67  263.45  123.97
  302.88  123.25  315.74  123.59  331.34  123.33  351.88  122.29  385.53  122.02
  491.55  123.56  506.41  124.03  522.55  125.27  544.07  126.32  593.58  127.08
#Mann= 5 ,-1 , 0
       0    .075       0   43.03     .09       0 180.556     .05       0
 192.283     .09       0  544.07     .04       0
#XS Ineff= 2 , 0
       0     100  126.33     297       0  126.33
Permanent Ineff=
       F       F
Bank Sta=180.556,192.283
XS Rating Curve= 0 ,0
Exp/Cntr=0.5,0.3

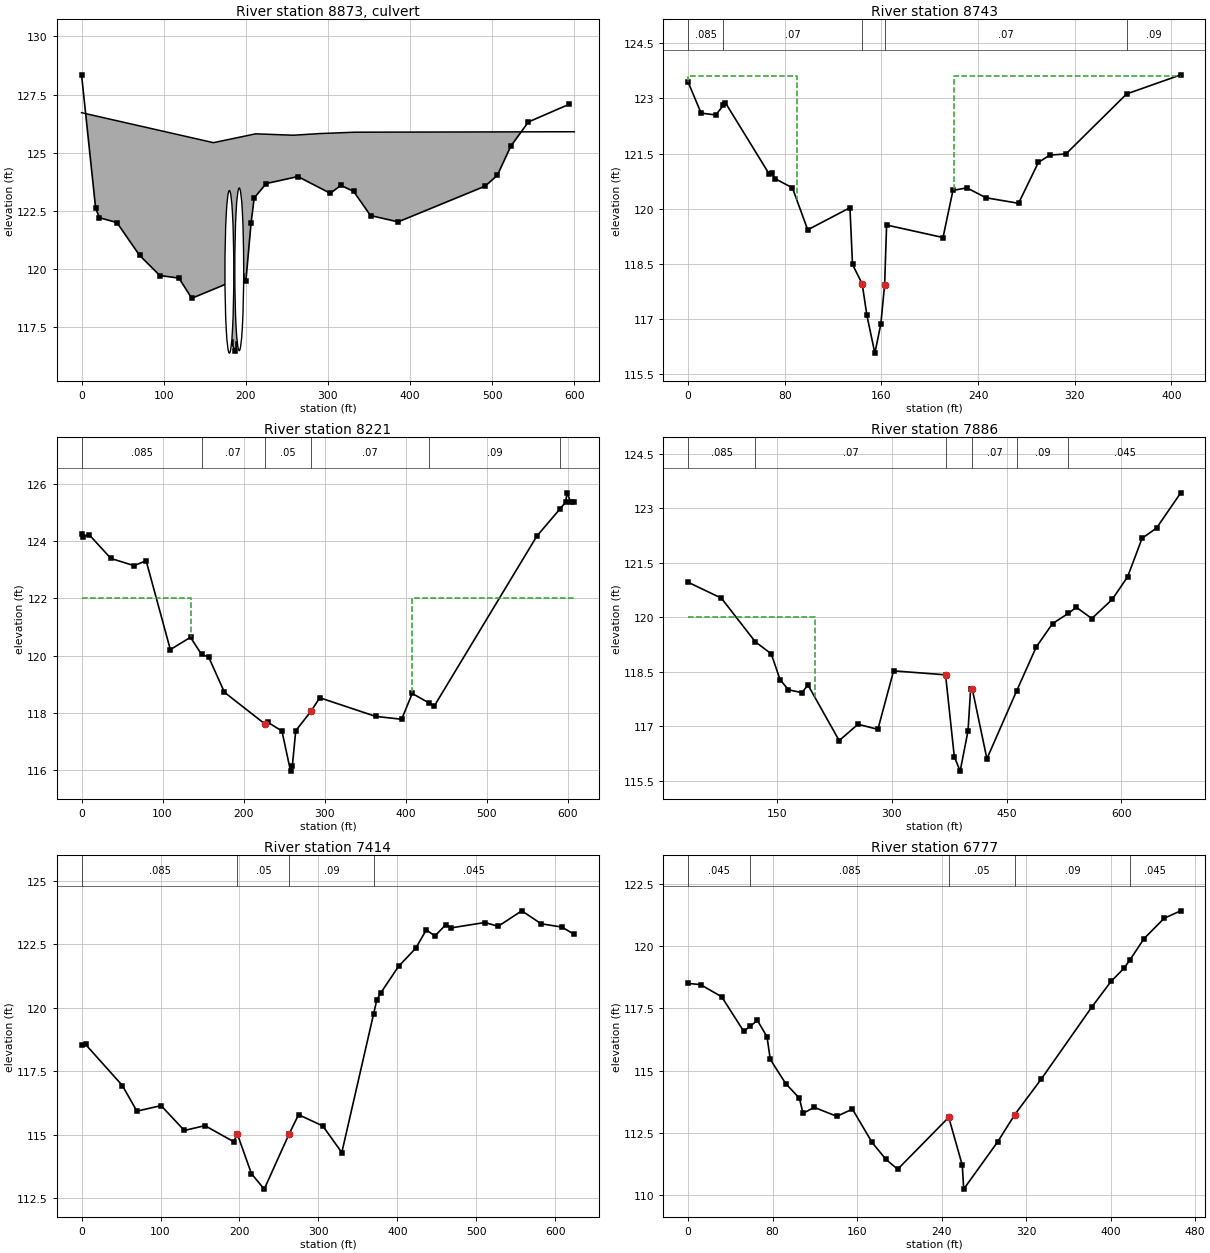
Type RM Length L Ch R = 2 ,8873    ,,,
BEGIN DESCRIPTION:
str59
END DESCRIPTION:
Bridge Culvert--1,0,-1,-1, 0
Deck Dist Width WeirC Skew NumUp NumDn MinLoCord MaxHiCord MaxSubmerge Is_Ogee
70,60.8,2.6,0, 7, 7, , , 0.98, 0, 1,1,,
       0  160.59  212.01  257.94  289.26  332.36     600
  126.72  125.43  125.81  125.75  125.82  125.88   125.9
                                                        
       0  160.59  212.01  257.94  289.26  332.36     600
  126.72  125.43  125.81  125.75  125.82  125.88   125.9
                                                        
BR Coef=-1 , 0 , 0 ,, 0 ,,,0.8,-1,,0,
WSPro=,,,, 1 ,,,, 0 ,,,, 0 ,,,,-1 ,-1 ,-1 , 0 , 0 , 0 , 0 , 0
Culvert=3,7,10.79,60.8,0.024,0.5,1,34,1,116.3698,180,116.4712,149,Culvert #1  , 0 ,70
Culvert Bottom n=0.024
Culvert=3,7,10.79,60.8,0.024,0.9,1,34,3,116.4756,192,116.6558,161,Culvert #2  , 0 ,70
Culvert Bottom n=0.024
BC Design=,, 0 ,, 0 ,,,,,,
BC Use User HTab Curves=0
BC User HTab FreeFlow(D)= 0

Type RM Length L Ch R = 1 ,8743    ,521.54,521.77,501.39
BEGIN DESCRIPTION:
Surveyed Section
END DESCRIPTION:
XS GIS Cut Line= 6
 2296159.7226207  720732.0495901    2296067.2493     720696.6719
    2296020.3953     720684.9603    2296013.9435     720686.3455
    2296006.5466     720680.4061  2295767.684251  720633.0631579
#Sta/Elev= 28
       0  123.45   10.83   122.6   22.89  122.55   29.28  122.81   30.96  122.88
    67.1  120.95   69.25  120.96   72.03  120.82   86.39  120.57  99.067  119.43
 133.997  120.03 136.131  118.49  144.15  117.96 148.011  117.11 154.613  116.08
 159.562  116.87  162.71  117.94 164.342  119.56 211.026  119.22  219.23   120.5
  230.74  120.57  246.63   120.3  273.54  120.15  289.92  121.26  299.39  121.46
  312.74  121.49  362.95  123.12  407.76  123.64
#Mann= 5 ,-1 , 0
       0    .085       0   29.28     .07       0  144.15     .05       0
  162.71     .07       0  362.95     .09       0
#XS Ineff= 2 , 0
       0      90  123.62     220       0  123.62
Permanent Ineff=
       F       F
Bank Sta=144.15,162.71
XS Rating Curve= 0 ,0
Exp/Cntr=0.5,0.3

Type RM Length L Ch R = 1 ,8221    ,339.47,335.17,336.76
XS GIS Cut Line= 2
 2296398.0715298  720432.4853874 2295810.6652018  720274.8885677
#Sta/Elev= 30
       0  124.23     1.6  124.15     9.7  124.21   36.19  123.39   64.78  123.14
   79.71  123.31  109.57  120.21  134.47  120.64  148.15  120.04  156.88  119.95
  176.37  118.72  226.11  117.62  230.08  117.67  247.32  117.37  257.96  115.97
  260.21  116.16  264.37  117.38  283.22  118.06     294  118.53  362.93  117.88
   395.1  117.78  408.14  118.68  429.38  118.34  435.32  118.24  561.96  124.17
  590.54  125.12  597.36  125.35  599.31  125.68  603.57  125.37  608.18  125.35
#Mann= 6 ,-1 , 0
       0    .085       0  148.15     .07       0  226.11     .05       0
  283.22     .07       0  429.38     .09       0  590.54    .045       0
#XS Ineff= 2 , 0
       0  134.47     122  408.14       0     122
Permanent Ineff=
       F       F
Bank Sta=226.11,283.22
XS Rating Curve= 0 ,0
Exp/Cntr=0.3,0.1

Type RM Length L Ch R = 1 ,7886    ,466.75,471.67,479.92
XS GIS Cut Line= 2
 2296538.7364598  720155.0628867 2295873.1829485  720028.7249403
#Sta/Elev= 30
   33.79  120.96   77.42  120.52  121.67  119.32  142.45  118.99  154.03  118.28
  164.88     118  182.51  117.92   190.5  118.13  231.26   116.6  255.81  117.05
  281.81  116.91  302.32  118.52  370.21  118.41  381.62  116.16  389.27  115.76
  399.57  116.87     403  118.03  405.04  118.03  424.22   116.1  462.89  117.96
  488.76  119.18  509.93  119.82  530.37   120.1  540.99  120.27  561.27  119.96
  588.07  120.49  608.03  121.11  626.94  122.17  645.77  122.45  677.44  123.42
#Mann= 6 ,-1 , 0
   33.79    .085       0  121.67     .07       0  370.21     .05       0
  405.04     .07       0  462.89     .09       0  530.37    .045       0
#XS Ineff= 2 , 0
       0     200     120               0
Permanent Ineff=
       F       F
Bank Sta=370.21,405.04
XS Rating Curve= 0 ,0
Exp/Cntr=0.3,0.1

Type RM Length L Ch R = 1 ,7414    ,649.79,636.79,623.79
XS GIS Cut Line= 3
 2296511.3849456  719753.9073457 2296017.7552376  719759.1171579
 2295887.5099321  719753.9073457
#Sta/Elev= 30
       0  118.52    5.06  118.55   51.69  116.93   70.09  115.92  100.69  116.14
  130.16  115.16  156.22  115.35  192.56  114.72  197.28  115.02  215.11  113.46
  231.34  112.85  263.08  115.04  274.86  115.78  305.47  115.34  329.58  114.29
  369.85  119.75  373.92   120.3  378.78  120.57  401.38  121.62   423.3  122.34
  436.56  123.06  447.48  122.82  461.55  123.27  468.35  123.14  510.72  123.35
  527.58   123.2  557.49  123.81  582.05   123.3  608.32  123.17  624.01  122.88
#Mann= 4 ,-1 , 0
       0    .085       0  197.28     .05       0  263.08     .09       0
  369.85    .045       0
Bank Sta=197.28,263.08
XS Rating Curve= 0 ,0
Exp/Cntr=0.3,0.1

Type RM Length L Ch R = 1 ,6777    ,320.89,330.08,340.21
XS GIS Cut Line= 2
 2296232.6599918  719208.1795155 2295869.2755893  719501.2314529
#Sta/Elev= 30
       0  118.51    11.9  118.46    31.9  117.97   52.76  116.58   58.96  116.79
    65.7  117.02    74.8  116.36   77.87  115.45   92.45  114.48  105.44  113.89
  108.88  113.28  119.48  113.52  140.87  113.16  155.64  113.45  174.21  112.11
  187.33  111.43  198.47  111.03  246.81  113.12  259.64  111.19  260.97  110.23
  293.07  112.13  309.33  113.23  334.23  114.65  382.08  117.55  400.47  118.59
  412.47  119.11  418.42  119.46  431.66  120.31   450.7  121.13  466.44  121.43
#Mann= 5 ,-1 , 0
       0    .045       0   58.96    .085       0  246.81     .05       0
  309.33     .09       0  418.42    .045       0
Bank Sta=246.81,309.33
XS Rating Curve= 0 ,0
Exp/Cntr=0.3,0.1

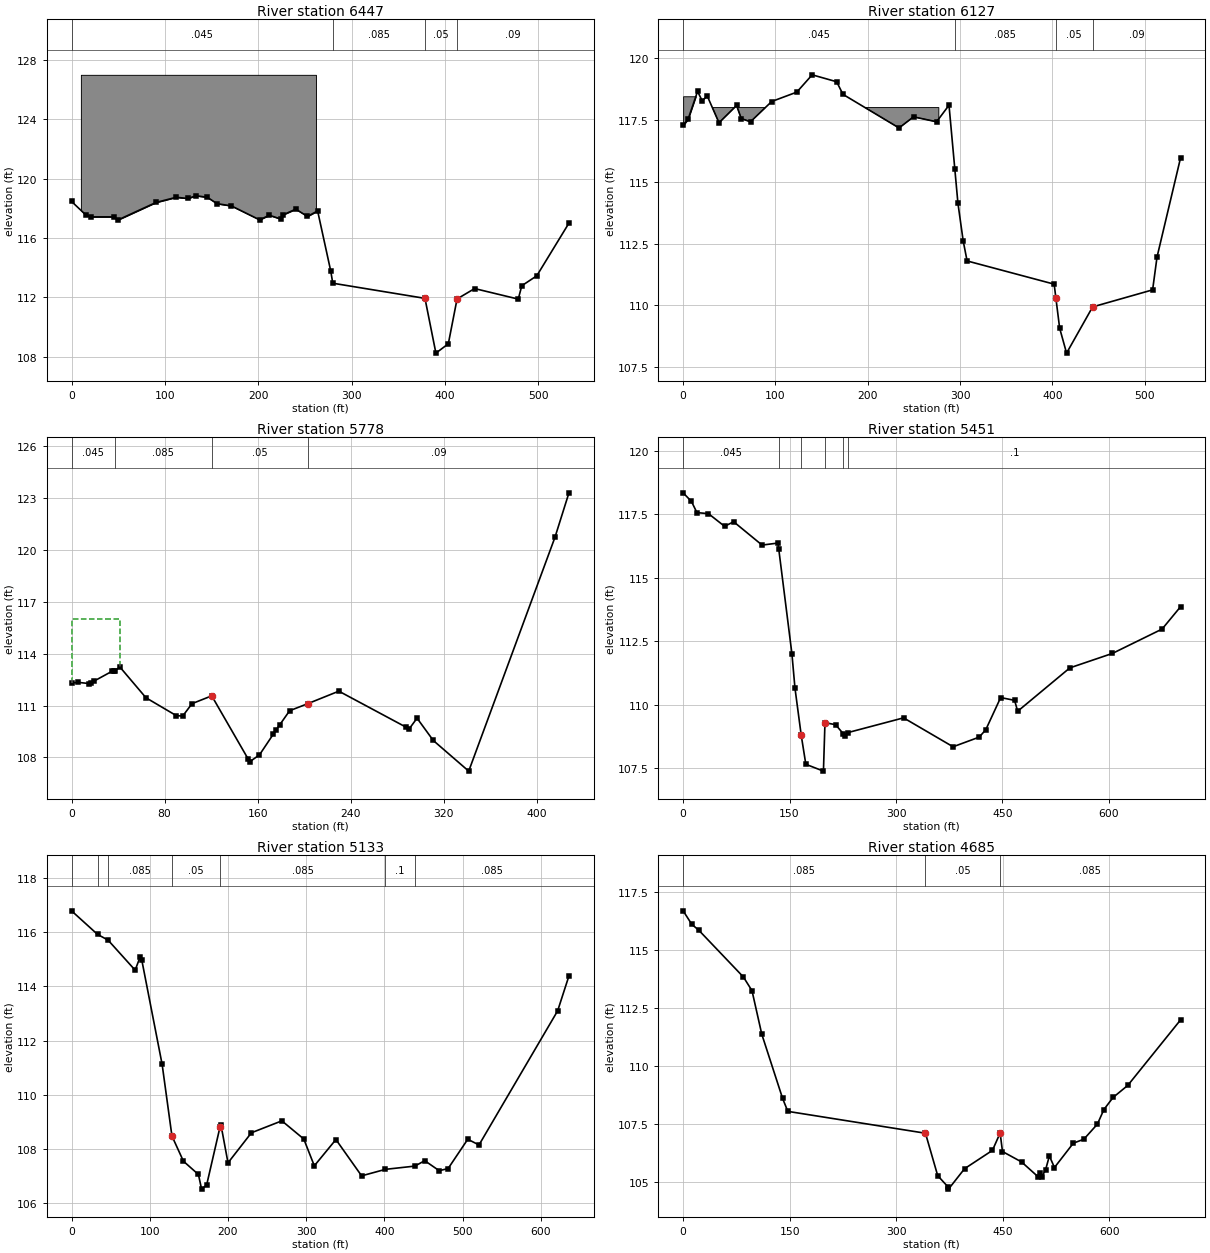
Type RM Length L Ch R = 1 ,6447    ,316.68,320.07,323.45
XS GIS Cut Line= 2
 2296263.9188651  719049.2802428 2295735.1229247  719113.1004425
#Sta/Elev= 30
       0  118.47    15.1  117.57   21.05  117.43   45.26  117.43   49.62  117.22
   90.47   118.4  112.16  118.75   124.3  118.67  133.66  118.85   145.4  118.75
  155.77  118.32   171.1  118.17  201.43  117.23  211.71  117.54  224.26  117.28
   226.6  117.57  240.14  117.95  252.61  117.46  263.51  117.83  277.52  113.79
  279.74  112.96  378.46  111.94  390.16  108.25  403.46  108.88  412.82   111.9
  431.61   112.6  478.35  111.89  482.12  112.79  498.19  113.46  532.63  117.01
#Mann= 4 ,-1 , 0
       0    .045       0  279.74    .085       0  378.46     .05       0
  412.82     .09       0
#Block Obstruct= 1 ,-1
   10.01  261.71     127
Bank Sta=378.46,412.82
XS Rating Curve= 0 ,0
Exp/Cntr=0.3,0.1

Type RM Length L Ch R = 1 ,6127    ,341.56,349.16,356.77
XS GIS Cut Line= 2
 2296293.8752854  718805.7215214 2295755.9621735  718775.7651012
#Sta/Elev= 30
       0  117.28    5.34  117.53   15.64  118.66   20.61  118.28   26.18  118.47
   38.87  117.39    57.9  118.09   62.95  117.56   72.98  117.43    95.9  118.25
  123.09  118.63  139.77  119.33  166.29  119.05  173.11  118.54  233.87  117.18
  249.52  117.63   274.5  117.43  287.97   118.1  294.21  115.54  297.65  114.13
  303.33  112.61  307.57   111.8  401.86  110.86  403.66  110.32  407.81  109.08
   415.3  108.07  443.51  109.94   508.5  110.63  513.29  111.96  538.75  115.97
#Mann= 4 ,-1 , 0
       0    .045       0  294.21    .085       0  403.66     .05       0
  443.51     .09       0
#Block Obstruct= 2 ,-1
   31.42  276.94118.0046       0   18.19118.4629
Bank Sta=403.66,443.51
XS Rating Curve= 0 ,0
Exp/Cntr=0.3,0.1

Type RM Length L Ch R = 1 ,5778    ,317.35,326.68,334.66
XS GIS Cut Line= 2
 2296188.4634181  718551.5695152 2295799.4641056  718373.7412581
#Sta/Elev= 30
       0   112.3    5.49  112.34   15.14  112.27   16.59  112.28   19.56  112.42
   34.57  112.97   36.88  112.98   37.38  113.01   41.52  113.23   63.99  111.45
   90.02  110.42   95.55  110.39  103.63  111.11  120.55  111.56  152.05  107.89
  153.18  107.75  161.61  108.15  173.65  109.36  176.12  109.61  178.96  109.88
  187.54   110.7  203.21  111.11  229.85  111.83  287.36  109.76  290.55  109.67
  297.09  110.27  311.07  108.98  341.53  107.21  415.69  120.72  427.72  123.29
#Mann= 4 ,-1 , 0
       0    .045       0   37.38    .085       0  120.55     .05       0
  203.21     .09       0
#XS Ineff= 1 ,-1
       0   41.52     116
Permanent Ineff=
       T
Bank Sta=120.55,203.21
XS Rating Curve= 0 ,0
Exp/Cntr=0.3,0.1

Type RM Length L Ch R = 1 ,5451    ,322.99,318.33,315.2
BEGIN DESCRIPTION:
Surveyed Section
END DESCRIPTION:
XS GIS Cut Line= 6
 2296390.8520603  718368.8622814     2296280.506      718300.788
    2296270.6717     718293.2695    2296244.9644     718262.9883
    2296198.9221     718216.8623 2295818.8724985  717968.6212531
#Sta/Elev= 30
       0  118.35   11.74  118.01   19.45  117.57   35.64  117.53   58.43  117.03
   71.22  117.21  111.26  116.29  133.57  116.37  134.69  116.15  153.29  112.01
  157.62  110.65  166.45  108.79  172.91  107.65  197.74  107.38  199.89  109.29
  214.93  109.21  225.46  108.86  228.73  108.75  232.32   108.9  310.67  109.48
  380.44  108.34   417.2  108.72  426.49  109.01  447.48  110.28  467.14  110.17
  471.46  109.74     545  111.45     605  112.02     675  112.98     701  113.86
#Mann= 6 ,-1 , 0
       0    .045       0  134.69    .085       0  166.45     .05       0
  199.89     .09       0  225.46    .085       0  232.32      .1       0
Bank Sta=166.45,199.89
XS Rating Curve= 0 ,0
Exp/Cntr=0.3,0.1

Type RM Length L Ch R = 1 ,5133    ,431.51,447.7,463.77
XS GIS Cut Line= 2
 2296589.8447482  718145.4123916  2296084.025346  717759.6556167
#Sta/Elev= 30
       0  116.79   33.27  115.92   46.69  115.71   81.34   114.6   87.88   115.1
   89.86  114.97  115.88  111.12   128.4  108.48   143.1  107.55  162.28  107.06
  166.31  106.52  172.77  106.67  189.93  108.82  191.23  108.87   200.1  107.49
  230.05   108.6  268.97  109.04     297  108.37  310.48  107.38   338.1  108.35
  370.97  107.01   401.4  107.25  439.12  107.37  451.69  107.57  470.22   107.2
  481.59  107.28  506.72  108.36  521.08  108.15  621.68   113.1  636.13  114.39
#Mann= 7 ,-1 , 0
       0    .045       0   33.27    .085       0   46.69    .085       0
   128.4     .05       0  189.93    .085       0   401.4      .1       0
  439.12    .085       0
Bank Sta=128.4,189.93
XS Rating Curve= 0 ,0
Exp/Cntr=0.3,0.1

Type RM Length L Ch R = 1 ,4685    ,540.17,532.55,526.51
XS GIS Cut Line= 3
 2296863.3207327  717896.3936089 2296350.8311845  717537.3174179
  2296290.030009  717494.7170281
#Sta/Elev= 30
       0   116.7   12.17  116.12   22.18  115.86    84.8  113.85   96.91  113.26
  110.63  111.39  139.96  108.62   147.3  108.06  341.03 107.118  358.27  105.29
  372.96   104.8  373.43  104.71  396.05  105.59   435.3  106.38  446.12  107.13
  449.42  106.33  476.33  105.88  499.61  105.24  502.26   105.4  504.84  105.24
  510.12  105.55  515.43  106.14  522.55  105.64  549.12  106.69  563.92  106.86
     583  107.51  592.14  108.14  605.08  108.66  625.76  109.18     700     112
#Mann= 3 ,-1 , 0
       0    .085       0  341.03     .05       0  446.12    .085       0
Bank Sta=341.03,446.12
XS Rating Curve= 0 ,0
Exp/Cntr=0.3,0.1

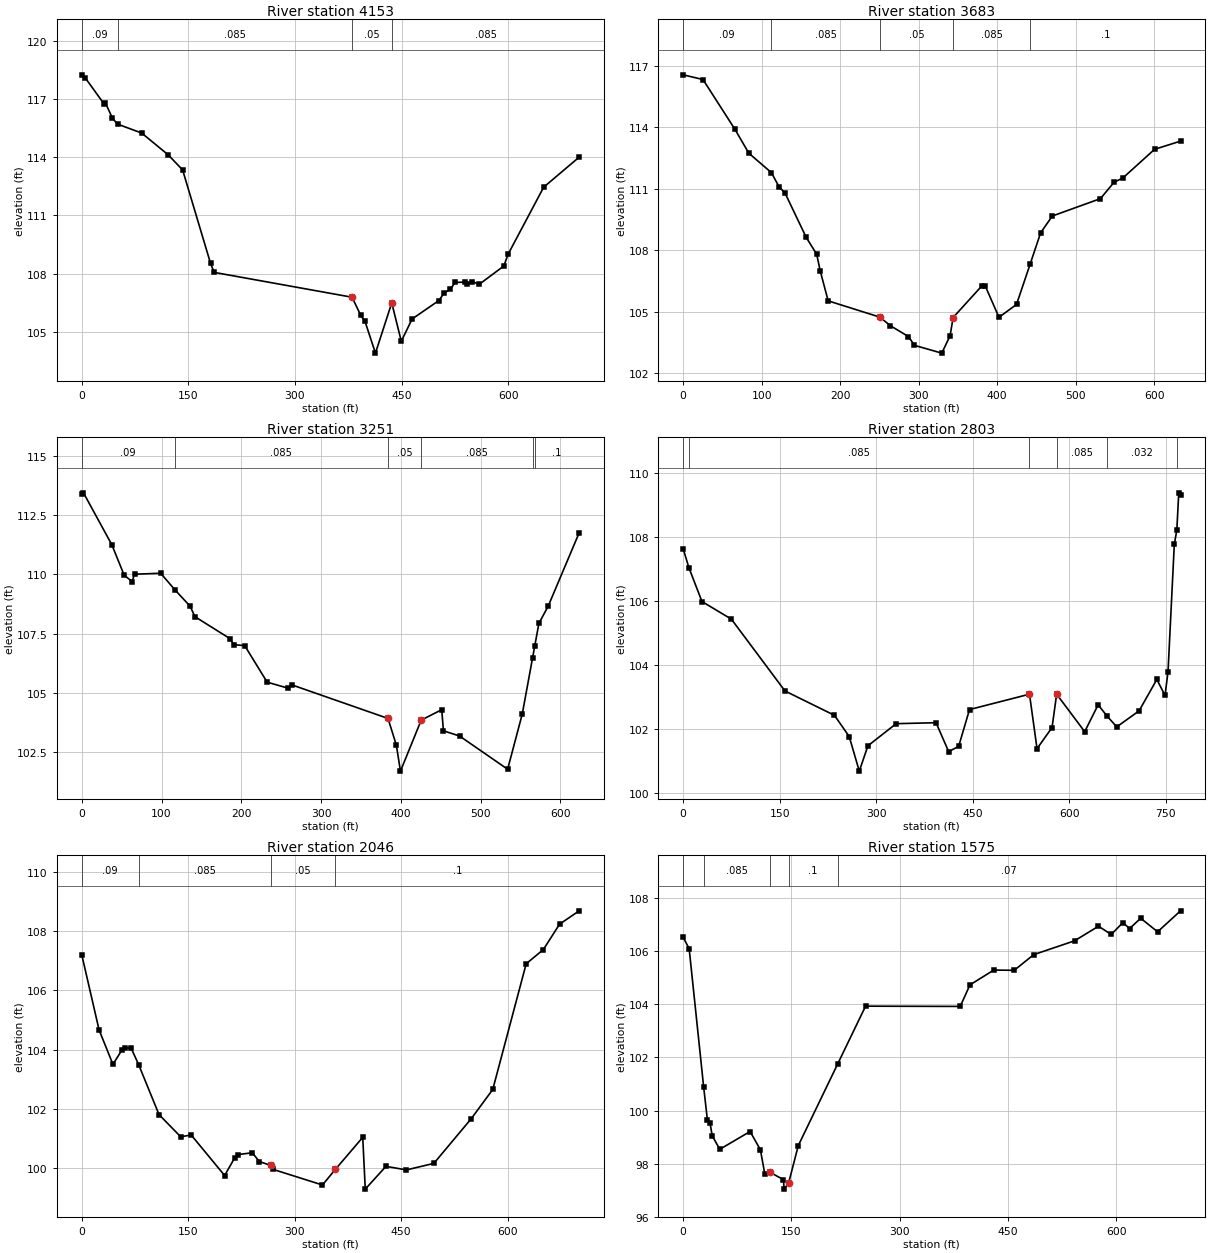
Type RM Length L Ch R = 1 ,4153    ,470.28,469.1,469.4
XS GIS Cut Line= 3
 2297085.7824527  717463.6575961 2296553.4883353  717200.1456568
 2296458.4468886  717153.0954356
#Sta/Elev= 30
       0  118.24    5.13  118.07   31.15  116.75   33.28  116.79   43.22     116
   50.31   115.7   84.31  115.24  121.49  114.12  141.91  113.34  181.23  108.52
  186.31  108.06   380.4  106.78  392.66  105.84   398.6  105.53  413.25   103.9
   436.2  106.49  449.62  104.51  464.88  105.66  502.13   106.6  510.17     107
  518.66  107.19  525.31  107.54  538.76  107.56     542  107.47  548.77  107.59
  559.48  107.45  593.95  108.39     600     109     650  112.45     700     114
#Mann= 4 ,-1 , 0
       0     .09       0   50.31    .085       0   380.4     .05       0
   436.2    .085       0
Bank Sta=380.4,436.2
XS Rating Curve= 0 ,0
Exp/Cntr=0.3,0.1

Type RM Length L Ch R = 1 ,3683    ,416.64,432.38,450.04
XS GIS Cut Line= 2
 2297235.9842581  717042.0384932 2296640.4472753   716825.958703
#Sta/Elev= 30
       0  116.57   25.31  116.34    66.1   113.9   83.67  112.74  112.45  111.79
  121.98  111.11  129.81  110.79  156.71  108.63  170.12   107.8   174.6  106.99
  184.71 105.525   250.5  104.73  263.98  104.31  286.95  103.78  294.65  103.35
  329.44  102.97  340.02  103.82  343.88  104.71  380.57  106.26  384.83  106.25
  402.26  104.72  424.62  105.35  441.88  107.31  455.34  108.85  470.21  109.67
  531.52  110.52  548.84  111.32  560.09  111.53  600.46  112.93  633.53  113.33
#Mann= 5 ,-1 , 0
       0     .09       0  112.45    .085       0   250.5     .05       0
  343.88    .085       0  441.88      .1       0
Bank Sta=250.5,343.88
XS Rating Curve= 0 ,0
Exp/Cntr=0.3,0.1

Type RM Length L Ch R = 1 ,3251    ,461.43,448,430.22
XS GIS Cut Line= 2
  2297375.772615  716709.7401584 2296795.0977379  716482.7273464
#Sta/Elev= 30
       0   113.4    2.12  113.44   37.69  111.25    53.1  109.97   63.04   109.7
   66.09  110.01   98.86  110.05  116.53  109.36  135.75  108.66  141.82  108.22
  185.45   107.3  190.57  107.04  204.19     107  232.34  105.46  258.17  105.21
  263.75  105.34  383.85  103.93  394.23  102.81  399.45  101.71  425.44  103.86
  451.15   104.3  453.29  103.41  473.48  103.19  533.76  101.79  552.12  104.12
  564.99  106.48  567.73  106.98  572.97  107.94  584.56  108.66  623.47  111.76
#Mann= 6 ,-1 , 0
       0     .09       0  116.53    .085       0  383.85     .05       0
  425.44    .085       0  564.99    .032       0  567.73      .1       0
Bank Sta=383.85,425.44
XS Rating Curve= 0 ,0
Exp/Cntr=0.3,0.1

Type RM Length L Ch R = 1 ,2803    ,741.71,756.85,771.99
XS GIS Cut Line= 2
 2297569.3309074  716443.2988053 2296810.6301934  716237.7924702
#Sta/Elev= 30
       0  107.63    9.04  107.03   29.26  105.98   75.01  105.43  158.34  103.19
  235.25  102.43  258.15  101.77  273.85  100.69  287.27  101.48  331.18  102.17
  393.18   102.2  412.76   101.3   428.3  101.46  445.19  102.61  538.45  103.09
  550.15  101.39  573.51  102.05  580.66  103.09  624.26  101.92  645.15  102.76
  658.86  102.41  674.11  102.07  708.81  102.57  736.43  103.55  749.09  103.05
   753.8  103.79  763.55  107.76  767.49  108.21  770.47  109.37  773.26  109.29
#Mann= 6 ,-1 , 0
       0     .09       0    9.04    .085       0  538.45     .05       0
  580.66    .085       0  658.86    .032       0  767.49      .1       0
Bank Sta=538.45,580.66
XS Rating Curve= 0 ,0
Exp/Cntr=0.3,0.1

Type RM Length L Ch R = 1 ,2046    ,475.27,471.64,463.39
XS GIS Cut Line= 2
 2297789.1748939  716213.8963847 2297227.6168851  715794.5200845
#Sta/Elev= 30
       0   107.2    24.4  104.66   43.88   103.5   56.75  103.99   61.56  104.06
   69.69  104.04   80.11  103.49  108.82   101.8  139.38  101.05  154.18  101.11
  201.28   99.74  215.49  100.34   220.7  100.45  240.29  100.51  250.21  100.21
  266.75  100.08  269.21   99.95  339.08   99.42  357.36   99.95  395.85  101.03
  399.45   99.28  428.55  100.05  457.39   99.93  496.07  100.15   548.7  101.66
  579.08  102.65  626.16   106.9  650.34  107.38  673.25  108.24  700.87  108.69
#Mann= 4 ,-1 , 0
       0     .09       0   80.11    .085       0  266.75     .05       0
  357.36      .1       0
Bank Sta=266.75,357.36
XS Rating Curve= 0 ,0
Exp/Cntr=0.3,0.1

Type RM Length L Ch R = 1 ,1575    ,282.65,298.23,317.73
XS GIS Cut Line= 2
  2297968.395535  715839.9226469 2297365.0193766  715506.5722545
#Sta/Elev= 30
       0  106.53    8.38  106.09   28.47  100.88   33.62   99.65   37.36   99.52
   40.27   99.05   50.83   98.54   92.81   99.21   107.1   98.52  113.18   97.61
  119.81   97.68     139    97.4  139.98   97.04   146.2   97.27   159.6   98.68
  214.12  101.75  252.84  103.93     384  103.92  397.46  104.73  430.54  105.29
  458.86  105.28  485.84  105.87  542.39  106.39  575.62  106.94  593.31  106.63
  609.56  107.08  618.63  106.85  634.11  107.24  657.55  106.73  689.34  107.52
#Mann= 5 ,-1 , 0
       0     .09       0   28.47    .085       0  119.81     .05       0
   146.2      .1       0  214.12     .07       0
Bank Sta=119.81,146.2
XS Rating Curve= 0 ,0
Exp/Cntr=0.5,0.3