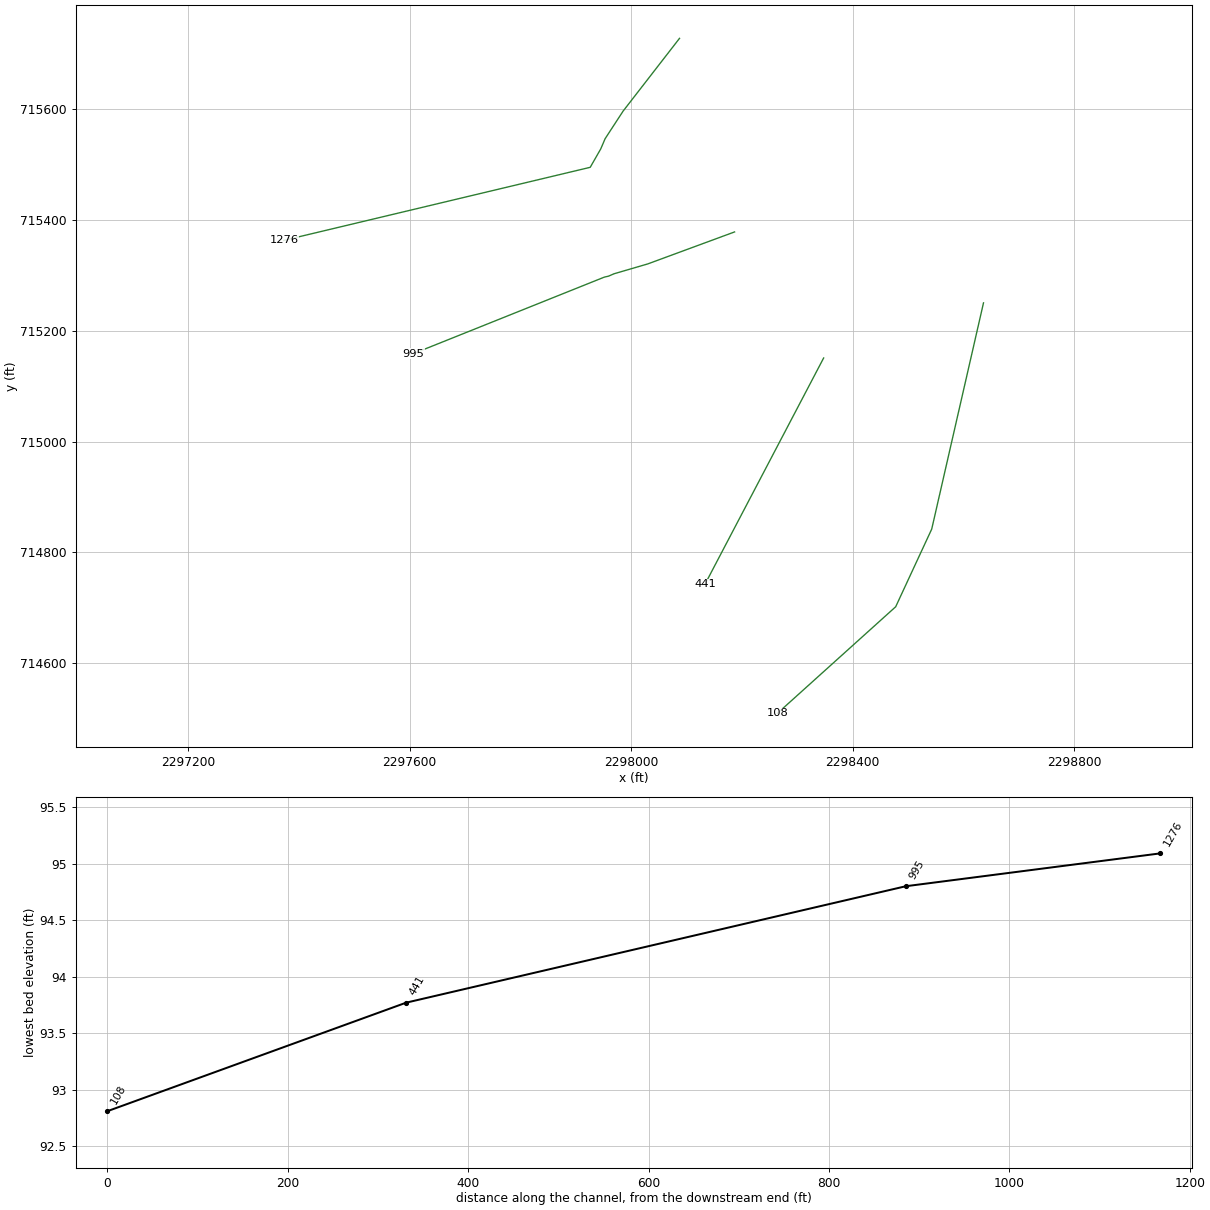
HEC-RAS study dtl_shepard_bch.prj: dtl_shepard_bch

--- dtl_shepard_bch.g02 (geometry) --- (continued)

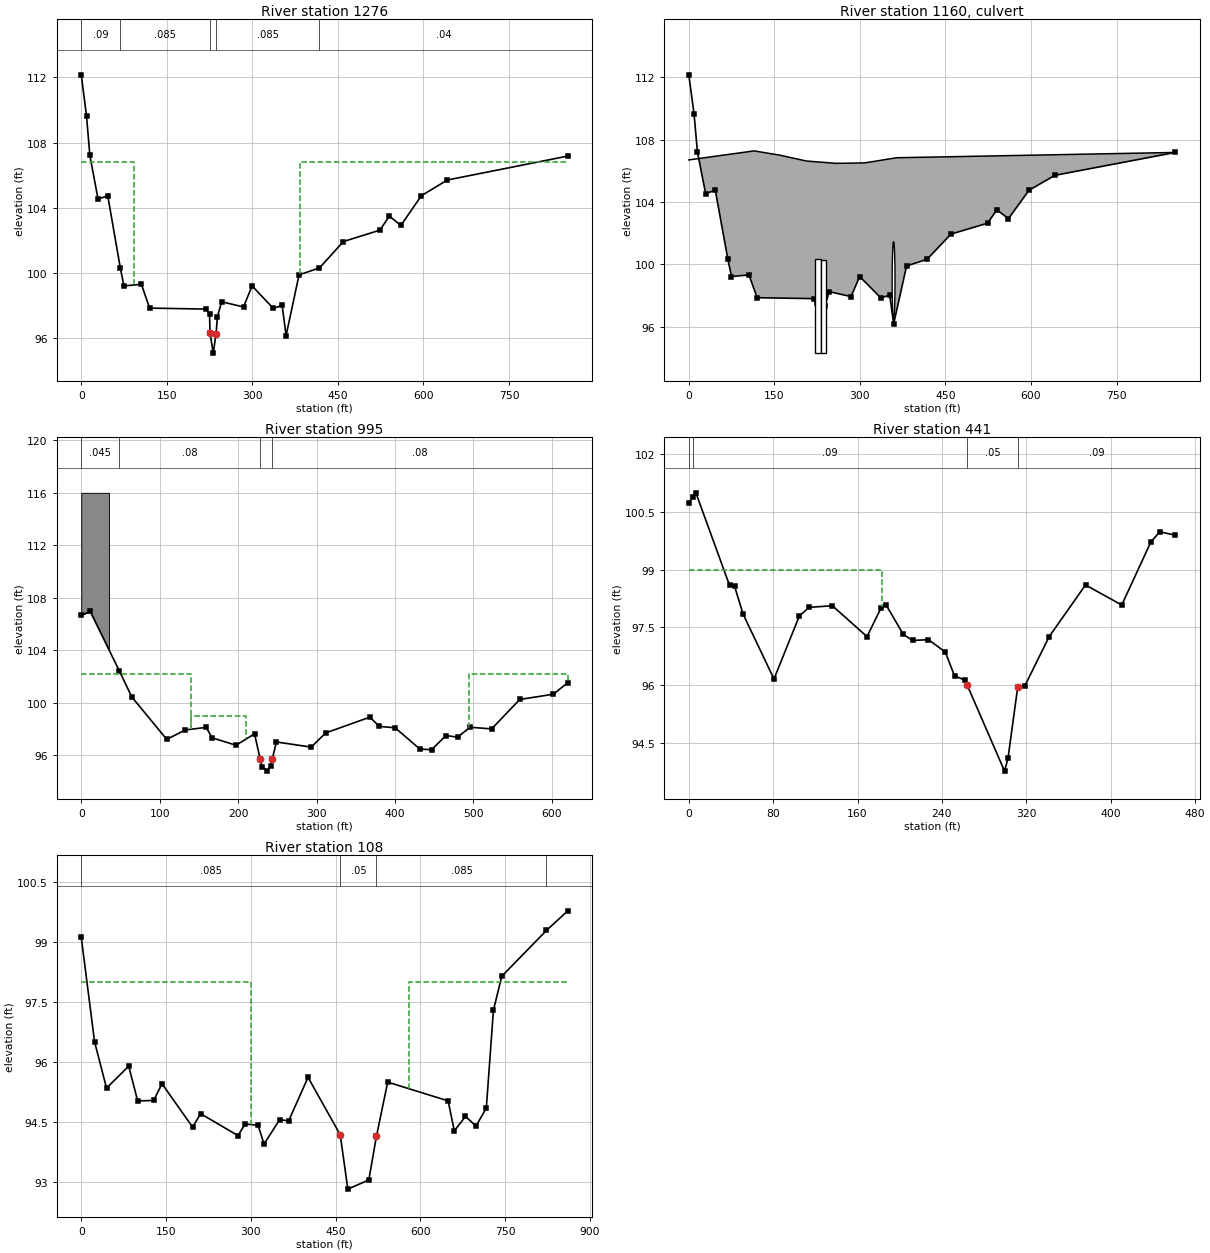
Type RM Length L Ch R = 1 ,1276    ,295.53,281.69,263.69
BEGIN DESCRIPTION:
Surveyed Section
END DESCRIPTION:
XS GIS Cut Line= 6
  2298087.262202  715728.1700717    2297985.4067     715596.7667
    2297952.9559     715546.9402    2297945.1131     715528.6036
    2297926.0809     715495.3326 2297373.1235478  715363.4376111
#Sta/Elev= 30
       0  112.15    9.25  109.63   15.11  107.21   29.47  104.53   46.47  104.74
    68.4  100.33   74.85   99.21  105.44   99.31  119.85   97.85  219.05   97.79
 224.875   97.48 225.791   96.33 231.362   95.09   236.4   96.28 238.711   97.32
  246.15   98.24 284.483   97.92  299.51   99.21  336.84   97.83  352.16   98.02
  359.13   96.17  381.83   99.89  417.59  100.31  459.58  101.93  523.76  102.63
  540.05  103.49  560.34  102.92   596.3  104.74   641.6   105.7  852.93  107.17
#Mann= 5 ,-1 , 0
       0     .09       0    68.4    .085       0 225.791     .05       0
   236.4    .085       0  417.59     .04       0
#XS Ineff= 2 , 0
       0      92  106.83     384       0  106.83
Permanent Ineff=
       F       F
Bank Sta=225.791,236.4
XS Rating Curve= 0 ,0
Exp/Cntr=0.5,0.3

Type RM Length L Ch R = 2 ,1160    ,,,
BEGIN DESCRIPTION:
STR 58/STR 58A
END DESCRIPTION:
Bridge Culvert--1,0,-1,-1, 0
Deck Dist Width WeirC Skew NumUp NumDn MinLoCord MaxHiCord MaxSubmerge Is_Ogee
60,112,2.6,0, 9, 9, , , 0.98, 0, 1,1,,
       0  114.53  160.31  206.08  258.33  308.48  364.23  365.23  852.93
  106.69  107.27  106.99  106.62  106.47   106.5  106.83  106.83  107.17
                                                                        
       0  114.53  160.31  206.08  258.33  308.48  364.23  365.23  852.93
  106.69  107.27  106.99  106.62  106.47   106.5  106.83  106.83  107.17
                                                                        
BR Coef=-1 , 0 , 0 ,, 0 ,,,0.8,-1,,0,
WSPro=,,,, 1 ,,,, 0 ,,,, 0 ,,,,-1 ,-1 ,-1 , 0 , 0 , 0 , 0 , 0
Culvert=2,6,10,123,0.013,0.4,1,8,1,94.3294,225.9,93.793,229.9,Culvert #1  , 0 ,50
Culvert Bottom n=0.013
Culvert=2,6,10,123,0.013,0.4,1,8,1,94.2942,236,94.0817,240,Culvert #2  , 0 ,50
Culvert Bottom n=0.013
Culvert=1,5,,122.5,0.013,0.5,1,1,1,96.4526,359,96.404,438,Culvert #3  , 0 ,12
Culvert Bottom n=0.013
BC Design=,, 0 ,, 0 ,,,,,,
BC Use User HTab Curves=0
BC User HTab FreeFlow(D)= 0

Type RM Length L Ch R = 1 ,995     ,554,554,554
BEGIN DESCRIPTION:
Surveyed Section
END DESCRIPTION:
XS GIS Cut Line= 6
 2298186.6061812  715378.6848473    2298029.9472     715320.9413
    2297969.0378     715303.1412    2297958.9548     715298.7957
    2297951.6204     715297.1364 2297606.9396673  715158.9471335
#Sta/Elev= 30
       0  106.69   11.47  106.96   48.76  102.41   64.45  100.45     109   97.22
  132.85   97.94  159.26   98.13 166.875   97.34 197.316   96.77 220.923   97.64
  228.13   95.72 230.308   95.14 237.229    94.8 241.328   95.17  243.56   95.72
 248.844   97.02 293.207   96.63  311.66   97.71  367.94   98.91  380.04   98.21
  400.27    98.1  431.78   96.48  446.61   96.43  465.06   97.51  479.78   97.39
  495.82   98.14  523.27   98.02  559.15  100.26  602.01  100.66  620.32  101.54
#Mann= 4 ,-1 , 0
       0    .045       0   48.76     .08       0  228.13     .05       0
  243.56     .08       0
#XS Ineff= 3 ,-1
       0   139.9  102.18   139.9     210      99  494.72  620.32  102.18
Permanent Ineff=
       F       F       F
#Block Obstruct= 1 ,-1
       0   35.33     116
Bank Sta=228.13,243.56
XS Rating Curve= 0 ,0
Exp/Cntr=0.5,0.3

Type RM Length L Ch R = 1 ,441     ,331.25,331.25,333.57
XS GIS Cut Line= 2
 2298347.3490655  715151.1023433 2298133.1613569  714742.5853892
#Sta/Elev= 30
       0  100.73     3.9  100.88    6.72  100.99   38.61   98.59   43.48   98.56
   51.37   97.85   80.78   96.16  104.86    97.8  114.21   98.02  136.11   98.06
  168.94   97.26  182.38   98.01  187.09   98.08   203.3   97.32  212.16   97.16
  227.24   97.18  243.19   96.86  251.91   96.24  261.92   96.13  263.97      96
  299.35   93.77  302.61    94.1  311.82   95.95  318.55   95.98  341.66   97.26
  376.11    98.6  410.46   98.08  437.97   99.71  446.52   99.98  461.26   99.89
#Mann= 4 ,-1 , 0
       0    .045       0     3.9     .09       0  263.97     .05       0
  311.82     .09       0
#XS Ineff= 2 , 0
       0  183.43      99               0
Permanent Ineff=
       F       F
Bank Sta=263.97,311.82
XS Rating Curve= 0 ,0
Exp/Cntr=0.3,0.1

Type RM Length L Ch R = 1 ,108     ,100.47,100.47,116.37
XS GIS Cut Line= 4
 2298635.8829297  715250.6668457 2298542.4142131  714842.2491928
 2298477.3924972   714702.046118 2298263.8078403  714509.5715725
#Sta/Elev= 30
       0   99.12   23.58    96.5   44.76   95.34   84.01   95.89   99.83   95.02
   128.2   95.03  142.93   95.45   197.2   94.36  211.21    94.7  277.47   94.15
  289.89   94.44  313.03   94.41  323.49   93.94  351.11   94.55   367.1   94.52
  401.35   95.61  458.35   94.17  471.79   92.81  508.95   93.04  522.37   94.13
  542.36   95.49  649.32   95.02  660.21   94.27  680.01   94.63  698.66   94.39
   716.9   94.84  729.46   97.29  744.19   98.14  823.39   99.29  861.04   99.78
#Mann= 4 ,-1 , 0
       0    .085       0  458.35     .05       0  522.37    .085       0
  823.39     .09       0
#XS Ineff= 2 , 0
       0     300      98     580       0      98
Permanent Ineff=
       F       F
Bank Sta=458.35,522.37
XS Rating Curve= 0 ,0
Exp/Cntr=0.3,0.1
Stream Node=Shepards_Branch ,1               , 0 , 0 ,Upstream end
Stream Node=Shepards_Branch ,1               , 0 , 1 ,Downstream end

Chan Stop Cuts=-1
Use User Specified Reach Order=0
User Specified Reach Order=Shepards_Branch ,1

--- dtl_shepard_bch.g01 (geometry) ---

Program Version=4.00

River Reach=Shepards_Branch ,1
Reach XY= 30
2295114.26426755724030.0545068092295149.74762073723673.801641077
2295640.83722846723336.000118986 2295896.4090987723306.696985051
2295933.26892909723095.2379581482295830.44940227722894.448882163
2296035.63253839722331.3979887372295895.75484616722152.100219533
2295942.80461545721942.2836811392295824.54438466721783.331758067
2295894.48323078721625.651450455 2295731.7164616721414.563296646
2295741.88938464721216.1912966972296011.47184609720692.285758331
2295966.96530764720434.147835329 2296124.6456154720387.098066136
2296203.48576915720275.1959123022296157.70761533720112.429143116
2296290.97178867719976.4415430432296263.62458083719443.170990273
2295976.47889851719301.8770831232295976.47889851718524.760593787
 2296749.0375199717765.8755763922296974.65198454717225.768221661
2297147.85096741716213.9215317372297412.20730986 716077.18549259
2297984.46803653715494.6473865962297938.64106064715158.775096104
2298180.20806322714894.4187536982298615.41734824714774.612769231

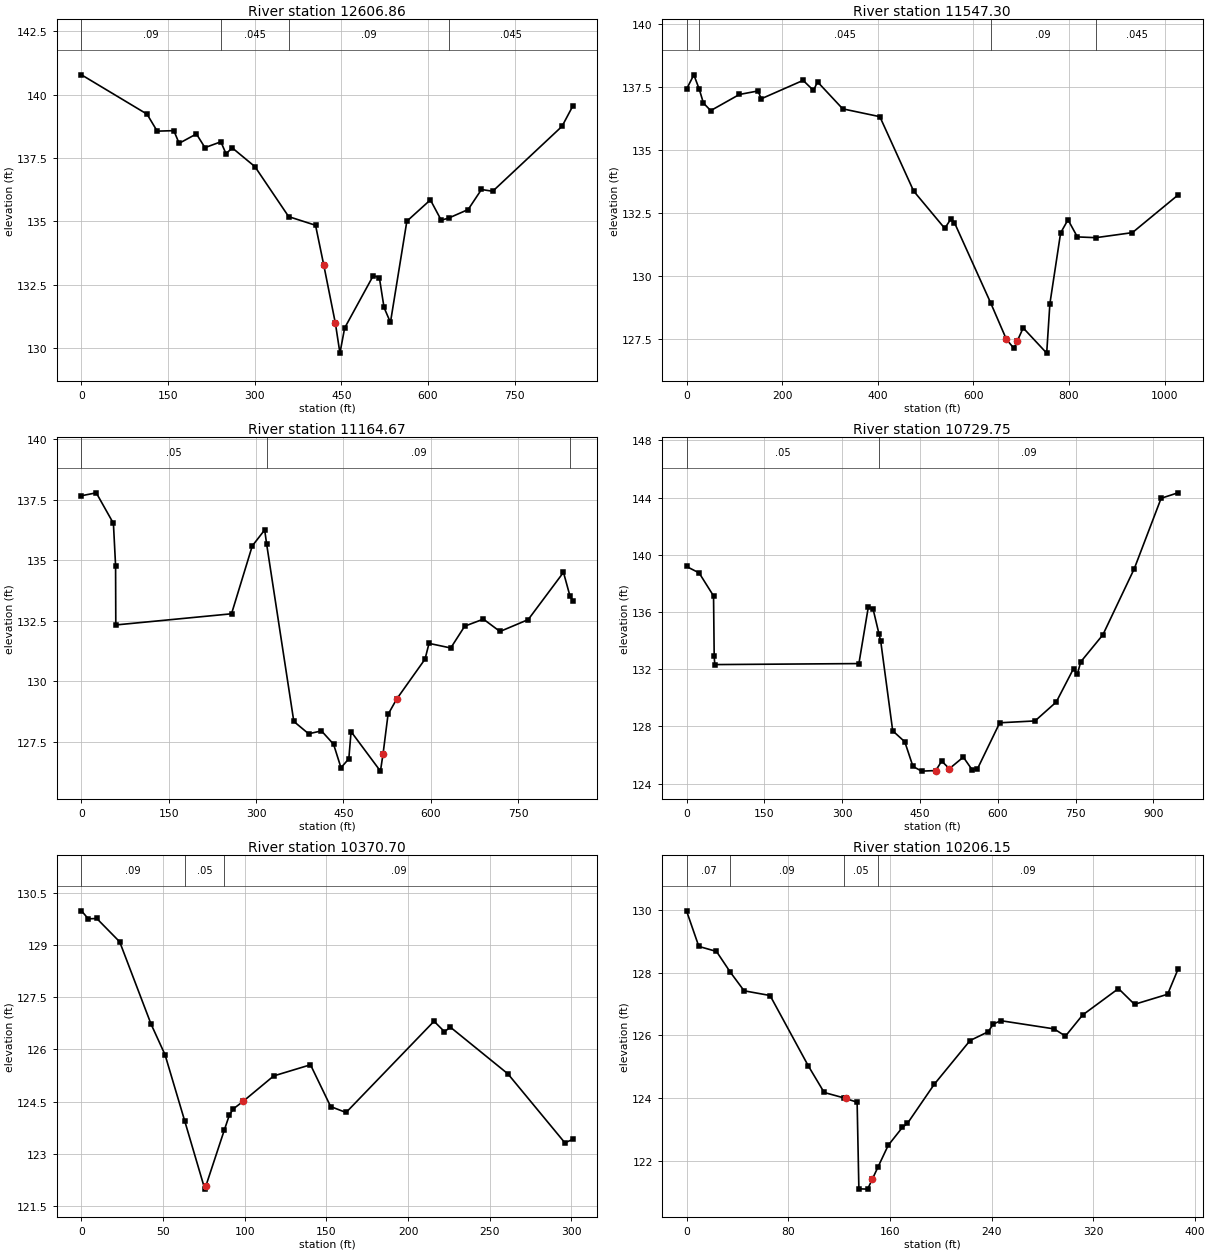
Type RM Length L Ch R = 1 ,12606.86,992.44,1059.56,1115.89
XS GIS Cut Line= 2
2295536.98043159724093.8048659712294701.00149198723933.666043118
#Sta/Elev= 30
       0  140.78  113.52  139.23  131.12  138.56  159.93  138.58  169.11  138.08
  199.05  138.45  213.86  137.91  241.39  138.14  250.32  137.67  261.14   137.9
  300.43  137.16  358.86  135.19  405.39  134.85  419.55  133.29   439.8  130.98
  447.63  129.81  455.79   130.8  505.27  132.86  515.91  132.79  524.01  131.61
  535.12  131.02  563.53  135.01  604.31  135.85  623.05  135.05  635.83135.1322
   669.7  135.47  692.75  136.26  712.22  136.19   832.3  138.75  851.18  139.56
#Mann= 4 ,-1 , 0
       0     .09       0  241.39    .045       0  358.86     .09       0
  635.83    .045       0
Bank Sta=419.55,439.8
XS Rating Curve= 0 ,0
Exp/Cntr=0.3,0.1

Type RM Length L Ch R = 1 ,11547.30,467.92,382.63,224.38
XS GIS Cut Line= 3
2296074.39546427723936.3802604382295688.97660246723208.970014259
2295515.26669292723100.401320785
#Sta/Elev= 30
       0  137.42   15.39  137.99   26.83  137.41   35.41  136.87   50.62  136.57
  110.57  137.21  149.45  137.35  156.41  137.04  243.96  137.77  265.62  137.37
  274.14  137.71  326.82  136.64  404.46  136.33  475.14  133.38   540.2   131.9
  552.73  132.26  560.42  132.13  636.37  128.94  669.16   127.5  684.93  127.14
  691.68  127.42  704.31  127.95   753.5  126.95  760.18  128.91  782.64  131.72
  798.08  132.24  817.66  131.56  856.37  131.53  932.77  131.73 1028.06  133.22
#Mann= 4 ,-1 , 0
       0     .09       0   26.83    .045       0  636.37     .09       0
  856.37    .045       0
Bank Sta=669.16,691.68
XS Rating Curve= 0 ,0
Exp/Cntr=0.3,0.1

Type RM Length L Ch R = 1 ,11164.67,392.74,434.92,406.87
XS GIS Cut Line= 2
2296459.81432602723094.9728861152295615.69273438723086.830234095
#Sta/Elev= 30
       0  137.66   25.36  137.78   54.84  136.52   58.56  134.78   58.94  132.33
  257.72  132.79  293.35  135.59  314.68  136.25  318.08  135.66  364.72  128.35
  390.19  127.84  412.21  127.96  433.01  127.41  445.74  126.44  459.21  126.81
  463.07  127.93  513.52   126.3  518.06  127.02  526.58  128.64  541.61  129.28
  590.12  130.92  596.97  131.57  634.29  131.38  658.29  132.28  690.39  132.57
  718.87  132.06  767.31  132.55  827.93   134.5   839.1  133.52  844.16  133.33
#Mann= 3 ,-1 , 0
       0     .05       0  318.08     .09       0   839.1    .045       0
Bank Sta=518.06,541.61
XS Rating Curve= 0 ,0
Exp/Cntr=0.3,0.1

Type RM Length L Ch R = 1 ,10729.75,362.23,359.05,318.24
XS GIS Cut Line= 2
2296400.10154463722720.4108936792295452.83969417722720.410893679
#Sta/Elev= 30
       0  139.18   24.31  138.73   52.13  137.12   53.37  132.91   54.47  132.32
   332.3  132.39  350.53  136.36  359.53  136.22  371.04  134.46  374.38  133.95
  397.46  127.69  420.77  126.92  436.48   125.2   453.1  124.87  480.45  124.91
  491.86  125.57  506.69  125.04  533.56  125.85  550.25  124.98  560.57  125.01
  603.75  128.25  671.78  128.38  712.66   129.7  746.05  132.04  753.31  131.64
  759.85  132.51  802.53   134.4  863.02  139.02  914.86  143.95  947.26  144.33
#Mann= 2 ,-1 , 0
       0     .05       0  371.04     .09       0
Bank Sta=480.45,506.69
XS Rating Curve= 0 ,0
Exp/Cntr=0.3,0.1

Type RM Length L Ch R = 1 ,10370.70,163.59,164.55,126.34
XS GIS Cut Line= 3
2296109.24045992722371.5025460272295815.44739972722428.308454931
2295813.67221509722428.308454931
#Sta/Elev= 23
       0  129.98    4.16  129.75    9.36  129.76    23.4  129.09   42.59  126.73
   51.16  125.85   63.21  123.95   75.53  121.99   76.25  122.09   87.44  123.68
   90.53  124.11    92.9  124.29      99  124.51  117.73  125.24  140.27  125.56
  152.62  124.36  162.06  124.19  215.94  126.81  222.33  126.51  225.95  126.64
  261.17   125.3  296.08  123.32  301.01  123.42
#Mann= 3 ,-1 , 0
       0     .09       0   63.21     .05       0   87.44     .09       0
Bank Sta=76.25,99
XS Rating Curve= 0 ,0
Exp/Cntr=0.3,0.1

Type RM Length L Ch R = 1 ,10206.15,103.27,240.21,207.02
XS GIS Cut Line= 2
2296139.41859907 722182.445380392295779.94370668722324.460152686
#Sta/Elev= 30
       0  129.96    9.69  128.83   23.58  128.67   34.48  128.01    45.3  127.42
   65.72  127.27   95.86  125.03  108.27  124.19  123.61  124.02  125.11     124
  134.19  123.88  135.57  121.13  142.44  121.12  146.18  121.44   150.7  121.83
  158.62  122.51  169.79  123.08   173.8  123.21  194.85  124.45  223.03  125.84
  237.34  126.12  241.12  126.36  247.23  126.47  289.09  126.21  298.06  125.98
  311.51  126.65  339.74  127.49  352.35  126.99   378.4  127.31  386.51   128.1
#Mann= 4 ,-1 , 0
       0     .07       0   34.48     .09       0  123.61     .05       0
   150.7     .09       0
Bank Sta=125.11,146.18
XS Rating Curve= 0 ,0
Exp/Cntr=0.3,0.1

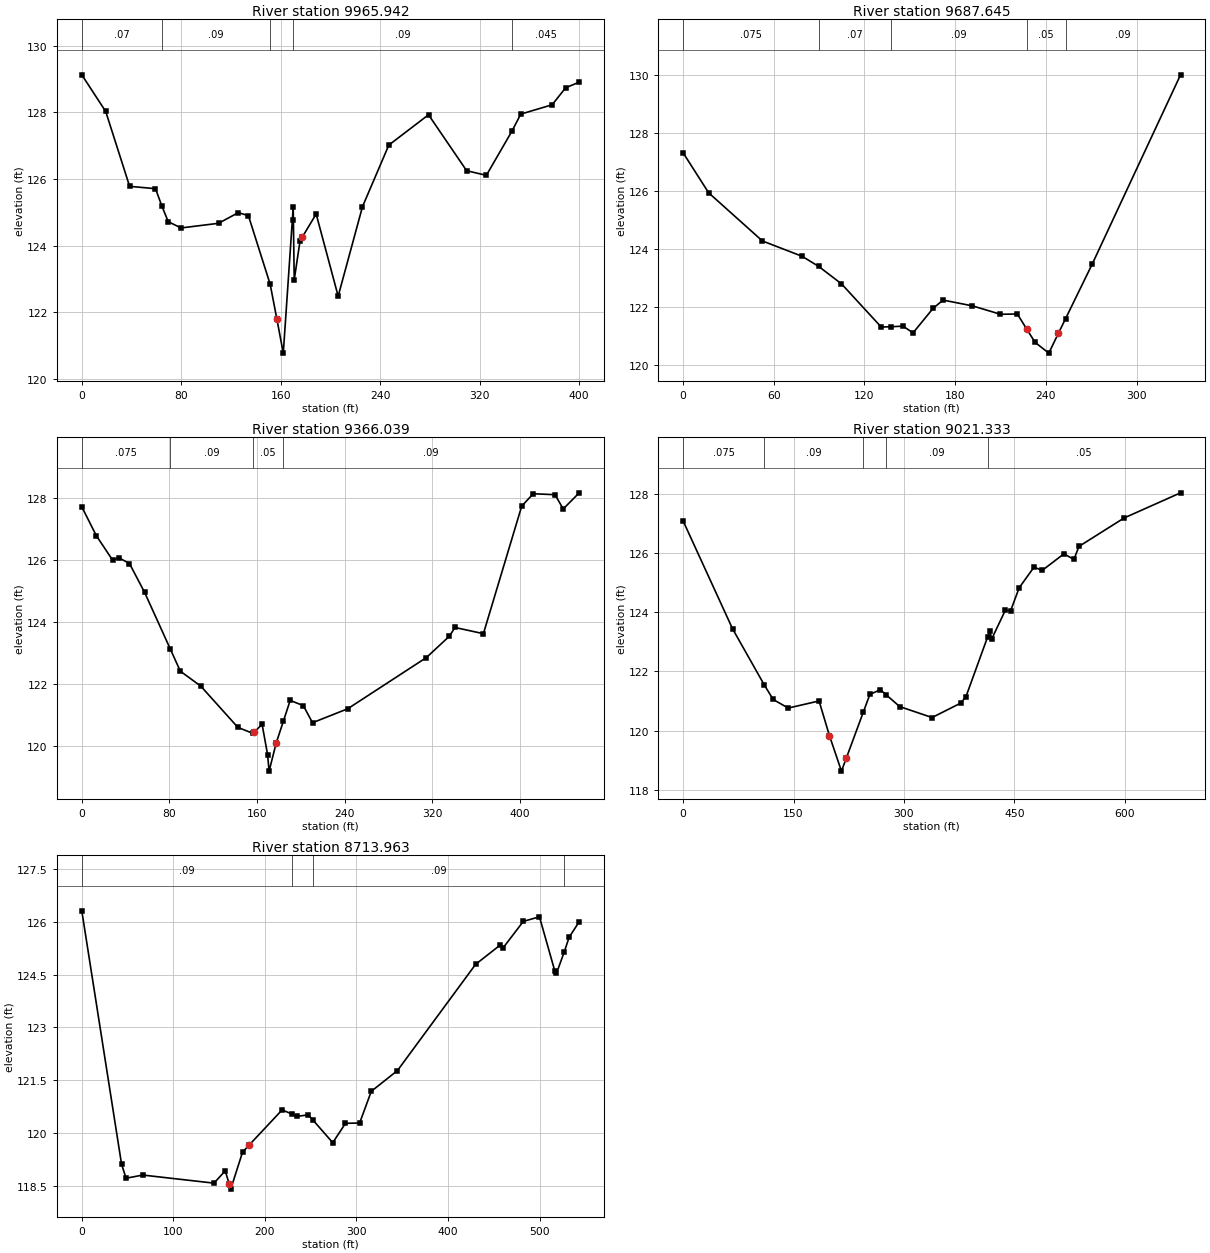
Type RM Length L Ch R = 1 ,9965.942,302.53,278.3,208.88
XS GIS Cut Line= 2
2296109.24045992722122.0891021342295712.48668982722069.721154839
#Sta/Elev= 30
       0  129.13   19.24  128.03   38.48  125.78    59.3  125.71   64.51  125.18
   69.54  124.72   79.82  124.53     110  124.67  125.92  124.99  134.05   124.9
  151.55  122.84  156.92   121.8  162.11  120.77  170.11  125.15  170.24  124.78
  170.91  122.97  175.62  124.15  177.49  124.26  188.56  124.95  206.27  122.48
  225.84  125.17  247.03  127.02  278.96  127.93  309.63  126.25  325.49  126.11
  346.25  127.45  353.17  127.95  378.39  128.23  389.26  128.74  400.19  128.91
#Mann= 5 ,-1 , 0
       0     .07       0   64.51     .09       0  151.55     .05       0
  170.24     .09       0  346.25    .045       0
Bank Sta=156.92,177.49
XS Rating Curve= 0 ,0
Exp/Cntr=0.3,0.1

Type RM Length L Ch R = 1 ,9687.645,245.55,321.61,215.23
XS GIS Cut Line= 2
2296101.00327839721779.3205804082295788.77188829721883.397710443
#Sta/Elev= 23
       0  127.33    16.9  125.95   52.43  124.29   78.74  123.76   89.72  123.41
  104.78  122.81  131.07  121.32  137.21  121.33  145.44  121.35  152.15  121.12
  165.48  121.97     172  122.25  191.46  122.05  209.99  121.76  221.12  121.77
  227.22  121.26  227.46  121.24  232.88  120.79  241.96  120.42  248.26   121.1
  253.06  121.61  270.75   123.5  329.12  130.02
#Mann= 5 ,-1 , 0
       0    .075       0   89.72     .07       0  137.21     .09       0
  227.22     .05       0  253.06     .09       0
Bank Sta=227.46,248.26
XS Rating Curve= 0 ,0
Exp/Cntr=0.3,0.1

Type RM Length L Ch R = 1 ,9366.039,259.67,344.7,322.02
XS GIS Cut Line= 2
2296032.75597999721530.2179412692295626.68455455721733.253653988
#Sta/Elev= 30
       0  127.72   13.25  126.79   28.15     126   33.76  126.08   43.54  125.89
   57.35  124.96   80.86  123.13   89.96  122.42   108.6  121.94  142.47  120.61
  155.95  120.42  157.49  120.46  164.57  120.71  169.59  119.73  170.96   119.2
  177.47  120.11  184.01  120.81   190.2  121.48  202.23  121.31  210.59  120.76
  242.73  121.21  314.51  122.86  335.55  123.55   340.6  123.83  366.56  123.63
  401.51  127.74  412.02  128.14  431.94  128.11   439.4  127.65     454  128.17
#Mann= 4 ,-1 , 0
       0    .075       0   80.86     .09       0  155.95     .05       0
  184.01     .09       0
Bank Sta=157.49,177.47
XS Rating Curve= 0 ,0
Exp/Cntr=0.3,0.1

Type RM Length L Ch R = 1 ,9021.333,209.95,307.37,346.9
XS GIS Cut Line= 2
2295959.39013426721308.4142215252295293.97897489721426.140811235
#Sta/Elev= 30
       0  127.08    67.1  123.44  110.28  121.54  122.33  121.05  142.76  120.76
  184.66     121  198.74  119.83  215.09  118.63  221.85  119.08  244.89  120.63
  253.68  121.22  267.89  121.38  276.18   121.2  294.23  120.81  338.16  120.44
  377.32  120.93  384.31  121.15  413.62  123.16  416.56  123.36  419.33   123.1
  437.83  124.07  444.82  124.04  456.47  124.82  476.66  125.52  487.85  125.41
  517.32  125.97  530.86  125.78  537.76  126.22  599.04  127.18  675.75  128.03
#Mann= 5 ,-1 , 0
       0    .075       0  110.28     .09       0  244.89     .05       0
  276.18     .09       0  413.62     .05       0
Bank Sta=198.74,221.85
XS Rating Curve= 0 ,0
Exp/Cntr=0.3,0.1

Type RM Length L Ch R = 1 ,8713.963,215.81,334.7,218.74
XS GIS Cut Line= 2
2295983.27668865721149.7392527462295495.30850516720910.873708382
#Sta/Elev= 30
       0  126.31   43.43  119.11   48.37  118.71   66.63   118.8  144.39  118.57
  156.67  118.92  161.09  118.54  162.68   118.4  175.57  119.45  182.71  119.65
  218.75  120.65  230.09  120.53  235.55  120.47   247.3  120.51  252.58  120.36
  274.11  119.72  288.02  120.27   303.5  120.28   316.2  121.18  344.79  121.77
  430.18  124.79  456.67  125.33  460.27  125.26  482.26  126.01  499.88  126.14
  516.66   124.6  518.42  124.53  526.94  125.14  532.33  125.56   543.3     126
#Mann= 4 ,-1 , 0
       0     .09       0  230.09     .05       0  252.58     .09       0
  526.94     .05       0
Bank Sta=161.09,182.71
XS Rating Curve= 0 ,0
Exp/Cntr=0.3,0.1