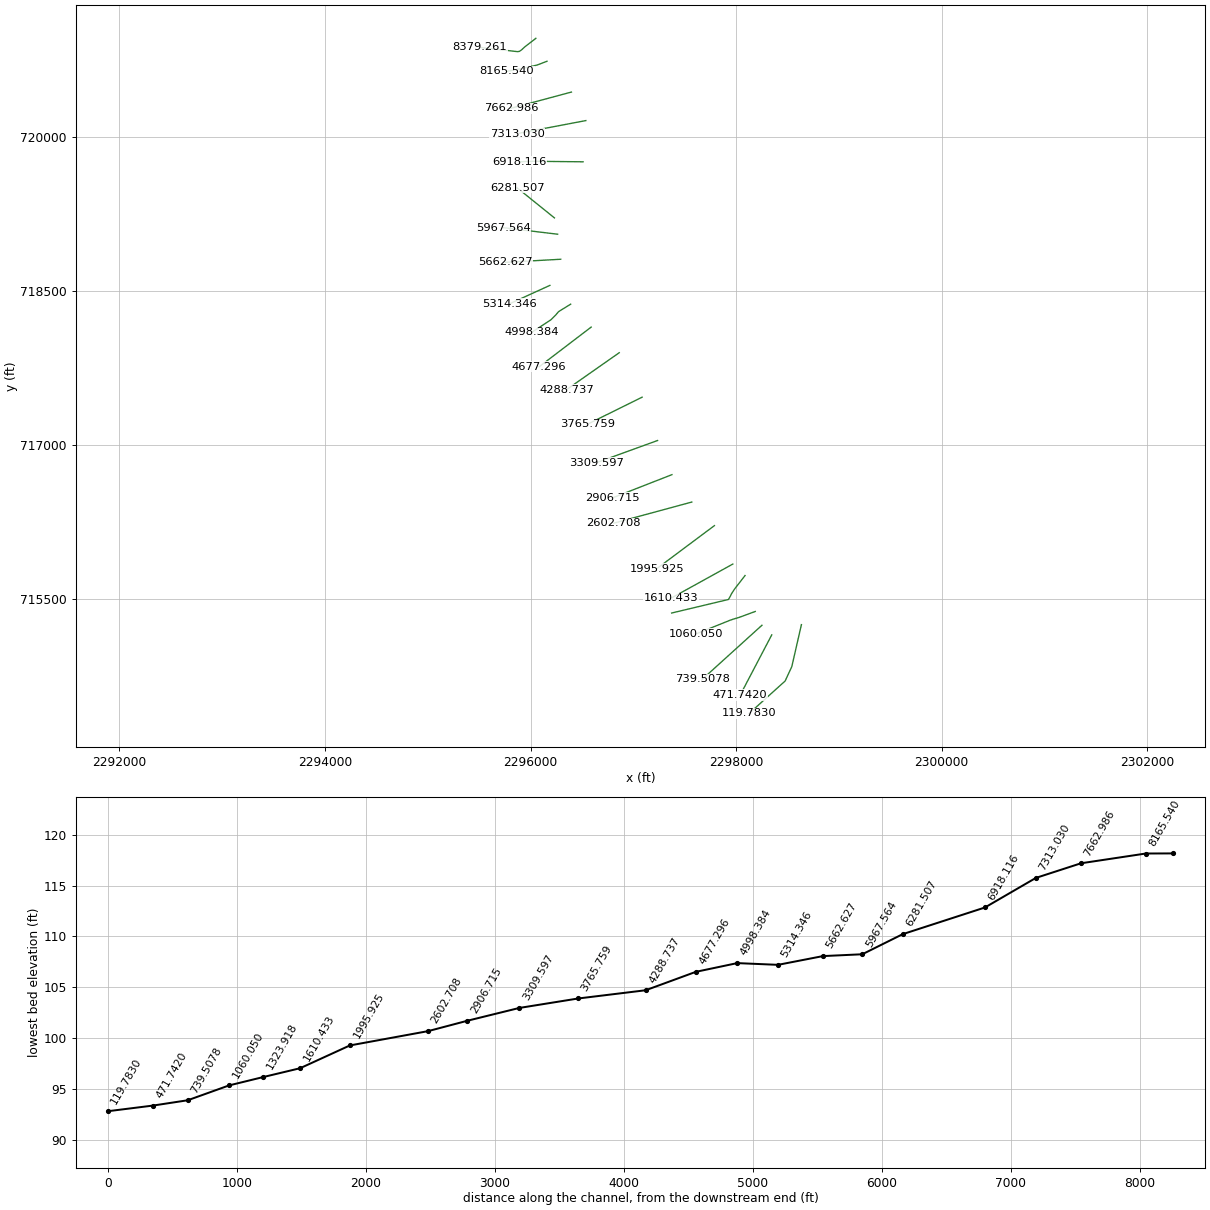
HEC-RAS study dtl_shepard_bch.prj: dtl_shepard_bch

--- dtl_shepard_bch.g01 (geometry) --- (continued)

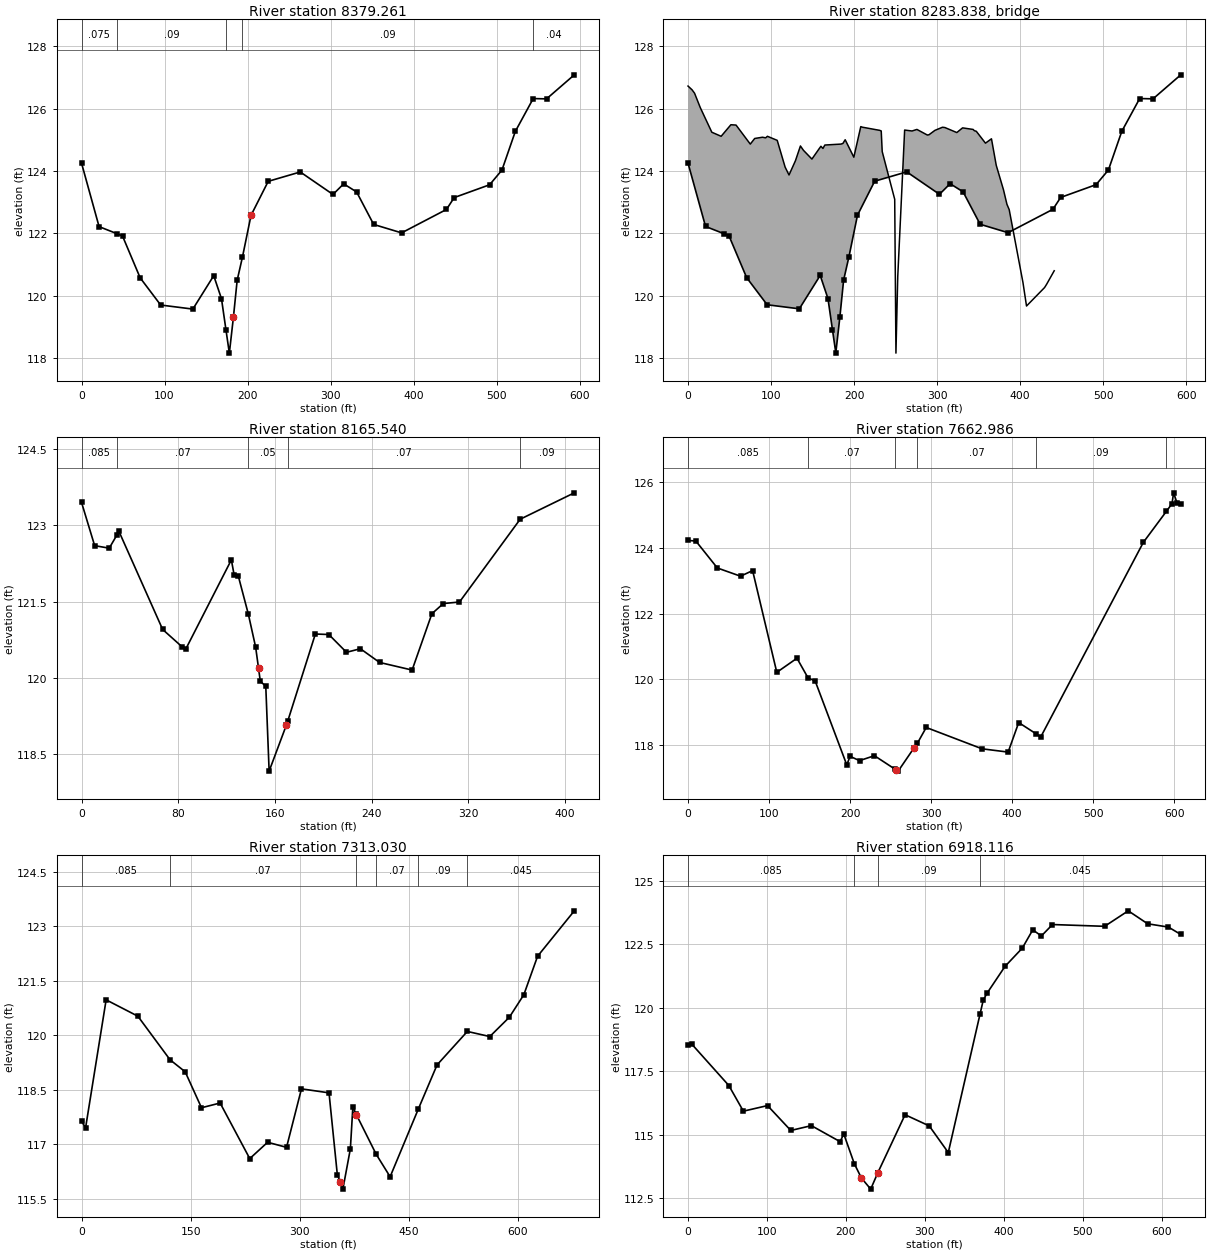
Type RM Length L Ch R = 1 ,8379.261,233.24,213.72,184.56
XS GIS Cut Line= 6
2296052.11226691720955.2676370892295945.86959998 720873.49150002
2295911.89830005 720842.273500012295891.25230001720828.284700021
2295872.78795582720825.8302511422295506.37241147720867.040801361
#Sta/Elev= 30
       0  124.25   21.11  122.22   43.03  121.99   49.34  121.92   70.61  120.58
   95.31  119.71  134.07  119.58  159.22  120.65  168.57  119.91  173.98  118.91
  178.03  118.17  182.94  119.32  187.44   120.5  193.86  121.25  204.13  122.58
  224.85  123.67  263.45  123.97  302.88  123.25  315.74  123.59  331.34  123.33
  351.88  122.29  385.53  122.02  439.58  122.77  448.87  123.15  491.55  123.56
  506.41  124.03  522.55  125.27  544.07  126.32  560.14  126.31  593.58  127.08
#Mann= 5 ,-1 , 0
       0    .075       0   43.03     .09       0  173.98     .05       0
  193.86     .09       0  544.07     .04       0
Bank Sta=182.94,204.13
XS Rating Curve= 0 ,0
Exp/Cntr=0.3,0.1

Type RM Length L Ch R = 3 ,8283.838,,,
Bridge Culvert--1,0,-1,-1, 0
Deck Dist Width WeirC Skew NumUp NumDn MinLoCord MaxHiCord MaxSubmerge Is_Ogee
,,2.6,0, 64, 64, , , 0.98, 0, 0,0,,
       0    4.85    7.89   14.76   28.68   39.89   51.64   57.84      75   80.32
   89.68   93.48   95.65  107.45     117  121.66  129.44  135.41  139.07  149.24
  157.91  160.11  162.52  164.82  184.18  186.55  189.31  199.73   208.1  210.29
  212.45  230.97  232.75  233.93  248.98  250.46  252.64  255.17  260.94  269.85
  275.74   287.6  288.36   290.3  297.41  306.52  309.48  323.77  330.74  343.38
   344.9  347.28   358.3  365.54  371.29  380.07  384.17   386.9  403.49  407.75
  429.44  430.65  432.04  441.12
  126.72   126.6  126.49  126.03  125.24  125.11  125.48  125.47  124.86  125.04
  125.08  125.06  125.11  124.98  124.12  123.87  124.33   124.8  124.66  124.38
  124.71  124.79  124.72  124.83  124.86  124.88     125  124.44  125.42   125.4
  125.39   125.3  125.28  124.62  123.09  118.16  120.61  122.04  125.31  125.28
  125.33  125.16  125.15  125.16   125.3   125.4  125.39  125.23  125.38  125.33
  125.29  125.27  124.89  125.03  124.18  123.39  122.93  122.76  120.42  119.67
  120.26  120.31  120.37   120.8
                                                                                
                                                                                
                                                                                
                                                                                
                                                                                
                                                                                
                                
       0    4.85    7.89   14.76   28.68   39.89   51.64   57.84      75   80.32
   89.68   93.48   95.65  107.45     117  121.66  129.44  135.41  139.07  149.24
  157.91  160.11  162.52  164.82  184.18  186.55  189.31  199.73   208.1  210.29
  212.45  230.97  232.75  233.93  248.98  250.46  252.64  255.17  260.94  269.85
  275.74   287.6  288.36   290.3  297.41  306.52  309.48  323.77  330.74  343.38
   344.9  347.28   358.3  365.54  371.29  380.07  384.17   386.9  403.49  407.75
  429.44  430.65  432.04  441.12
  126.72   126.6  126.49  126.03  125.24  125.11  125.48  125.47  124.86  125.04
  125.08  125.06  125.11  124.98  124.12  123.87  124.33   124.8  124.66  124.38
  124.71  124.79  124.72  124.83  124.86  124.88     125  124.44  125.42   125.4
  125.39   125.3  125.28  124.62  123.09  118.16  120.61  122.04  125.31  125.28
  125.33  125.16  125.15  125.16   125.3   125.4  125.39  125.23  125.38  125.33
  125.29  125.27  124.89  125.03  124.18  123.39  122.93  122.76  120.42  119.67
  120.26  120.31  120.37   120.8
                                                                                
                                                                                
                                                                                
                                                                                
                                                                                
                                                                                
                                
BR Coef=-1 , 0 , 0 ,, 0 ,,,0.8,-1,,0,
WSPro=,,,, 1 ,,,, 0 ,,,, 0 ,,,,-1 ,-1 ,-1 , 0 , 0 , 0 , 0 , 0
BC Design=,, 0 ,, 0 ,,,,,,
BC Use User HTab Curves=0
BC User HTab FreeFlow(D)= 0

Type RM Length L Ch R = 1 ,8165.540,346.9,502.55,358.04
XS GIS Cut Line= 6
2296159.72262067720732.0495901262296067.24930003720696.671900004
2296020.39530002720684.9603000132296013.94350001720686.345500022
2296006.54660003720680.4061000052295767.68425104720633.063157946
#Sta/Elev= 30
       0  123.45   10.83   122.6   22.89  122.55   29.28  122.81   30.96  122.88
    67.1  120.95   83.09  120.61   86.39  120.57  123.96  122.32  126.21  122.03
  129.62  122.01  138.03  121.25  144.07   120.6  146.43  120.19  147.92  119.93
  152.45  119.83  155.22  118.16  169.38  119.06  170.69  119.15  193.47  120.86
  204.62  120.85  219.23   120.5  230.74  120.57  246.63   120.3  273.54  120.15
  289.92  121.26  299.39  121.46  312.74  121.49  362.95  123.12  407.76  123.64
#Mann= 5 ,-1 , 0
       0    .085       0   29.28     .07       0  138.03     .05       0
  170.69     .07       0  362.95     .09       0
Bank Sta=146.43,169.38
XS Rating Curve= 0 ,0
Exp/Cntr=0.3,0.1

Type RM Length L Ch R = 1 ,7662.986,289.28,349.96,273.02
XS GIS Cut Line= 2
2296398.07152978720432.4853874152295810.66520184720274.888567731
#Sta/Elev= 30
       0  124.23     9.7  124.21   36.19  123.39   64.78  123.14   79.71  123.31
  109.57  120.21  134.47  120.64  148.15  120.04  156.88  119.95  195.94  117.39
  200.01  117.65  211.68  117.52  230.08  117.67  255.44  117.26  256.71117.2432
  259.35   117.2  278.73   117.9  283.11  118.05     294  118.53  362.93  117.88
   395.1  117.78  408.14  118.68  429.38  118.34  435.32  118.24  561.96  124.17
  590.54  125.12  597.36  125.35  599.31  125.68  603.57  125.37  608.18  125.35
#Mann= 6 ,-1 , 0
       0    .085       0  148.15     .07       0  255.44     .05       0
  283.11     .07       0  429.38     .09       0  590.54    .045       0
Bank Sta=256.71,278.73
XS Rating Curve= 0 ,0
Exp/Cntr=0.3,0.1

Type RM Length L Ch R = 1 ,7313.030,366.39,394.91,324.27
XS GIS Cut Line= 2
2296538.73645978720155.0628866552295873.18294854720028.724940285
#Sta/Elev= 30
       0  117.63    5.56  117.45   33.79  120.97   77.42  120.52  121.67  119.32
  142.45  118.99  164.88     118   190.5  118.13  231.26   116.6  255.81  117.05
  281.81  116.91  302.32  118.52  340.21  118.41  351.62  116.16  355.59  115.96
  359.27  115.76  369.57  116.87     373  118.03  377.27  117.83  377.81  117.81
  405.04  116.72  424.22   116.1  462.89  117.96  488.76  119.18  530.37   120.1
  561.27  119.96  588.07  120.49  608.03  121.11  626.94  122.17  677.44  123.42
#Mann= 6 ,-1 , 0
       0    .085       0  121.67     .07       0  377.27     .05       0
  405.04     .07       0  462.89     .09       0  530.37    .045       0
Bank Sta=355.59,377.81
XS Rating Curve= 0 ,0
Exp/Cntr=0.3,0.1

Type RM Length L Ch R = 1 ,6918.116,567.05,636.61,420.75
XS GIS Cut Line= 3
2296511.38494556719753.9073456532296017.75523764719759.117157862
2295887.50993212719753.907345653
#Sta/Elev= 30
       0  118.52    5.06  118.55   51.69  116.93   70.09  115.92  100.69  116.14
  130.16  115.16  156.22  115.35  192.56  114.72  197.28  115.02   210.6  113.85
  219.53  113.29  231.34  112.85  239.99  113.47  240.12  113.48  274.86  115.78
  305.47  115.34  329.58  114.29  369.85  119.75  373.92   120.3  378.78  120.57
  401.38  121.62   423.3  122.34  436.56  123.06  447.48  122.82  461.55  123.27
  527.58   123.2  557.49  123.81  582.05   123.3  608.32  123.17  624.01  122.88
#Mann= 4 ,-1 , 0
       0    .085       0   210.6     .05       0  240.12     .09       0
  369.85    .045       0
Bank Sta=219.53,239.99
XS Rating Curve= 0 ,0
Exp/Cntr=0.3,0.1

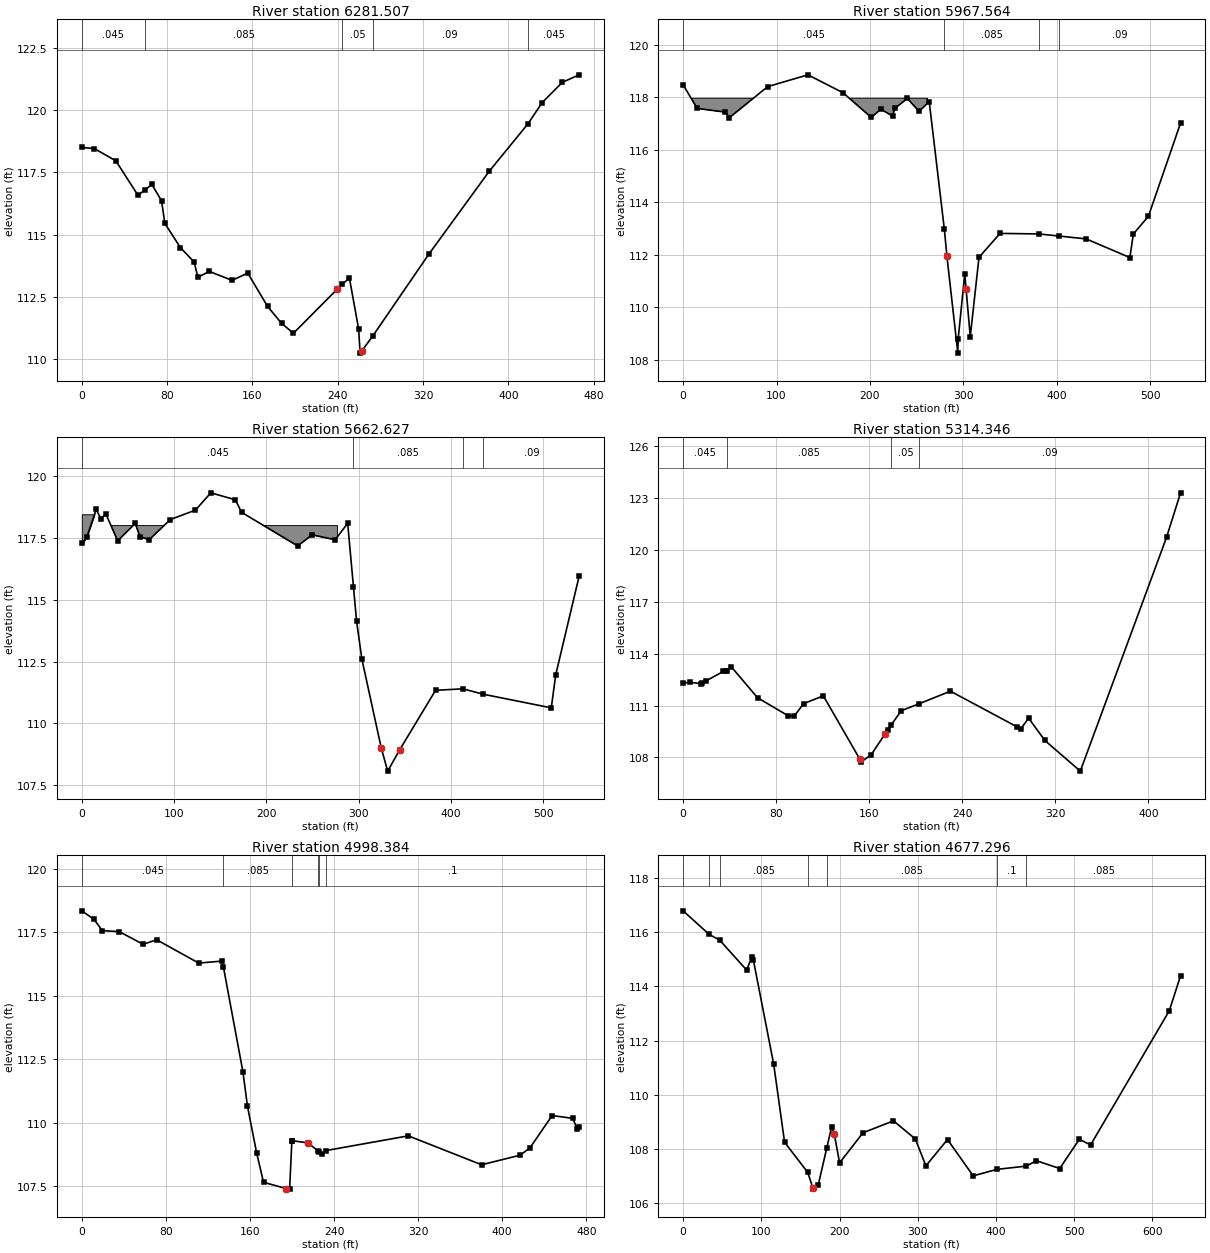
Type RM Length L Ch R = 1 ,6281.507,196.89,313.94,345.97
XS GIS Cut Line= 2
2296232.65999177719208.1795154962295869.27558932719501.231452927
#Sta/Elev= 30
       0  118.51    11.9  118.46    31.9  117.97   52.76  116.58   58.96  116.79
    65.7  117.02    74.8  116.36   77.87  115.45   92.45  114.48  105.44  113.89
  108.88  113.28  119.48  113.52  140.87  113.16  155.64  113.45  174.21  112.11
  187.33  111.43  198.47  111.03  239.44   112.8  244.38  113.01  250.96  113.25
  259.64  111.19  260.97  110.23  262.78  110.33  272.72  110.91   325.4  114.21
  382.08  117.55  418.42  119.46  431.66  120.31   450.7  121.13  466.44  121.43
#Mann= 5 ,-1 , 0
       0    .045       0   58.96    .085       0  244.38     .05       0
  272.72     .09       0  418.42    .045       0
Bank Sta=239.44,262.78
XS Rating Curve= 0 ,0
Exp/Cntr=0.3,0.1

Type RM Length L Ch R = 1 ,5967.564,272.24,304.94,320.02
XS GIS Cut Line= 2
2296263.91886508719049.2802427562295735.12292469719113.100442454
#Sta/Elev= 30
       0  118.47    15.1  117.57   45.26  117.43   49.62  117.22   90.47   118.4
  133.66  118.85   171.1  118.17  201.43  117.23  211.71  117.54  224.26  117.28
   226.6  117.57  240.14  117.95  252.61  117.46  263.51  117.83  279.74  112.96
  282.46  111.94  294.16  108.25  294.49  108.78  301.56  111.27  302.96   110.7
  307.46  108.88  316.82   111.9  339.36  112.81  380.73  112.79  402.56  112.71
  431.61   112.6  478.35  111.89  482.12  112.79  498.19  113.46  532.63  117.01
#Mann= 4 ,-1 , 0
       0    .045       0  279.74    .085       0  380.73     .05       0
  402.56     .09       0
#Block Obstruct= 1 ,-1
   10.01  261.71117.9586
Bank Sta=282.46,302.96
XS Rating Curve= 0 ,0
Exp/Cntr=0.3,0.1

Type RM Length L Ch R = 1 ,5662.627,271.88,348.28,346.27
XS GIS Cut Line= 2
2296293.87528537718805.7215214072295755.96217354 718775.76510115
#Sta/Elev= 30
       0  117.28    5.34  117.53   15.64  118.66   20.61  118.28   26.18  118.47
   38.87  117.39    57.9  118.09   62.95  117.56   72.98  117.43    95.9  118.25
  123.09  118.63  139.77  119.33  166.29  119.05  173.11  118.54  233.87  117.18
  249.52  117.63   274.5  117.43  287.97   118.1  294.21  115.54  297.65  114.13
  303.33  112.61  324.27  109.02   331.3  108.07  344.26  108.93  383.18  111.34
  412.79   111.4  435.04  111.18   508.5  110.63  513.29  111.96  538.75  115.97
#Mann= 4 ,-1 , 0
       0    .045       0  294.21    .085       0  412.79     .05       0
  435.04     .09       0
#Block Obstruct= 2 ,-1
   31.42  276.94118.0046       0   18.19118.4629
Bank Sta=324.27,344.26
XS Rating Curve= 0 ,0
Exp/Cntr=0.3,0.1

Type RM Length L Ch R = 1 ,5314.346,271.59,315.96,325.21
XS GIS Cut Line= 2
 2296188.4634181718551.5695152432295799.46410556718373.741258085
#Sta/Elev= 30
       0   112.3    5.49  112.34   15.14  112.27   16.59  112.28   19.56  112.42
   34.57  112.97   36.88  112.98   37.38  113.01   41.52  113.23   63.99  111.45
   90.02  110.42   95.55  110.39  103.63  111.11  120.55  111.56  152.05  107.89
  153.18  107.75  161.61  108.15  173.65  109.36  176.12  109.61  178.96  109.88
  187.54   110.7  203.21  111.11  229.85  111.83  287.36  109.76  290.55  109.67
  297.09  110.27  311.07  108.98  341.53  107.21  415.69  120.72  427.72  123.29
#Mann= 4 ,-1 , 0
       0    .045       0   37.38    .085       0  178.96     .05       0
  203.21     .09       0
Bank Sta=152.05,173.65
XS Rating Curve= 0 ,0
Exp/Cntr=0.3,0.1

Type RM Length L Ch R = 1 ,4998.384,312.13,321.09,298.29
XS GIS Cut Line= 6
 2296390.8520603718368.8622813522296280.50600003718300.788000003
2296270.67170003718293.2695000172296244.96440001718262.988300011
2296198.92210001718216.8622999942296009.54204936718093.162914857
#Sta/Elev= 30
       0  118.35   11.74  118.01   19.45  117.57   35.64  117.53   58.43  117.03
   71.22  117.21  111.26  116.29  133.57  116.37  134.69  116.15  153.29  112.01
  157.62  110.65  166.45  108.79  172.91  107.65  194.65   107.4  197.74  107.38
  199.89  109.29  200.47109.2869   215.1109.2044  224.65  108.89  225.46  108.86
  228.73  108.75  232.32   108.9  310.67  109.48  380.44  108.34   417.2  108.72
  426.49  109.01  447.48  110.28  467.14  110.17  471.46  109.74  473.26  109.84
#Mann= 6 ,-1 , 0
       0    .045       0  134.69    .085       0  200.47     .05       0
  224.65     .09       0  225.46    .085       0  232.32      .1       0
Bank Sta=194.65,215.1
XS Rating Curve= 0 ,0
Exp/Cntr=0.3,0.1

Type RM Length L Ch R = 1 ,4677.296,360.98,388.56,348.58
XS GIS Cut Line= 2
2296589.84474818718145.4123915882296084.02534598717759.655616701
#Sta/Elev= 30
       0  116.79   33.27  115.92   46.69  115.71   81.34   114.6   87.88   115.1
   89.86  114.97  115.88  111.12  129.75  108.25  159.29  107.14  165.97  106.56
  166.31  106.52  172.77  106.67  183.78  108.05  189.93  108.82  193.26  108.56
   200.1  107.49  230.05   108.6  268.97  109.04     297  108.37  310.48  107.38
   338.1  108.35  370.97  107.01   401.4  107.25  439.12  107.37  451.69  107.57
  481.59  107.28  506.72  108.36  521.08  108.15  621.68   113.1  636.13  114.39
#Mann= 7 ,-1 , 0
       0    .045       0   33.27    .085       0   46.69    .085       0
  159.29     .05       0  183.78    .085       0   401.4      .1       0
  439.12    .085       0
Bank Sta=165.97,193.26
XS Rating Curve= 0 ,0
Exp/Cntr=0.3,0.1

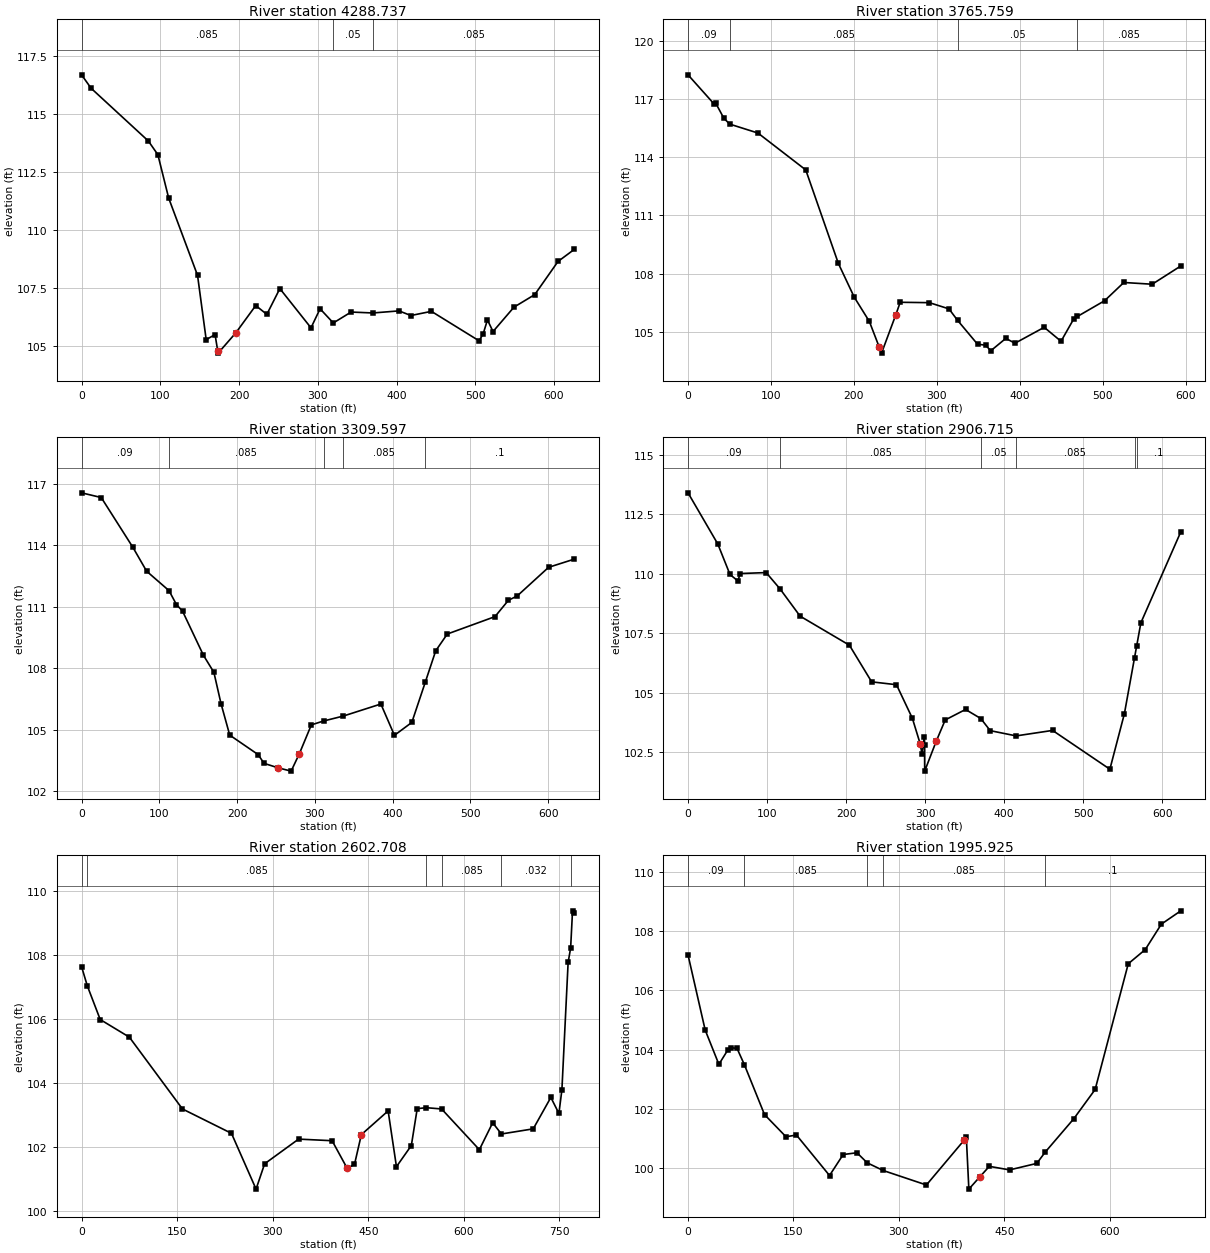
Type RM Length L Ch R = 1 ,4288.737,470.29,522.98,434.49
XS GIS Cut Line= 2
2296863.32073273717896.3936089282296350.83118452 717537.31741789
#Sta/Elev= 30
       0   116.7   12.17  116.12    84.8  113.85   96.91  113.26  110.63  111.39
   147.3  108.06  158.27  105.29  169.53  105.51  172.96   104.8  173.43  104.71
  196.05  105.59  221.19  106.76   235.3  106.38  251.82  107.49  291.36   105.8
  302.92  106.62   319.7  106.01  342.31  106.48  370.01  106.44  403.11  106.53
  418.24  106.33  444.28  106.51  504.84  105.24  510.12  105.55  515.43  106.14
  522.55  105.64  549.12  106.69  575.49  107.23  605.08  108.66  625.76  109.18
#Mann= 3 ,-1 , 0
       0    .085       0   319.7     .05       0  370.01    .085       0
Bank Sta=172.96,196.05
XS Rating Curve= 0 ,0
Exp/Cntr=0.3,0.1

Type RM Length L Ch R = 1 ,3765.759,438.64,456.16,409.3
XS GIS Cut Line= 2
 2297085.7824527717463.6575961112296553.48833533717200.145656809
#Sta/Elev= 30
       0  118.24   31.15  116.75   33.28  116.79   43.22     116   50.31   115.7
   84.31  115.24  141.91  113.34  181.23  108.52   200.4  106.78   218.6  105.53
  230.21  104.24  233.25   103.9  250.41  105.87  255.75  106.52  290.94   106.5
  314.54  106.18  324.89  105.59  348.96  104.36  358.72  104.31  364.91  104.02
  383.07  104.66  394.09  104.41  429.32  105.23  449.62  104.51  464.88  105.66
   469.4  105.79  502.13   106.6  525.31  107.54  559.48  107.45  593.95  108.39
#Mann= 4 ,-1 , 0
       0     .09       0   50.31    .085       0  324.89     .05       0
   469.4    .085       0
Bank Sta=230.21,250.41
XS Rating Curve= 0 ,0
Exp/Cntr=0.3,0.1

Type RM Length L Ch R = 1 ,3309.597,365.81,402.88,371.45
XS GIS Cut Line= 2
2297235.98425813717042.0384932312296640.44727531716825.958702996
#Sta/Elev= 30
       0  116.57   25.31  116.34    66.1   113.9   83.67  112.74  112.45  111.79
  121.98  111.11  129.81  110.79  156.71  108.63  170.12   107.8  179.29  106.27
   190.5  104.73  226.95  103.78  234.65  103.35  252.84  103.13  269.44  102.97
  280.02  103.82  295.43  105.23  311.19  105.42   336.4  105.66  384.83  106.25
  402.26  104.72  424.62  105.35  441.88  107.31  455.34  108.85  470.21  109.67
  531.52  110.52  548.84  111.32  560.09  111.53  600.46  112.93  633.53  113.33
#Mann= 5 ,-1 , 0
       0     .09       0  112.45    .085       0  311.19     .05       0
   336.4    .085       0  441.88      .1       0
Bank Sta=252.84,280.02
XS Rating Curve= 0 ,0
Exp/Cntr=0.3,0.1

Type RM Length L Ch R = 1 ,2906.715,287.44,304.01,266.11
XS GIS Cut Line= 2
2297375.77261503716709.7401583942296795.09773789716482.727346361
#Sta/Elev= 30
       0   113.4   37.69  111.25    53.1  109.97   63.04   109.7   66.09  110.01
   98.86  110.05  116.53  109.36  141.82  108.22  204.19     107  232.34  105.46
  263.75  105.34  283.85  103.93  293.84  102.85  296.09  102.42  298.79  103.14
  299.28  102.82  299.45  101.71  313.98  102.96  325.44  103.86  351.15   104.3
  370.41  103.92  382.39  103.41  415.17  103.19  461.27  103.42  533.76  101.79
  552.12  104.12  564.99  106.48  567.73  106.98  572.97  107.94  623.47  111.76
#Mann= 6 ,-1 , 0
       0     .09       0  116.53    .085       0  370.41     .05       0
  415.17    .085       0  564.99    .032       0  567.73      .1       0
Bank Sta=293.84,313.98
XS Rating Curve= 0 ,0
Exp/Cntr=0.3,0.1

Type RM Length L Ch R = 1 ,2602.708,433.64,606.78,535.93
XS GIS Cut Line= 2
2297569.33090743716443.2988053112296810.63019343716237.792470187
#Sta/Elev= 30
       0  107.63    9.04  107.03   29.26  105.98   75.01  105.43  158.34  103.19
  235.25  102.43  273.85  100.69  287.27  101.48  340.59  102.25  393.18   102.2
  416.76101.3412   428.3  101.46  439.08  102.39  481.09  103.13  494.15  101.39
  517.51  102.05  526.74   103.2  541.03  103.23  565.01  103.19  624.26  101.92
  645.15  102.76  658.86  102.41  708.81  102.57  736.43  103.55  749.09  103.05
   753.8  103.79  763.55  107.76  767.49  108.21  770.47  109.37  773.26  109.29
#Mann= 6 ,-1 , 0
       0     .09       0    9.04    .085       0  541.03     .05       0
  565.01    .085       0  658.86    .032       0  767.49      .1       0
Bank Sta=416.76,439.08
XS Rating Curve= 0 ,0
Exp/Cntr=0.3,0.1

Type RM Length L Ch R = 1 ,1995.925,383.02,385.49,353.32
XS GIS Cut Line= 2
2297789.17489387716213.8963847012297227.61688508 715794.52008453
#Sta/Elev= 30
       0   107.2    24.4  104.66   43.88   103.5   56.75  103.99   61.56  104.06
   69.69  104.04   80.11  103.49  108.82   101.8  139.38  101.05  154.18  101.11
  201.28   99.74   220.7  100.45  240.29  100.51  254.84  100.17  277.55   99.91
  339.08   99.42  392.91  100.94  395.85  101.03  399.45   99.28  414.85   99.69
  428.55  100.05  457.39   99.93  496.07  100.15  507.99  100.53   548.7  101.66
  579.08  102.65  626.16   106.9  650.34  107.38  673.25  108.24  700.87  108.69
#Mann= 5 ,-1 , 0
       0     .09       0   80.11    .085       0  254.84     .05       0
  277.55    .085       0  507.99      .1       0
Bank Sta=392.91,414.85
XS Rating Curve= 0 ,0
Exp/Cntr=0.3,0.1

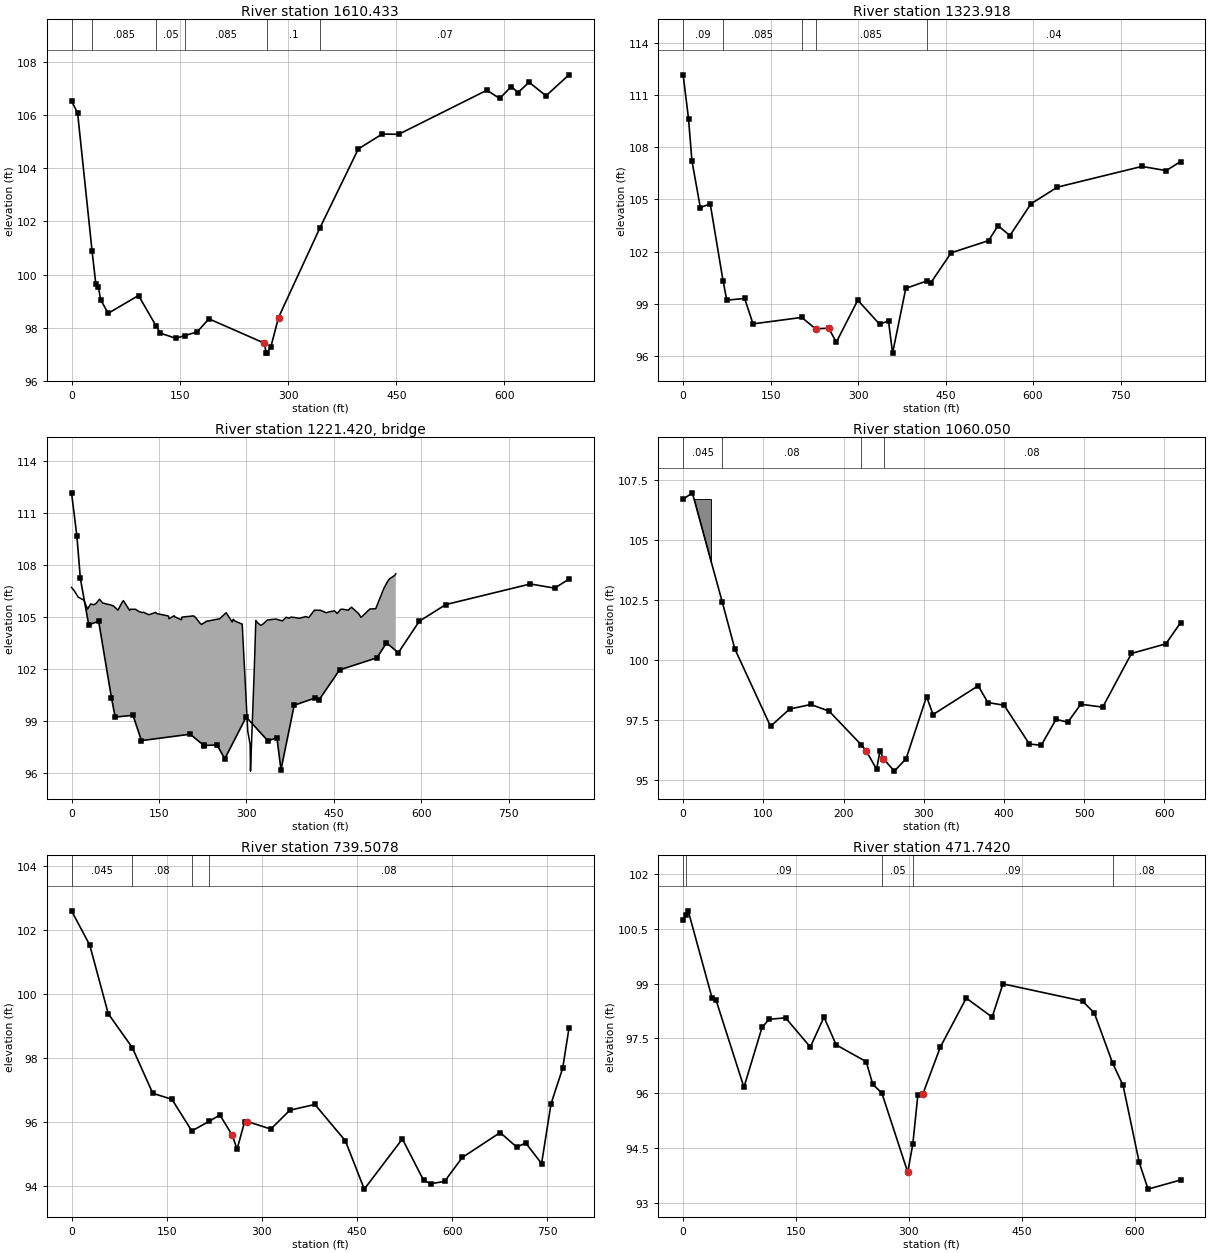
Type RM Length L Ch R = 1 ,1610.433,236.43,286.52,231.76
XS GIS Cut Line= 2
2297968.39553496 715839.922646942297365.01937659715506.572254509
#Sta/Elev= 30
       0  106.53    8.38  106.09   28.47  100.88   33.62   99.65   37.36   99.52
   40.27   99.05   50.83   98.54   92.81   99.21  117.46   98.05  123.26   97.79
  144.29    97.6   157.1    97.7  174.07   97.84  190.41   98.33  266.84   97.42
  269.98   97.04  270.63   97.05   276.2   97.27  286.83   98.38  344.12  101.75
  397.46  104.73  430.54  105.29   453.3  105.28  575.62  106.94  593.31  106.63
  609.56  107.08  618.63  106.85  634.11  107.24  657.55  106.73  689.34  107.52
#Mann= 6 ,-1 , 0
       0     .09       0   28.47    .085       0  117.46     .05       0
   157.1    .085       0  270.63      .1       0  344.12     .07       0
Bank Sta=266.84,286.83
XS Rating Curve= 0 ,0
Exp/Cntr=0.3,0.1

Type RM Length L Ch R = 1 ,1323.918,273.48,263.87,226.02
XS GIS Cut Line= 6
2298087.26220195715728.1700717212297985.40670003     715596.7667
2297952.95590003715546.9402000012297945.11310002715528.603599995
2297926.08090004715495.3326000122297373.12354781715363.437611148
#Sta/Elev= 30
       0  112.15    9.25  109.63   15.11  107.21   29.47  104.53   46.47  104.74
    68.4  100.33   74.85   99.21  105.44   99.31  119.85   97.85  203.42   98.22
  227.05 97.5658   227.997.56966  249.57    97.6  262.71    96.8  299.51   99.21
  336.84   97.83  352.16   98.02  359.13   96.17  381.83   99.89  417.59  100.31
  424.89  100.22  459.58  101.93  523.76  102.63  540.05  103.49  560.34  102.92
   596.3  104.74   641.6   105.7  786.62  106.89  828.37  106.65  852.93  107.17
#Mann= 5 ,-1 , 0
       0     .09       0    68.4    .085       0  203.42     .05       0
   227.9    .085       0  417.59     .04       0
Bank Sta=227.05,249.57
XS Rating Curve= 0 ,0
Exp/Cntr=0.3,0.1

Type RM Length L Ch R = 3 ,1221.420,,,
Bridge Culvert--1,0,-1,-1, 0
Deck Dist Width WeirC Skew NumUp NumDn MinLoCord MaxHiCord MaxSubmerge Is_Ogee
,,2.6,0, 99, 99, , , 0.98, 0, 0,0,,
       0    4.47   11.38   20.99   27.47    32.8   38.03   41.87   47.89   53.48
    67.1   71.92   79.64   86.83   88.99   98.93   99.88  100.85  109.45  110.02
  116.27  121.22  123.51  131.38  133.24  144.06  146.36  156.38  164.96  166.48
  167.16  175.42   176.3  176.86  188.42  189.41  204.13  209.14  212.61  220.71
  222.89  232.46  233.85  246.93   253.9  254.54  264.98  265.21  265.31  275.43
   277.2  280.25  292.65  302.22  304.25  306.23  306.88  313.32  316.01  319.33
  324.53   328.5  335.61  348.94  349.85  350.88  361.42   362.4  367.97  372.65
  376.64  383.47  390.78  401.58  406.76  416.45  417.56  418.84  426.95  436.74
  441.19  450.98  455.52  461.58  465.86  474.38  480.03  491.98  496.38  498.14
  507.29  508.68  512.03  521.52  535.66  542.48  545.32  554.33     556
  106.69  106.51  106.13  105.96  105.44  105.74  105.69  105.76  106.01  105.79
  105.68  105.62  105.38  105.84  105.93   105.4  105.36  105.43  105.43  105.42
  105.29  105.24  105.26  105.13  105.12  105.25  105.18  105.11  105.05  105.03
  104.88  105.05  105.05     105  104.82  104.98  105.03  105.05  104.96  104.61
  104.55  104.76  104.75  104.84  104.88   104.9  105.23  105.22  105.22   104.7
  104.85  104.75  104.57   98.38   98.01   97.62   96.09  101.95  104.79  104.64
   104.5  104.58  104.81  104.86  104.86  104.86  104.76  104.79  104.97  104.92
  104.98  104.95  104.91  105.01  104.95  105.38  105.36  105.38  105.37  105.23
  105.28  105.34  105.19  105.43  105.43  105.38  105.55  105.19  104.97  105.01
  105.31  105.36  105.45  105.46  106.65  107.06  107.19  107.39  107.48
                                                                                
                                                                                
                                                                                
                                                                                
                                                                                
                                                                                
                                                                                
                                                                                
                                                                                
                                                                        
       0    4.47   11.38   20.99   27.47    32.8   38.03   41.87   47.89   53.48
    67.1   71.92   79.64   86.83   88.99   98.93   99.88  100.85  109.45  110.02
  116.27  121.22  123.51  131.38  133.24  144.06  146.36  156.38  164.96  166.48
  167.16  175.42   176.3  176.86  188.42  189.41  204.13  209.14  212.61  220.71
  222.89  232.46  233.85  246.93   253.9  254.54  264.98  265.21  265.31  275.43
   277.2  280.25  292.65  302.22  304.25  306.23  306.88  313.32  316.01  319.33
  324.53   328.5  335.61  348.94  349.85  350.88  361.42   362.4  367.97  372.65
  376.64  383.47  390.78  401.58  406.76  416.45  417.56  418.84  426.95  436.74
  441.19  450.98  455.52  461.58  465.86  474.38  480.03  491.98  496.38  498.14
  507.29  508.68  512.03  521.52  535.66  542.48  545.32  554.33     556
  106.69  106.51  106.13  105.96  105.44  105.74  105.69  105.76  106.01  105.79
  105.68  105.62  105.38  105.84  105.93   105.4  105.36  105.43  105.43  105.42
  105.29  105.24  105.26  105.13  105.12  105.25  105.18  105.11  105.05  105.03
  104.88  105.05  105.05     105  104.82  104.98  105.03  105.05  104.96  104.61
  104.55  104.76  104.75  104.84  104.88   104.9  105.23  105.22  105.22   104.7
  104.85  104.75  104.57   98.38   98.01   97.62   96.09  101.95  104.79  104.64
   104.5  104.58  104.81  104.86  104.86  104.86  104.76  104.79  104.97  104.92
  104.98  104.95  104.91  105.01  104.95  105.38  105.36  105.38  105.37  105.23
  105.28  105.34  105.19  105.43  105.43  105.38  105.55  105.19  104.97  105.01
  105.31  105.36  105.45  105.46  106.65  107.06  107.19  107.39  107.48
                                                                                
                                                                                
                                                                                
                                                                                
                                                                                
                                                                                
                                                                                
                                                                                
                                                                                
                                                                        
BR Coef=-1 , 0 , 0 ,, 0 ,,,0.8,-1,,0,
WSPro=,,,, 1 ,,,, 0 ,,,, 0 ,,,,-1 ,-1 ,-1 , 0 , 0 , 0 , 0 , 0
BC Design=,, 0 ,, 0 ,,,,,,
BC Use User HTab Curves=0
BC User HTab FreeFlow(D)= 0

Type RM Length L Ch R = 1 ,1060.050,212.15,320.54,294.89
XS GIS Cut Line= 6
2298186.60618123715378.6848473252298029.94720003 715320.94130002
2297969.03780001715303.1412000212297958.95480001715298.795699999
2297951.62040004715297.1363999992297606.93966734715158.947133482
#Sta/Elev= 30
       0  106.69   11.47  106.96   48.76  102.41   64.45  100.45     109   97.22
  132.85   97.94  159.26   98.13  182.12   97.85  222.08   96.45  227.97   96.21
  241.26   95.43  245.66   96.21  249.62   95.87  250.18   95.85  263.44   95.35
   278.1   95.87  303.62   98.46  311.66   97.71  367.94   98.91  380.04   98.21
  400.27    98.1  431.78   96.48  446.61   96.43  465.06   97.51  479.78   97.39
  495.82   98.14  523.27   98.02  559.15  100.26  602.01  100.66  620.32  101.54
#Mann= 4 ,-1 , 0
       0    .045       0   48.76     .08       0  222.08     .05       0
  250.18     .08       0
#Block Obstruct= 1 ,-1
       0   35.33106.6887
Bank Sta=227.97,249.62
XS Rating Curve= 0 ,0
Exp/Cntr=0.3,0.1

Type RM Length L Ch R = 1 ,739.5078,190.33,267.77,284.34
XS GIS Cut Line= 2
2298251.84842025715244.5710598532297670.71683456714718.301546931
#Sta/Elev= 30
       0   102.6   28.67  101.53   57.85   99.38   95.73   98.32  128.05   96.89
  158.27    96.7  189.57   95.71  216.62   96.01  233.86   96.21  253.47   95.57
  260.91   95.14  272.82      96  276.9996.00634  314.09   95.77  344.17   96.36
  383.58   96.54  431.68    95.4   461.4   93.89  521.44   95.46  554.81   94.17
  565.93   94.06   587.9   94.13   615.9   94.88  675.56   95.66  701.56   95.21
  716.07   95.33  740.86   94.69  755.75   96.56  774.08   97.67  784.01   98.92
#Mann= 4 ,-1 , 0
       0    .045       0   95.73     .08       0  189.57     .05       0
  216.62     .08       0
Bank Sta=253.47,276.99
XS Rating Curve= 0 ,0
Exp/Cntr=0.3,0.1

Type RM Length L Ch R = 1 ,471.7420,298.35,351.96,292.58
XS GIS Cut Line= 2
2298347.34906545715151.1023432612298040.52784367714565.906900331
#Sta/Elev= 30
       0  100.73     3.9  100.88    6.72  100.99   38.61   98.59   43.48   98.56
   80.78   96.16  104.86    97.8  114.21   98.02  136.11   98.06  168.94   97.26
  187.09   98.08   203.3   97.32  243.19   96.86  251.91   96.24  263.97      96
   298.4   93.83  305.14   94.61  311.82   95.95  318.55   95.98  341.66   97.26
  376.11    98.6  410.46   98.08  424.84   98.99  530.51   98.52  546.22   98.19
  570.69   96.81  584.42   96.21  605.85    94.1  617.61   93.37  660.75   93.62
#Mann= 5 ,-1 , 0
       0    .045       0     3.9     .09       0  263.97     .05       0
  305.14     .09       0  570.69     .08       0
Bank Sta=298.4,318.55
XS Rating Curve= 0 ,0
Exp/Cntr=0.3,0.1

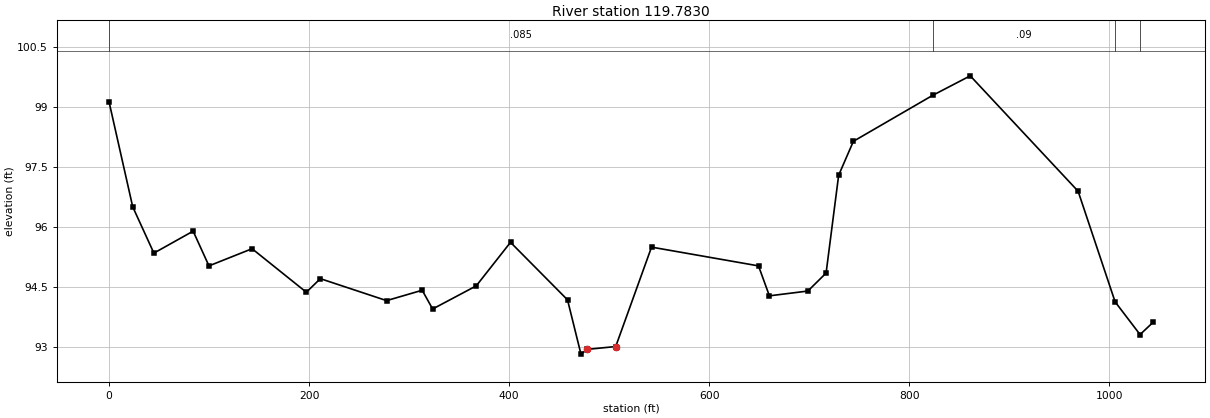
Type RM Length L Ch R = 1 ,119.7830,70.97,119.78,195.87
XS GIS Cut Line= 4
2298635.88292968715250.6668457092298542.41421312714842.249192834
2298477.39249723714702.0461179612298127.90077437714387.097181663
#Sta/Elev= 30
       0   99.12   23.58    96.5   44.76   95.34   84.01   95.89   99.83   95.02
  142.93   95.45   197.2   94.36  211.21    94.7  277.47   94.15  313.03   94.41
  323.49   93.94   367.1   94.52  401.35   95.61  458.35   94.17  471.79   92.81
  478.25   92.93  506.54      93  542.36   95.49  649.32   95.02  660.21   94.27
  698.66   94.39   716.9   94.84  729.46   97.29  744.19   98.14  823.39   99.29
  861.04   99.78  968.89   96.89 1005.88   94.12 1030.83    93.3 1043.99   93.61
#Mann= 4 ,-1 , 0
       0    .085       0  823.39     .09       0 1005.88     .08       0
 1030.83     .04       0
Bank Sta=478.25,506.54
XS Rating Curve= 0 ,0
Exp/Cntr=0.3,0.1

Chan Stop Cuts=-1
Use User Specified Reach Order=0