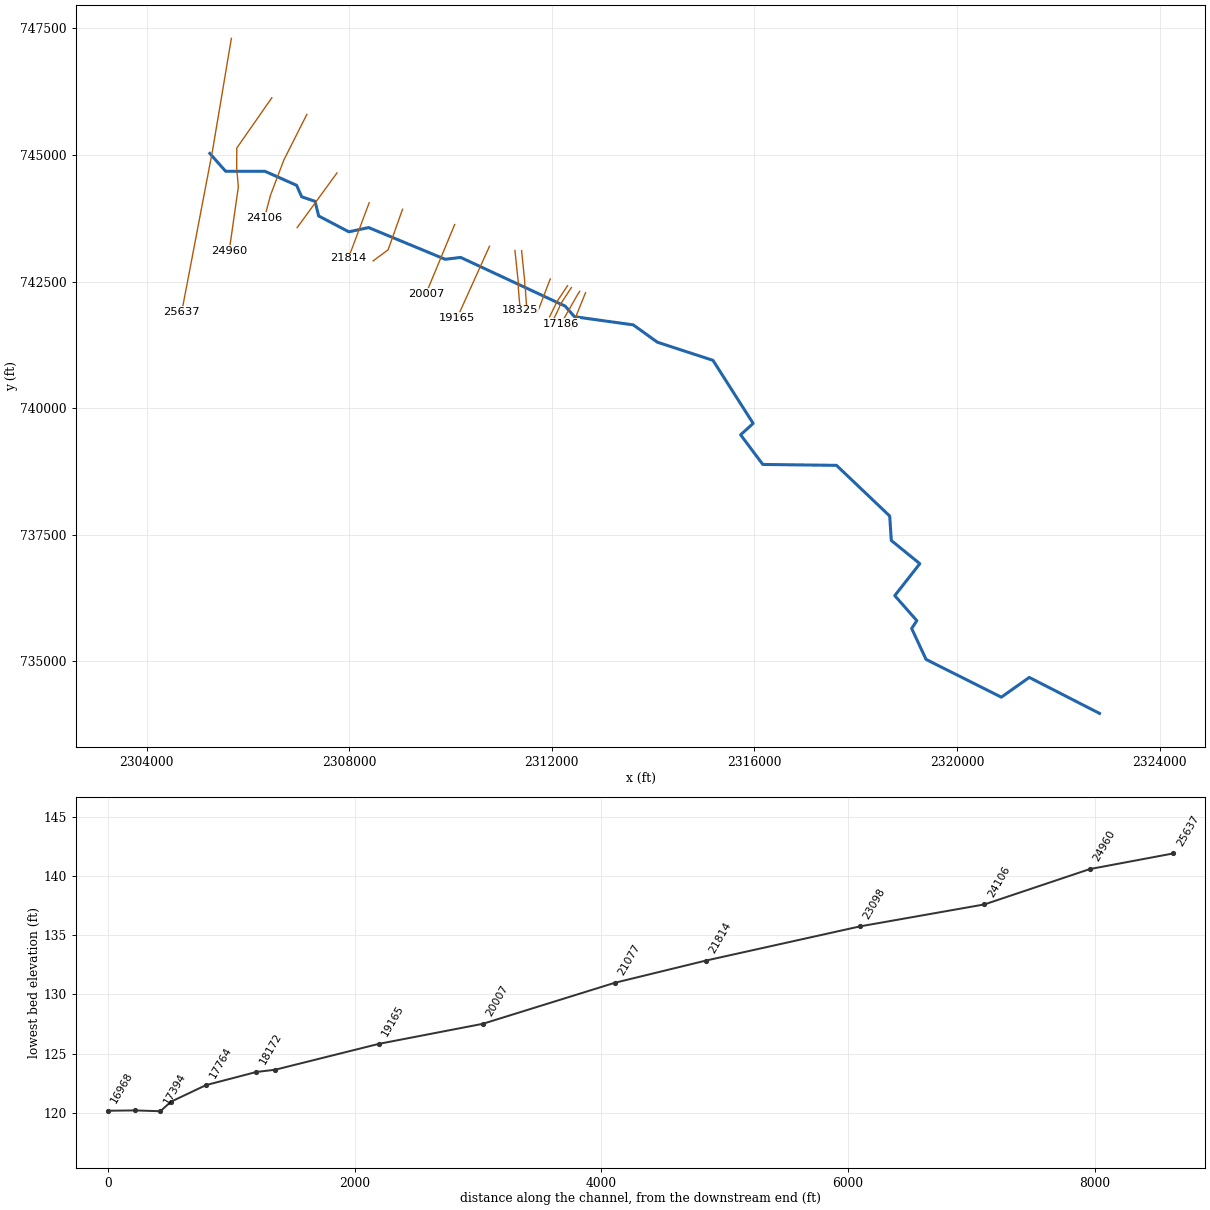
--- dtl_toisnot_swp_tri.prj (project) ---

Proj Title=dtl_toisnot_swp_trib
Current Plan=p02
Default Exp/Contr=0.3,0.1
English Units
Geom File=g01
Flow File=f01
Flow File=f02
Plan File=p01
Plan File=p02
Y Axis Title=Elevation
X Axis Title(PF)=Main Channel Distance
X Axis Title(XS)=Station
BEGIN DESCRIPTION:
END DESCRIPTION:
DSS File=dss
DSS Export Rating Curves= 0
DSS Export Rating Curve Sorted= 0
DSS Export Volume Flow Curves= 0
DXF OffsetX= 0
DXF OffsetY= 0
DXF ScaleX= 1
DXF ScaleY= 10

--- dtl_toisnot_swp_tri.p02 (plan) ---

Plan Title=dtl_toisnot_swp_trib_future
Program Version=4.00
Short Identifier=Future
Geom File=g01
Flow File=f02
Subcritical Flow
K Sum by GR= 0
Std Step Tol= 0.01
Critical Tol= 0.01
Num of Std Step Trials= 20
Max Error Tol= 0.3
Flow Tol Ratio= 0.001
Split Flow NTrial= 30
Split Flow Tol= 0.02
Split Flow Ratio= 0.02
Log Output Level= 0
Friction Slope Method= 1
Unsteady Friction Slope Method= 2
Unsteady Bridges Friction Slope Method= 1
Parabolic Critical Depth
Global Vel Dist= 0 , 0 , 0
Global Log Level= 0
CheckData=True
Encroach Param=-1 ,10,10, 2
Computation Interval=1HOUR
Output Interval=1HOUR
Run HTab= 0
Run UNet= 0
Run PostProcess= 0
Run WQNet= 0
UNET Theta= 1
UNET Theta Warmup= 1
UNET ZTol= 0.02
UNET ZSATol= 0.05
UNET MxIter= 20
UNET MaxInSteps= 0
UNET DtIC= 0
UNET DtMin= 0
UNET MaxCRTS= 20
UNET WFStab= 2
UNET SFStab= 1
UNET WFX= 1
UNET SFX= 1
UNET DSS MLevel= 4
UNET DZMax Abort= 100
UNET Convert EG Bridges= 0
UNET Use Existing IB Tables=-1
UNET Froude Reduction=False
UNET Froude Limit= 1
UNET Froude Power= 10
UNET Time Slicing=0,0, 5
Instantaneous Interval=1HOUR
DSS File=dss
Write IC File= 0
Echo Input=False
Echo Output=False
Write Detailed= 0
Detailed Automatic Start=False, 10
WQ ULTIMATE=-1
WQ Max Comp Step=1HOUR
WQ Output Interval=15MIN
WQ Output Selected Increments= 0
WQ Output face flow=0
WQ Output face velocity=0
WQ Output face area=0
WQ Output face dispersion=0
WQ Output cell volume=0
WQ Output cell surface area=0
WQ Output cell continuity=0
WQ Output face conc=0
WQ Output face dconc_dx=0
WQ Output face courant=0
WQ Output face peclet=0
WQ Output face adv mass=0
WQ Output face disp mass=0
WQ Output cell mass=0
WQ Output cell source sink temp=0
WQ Output cell source sink nsm=0
WQ Output MaxMinRange=-1
WQ Daily Max Min Mean=-1
WQ Daily Range=0
WQ Daily Time=0
WQ Create Restart=0
WQ Fixed Restart=0
WQ System Summary=False
Sorting and Armoring Iterations= 10
XS Update Threshold= 0.02
Hydraulics Update Threshold= 0.02
Energy Slope Method= 1
Volume Change Method= 0
XS Weighting Method= 0
Number of US Weighted Cross Sections= 1
Number of DS Weighted Cross Sections= 1
Upstream XS Weight=0.25
Main XS Weight=0.5
Downstream XS Weight=0.25
Number of DS XS's Weighted with US Boundary= 1
Upstream Boundary Weight= 1
Weight of XSs Associated with US Boundary= 0
Number of US XS's Weighted with DS Boundary= 1
Downstream Boundary Weight= 0.5
Weight of XSs Associated with DS Boundary= 0.5
Sediment Output Level= 4
Mass or Volume Output= 0
Output Increment Type= 1
Profile and TS Output Increment= 10
XS Output Flag= 0
XS Output Increment= 10
Disregard all LS=0
Disregard all Conn=0
Disregard all Breaches=0
Disregard all Pumps=0

--- dtl_toisnot_swp_tri.p01 (plan) ---

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Plan Title=dtl_toisnot_swp_trib
Short Identifier=dtl_toisnot_
Geom File=g01
Flow File=f01
Encroach River=Toisnot_Smp_Trib
Encroach Reach=Main
Encroach Node=25637
       1    2308    2400
Encroach Node=24960
       1    1545    1641
Encroach Node=24106
       1    1350    1450
Encroach Node=23098
       1     640     735
Encroach Node=21814
       1     545     625
Encroach Node=21077
       1     555     620
Encroach Node=20007
       1     645     735
Encroach Node=19165
       1     435     550
Encroach Node=18325
       1     630     750
Encroach Node=18172
       1     620     780
Encroach Node=17764
       1     290     455
Encroach Node=17480
       1     295     460
Encroach Node=17394
       1     225     430
Encroach Node=17186
       1     280     485
Encroach Node=16968
       1     320     530
Encroach Node=16910
       1     305     520
Encroach Node=16547
       1     375     590
Encroach Node=16093
       1     265     480
Encroach Node=15360
       4       1
Encroach Node=14945
       4       1
Encroach Node=14903
       4       1
Encroach Node=14726
       4       1
Encroach Node=14524
       1     250     720
Encroach Node=14330
       1     177     227
Encroach Node=13782
       1     265     380
Encroach Node=12590
       1     320     565
Encroach Node=11692
       1     800     982
Encroach Node=11665
       1     745     963
Encroach Node=11598
       1     745     957
Encroach Node=11571
       1     800     958
Encroach Node=11218
       1     670     925
Encroach Node=10485
       1     550     800
Encroach Node=9694
       1     365     555
Encroach Node=9130
       1     805     945
Encroach Node=8580
       1     420     550
Encroach Node=8235
       1     430     525
Encroach Node=7663
       1     370     475
Encroach Node=7426
       1     525     640
Encroach Node=6932
       1     320     450
Encroach Node=6694
       1     290     485
Encroach Node=5970
       1     575     770
Encroach Node=5620
       1     450     645
Encroach Node=4844
       1     250     435
Encroach Node=3918
       1     500     685
Encroach Node=3478
       1     465     635
Encroach Node=3072
       1     440     540
Encroach Node=2680
       1     400     480
Encroach Node=2328
       1  706.25  758.75
Encroach Node=2217
       1  678.25     726
Encroach Node=1722
       1     450     670
Encroach Node=878
       1     775    1018

--- dtl_toisnot_swp_tri.f02 (steady flow) ---

Flow Title=dtl_toisnot_swp_trib_future
Program Version=4.00
Number of Profiles= 3
Profile Names=100-yr 10%,100-yr 20%,100-yr 35%
River Rch & RM=Toisnot_Smp_Trib,Main            ,25637
    1100    1410    1730
River Rch & RM=Toisnot_Smp_Trib,Main            ,19165
    1300    1660    2030
River Rch & RM=Toisnot_Smp_Trib,Main            ,17764
    1800    2310    2820
River Rch & RM=Toisnot_Smp_Trib,Main            ,12590
    2000    2560    3130
River Rch & RM=Toisnot_Smp_Trib,Main            ,6932
    2160    2760    3380
Boundary for River Rch & Prof#=Toisnot_Smp_Trib,Main            , 1
Up Type= 0
Dn Type= 3
Dn Slope=0.002
Boundary for River Rch & Prof#=Toisnot_Smp_Trib,Main            , 2
Up Type= 0
Dn Type= 3
Dn Slope=0.002
Boundary for River Rch & Prof#=Toisnot_Smp_Trib,Main            , 3
Up Type= 0
Dn Type= 3
Dn Slope=0.002
Gate Openings=Toisnot_Smp_Trib,Main            ,14497   ,Gate #1     ,
     122       1     122       1     122       1
DSS Import GetInterval= 0
DSS Import GetPeak= 0
DSS Import FillOption= 0

--- dtl_toisnot_swp_tri.f01 (steady flow) ---

Flow Title=dtl_toisnot_swp_trib
Program Version=4.00
Number of Profiles= 6
Profile Names=100 yr,fway,10 yr,25 yr,50 yr,500 yr
River Rch & RM=Toisnot_Smp_Trib,Main            ,25637
     630     630     260     380     500    1030
River Rch & RM=Toisnot_Smp_Trib,Main            ,19165
     740     740     310     460     590    1200
River Rch & RM=Toisnot_Smp_Trib,Main            ,17764
    1050    1050     450     650     840    1660
River Rch & RM=Toisnot_Smp_Trib,Main            ,12590
    1160    1160     510     730     930    1840
River Rch & RM=Toisnot_Smp_Trib,Main            ,6932
    1260    1260     550     790    1010    1990
Boundary for River Rch & Prof#=Toisnot_Smp_Trib,Main            , 1
Up Type= 0
Dn Type= 3
Dn Slope=0.002
Boundary for River Rch & Prof#=Toisnot_Smp_Trib,Main            , 2
Up Type= 0
Dn Type= 3
Dn Slope=0.002
Boundary for River Rch & Prof#=Toisnot_Smp_Trib,Main            , 3
Up Type= 0
Dn Type= 3
Dn Slope=0.002
Boundary for River Rch & Prof#=Toisnot_Smp_Trib,Main            , 4
Up Type= 0
Dn Type= 3
Dn Slope=0.002
Boundary for River Rch & Prof#=Toisnot_Smp_Trib,Main            , 5
Up Type= 0
Dn Type= 3
Dn Slope=0.002
Boundary for River Rch & Prof#=Toisnot_Smp_Trib,Main            , 6
Up Type= 0
Dn Type= 3
Dn Slope=0.002
Gate Openings=Toisnot_Smp_Trib,Main            ,14497   ,Gate #1     ,
     122       1     122       1     122       1     122       1     122       1
     122       1
DSS Import GetInterval= 0
DSS Import GetPeak= 0
DSS Import FillOption= 0

--- dtl_toisnot_swp_tri.g01 (geometry) ---

Geom Title=dtl_toisnot_swp_trib
Program Version=4.00

River Reach=Toisnot_Smp_Trib,Main
Reach XY= 30
2305249.31732182745030.4028930962305561.97247317744677.486877471
2306337.20971689744677.7805176232306961.19427493744400.958313018
2307063.30090341 744174.05487062 2307326.1357886744084.475824386
2307397.52331549743795.3187256012307993.60491942743481.999328658
2308383.87890629743565.9536743312309895.05590829742939.700073287
2310201.37548834742976.0046997072312263.92791751742013.934082031
2312447.71972658741805.1829223782313607.19628909741644.081481948
2314083.69348145 741301.457275422315180.74969481740943.520690933
2315974.22290047739697.3010864412315726.47448733739472.615478516
2316164.39807133738887.2045288092317618.84912112738869.052307129
2318669.41210946737868.4080810552318701.17871103 737385.10369876
 2319263.8991089736926.758728027 2318769.2496949736295.967102066
 2319204.9042969735801.3176880332319102.79772958735647.023315445
2319386.42712408735036.6530761872320872.64471437 734290.14068605
2321424.02008063734680.4146728522322809.89550781733970.281311035

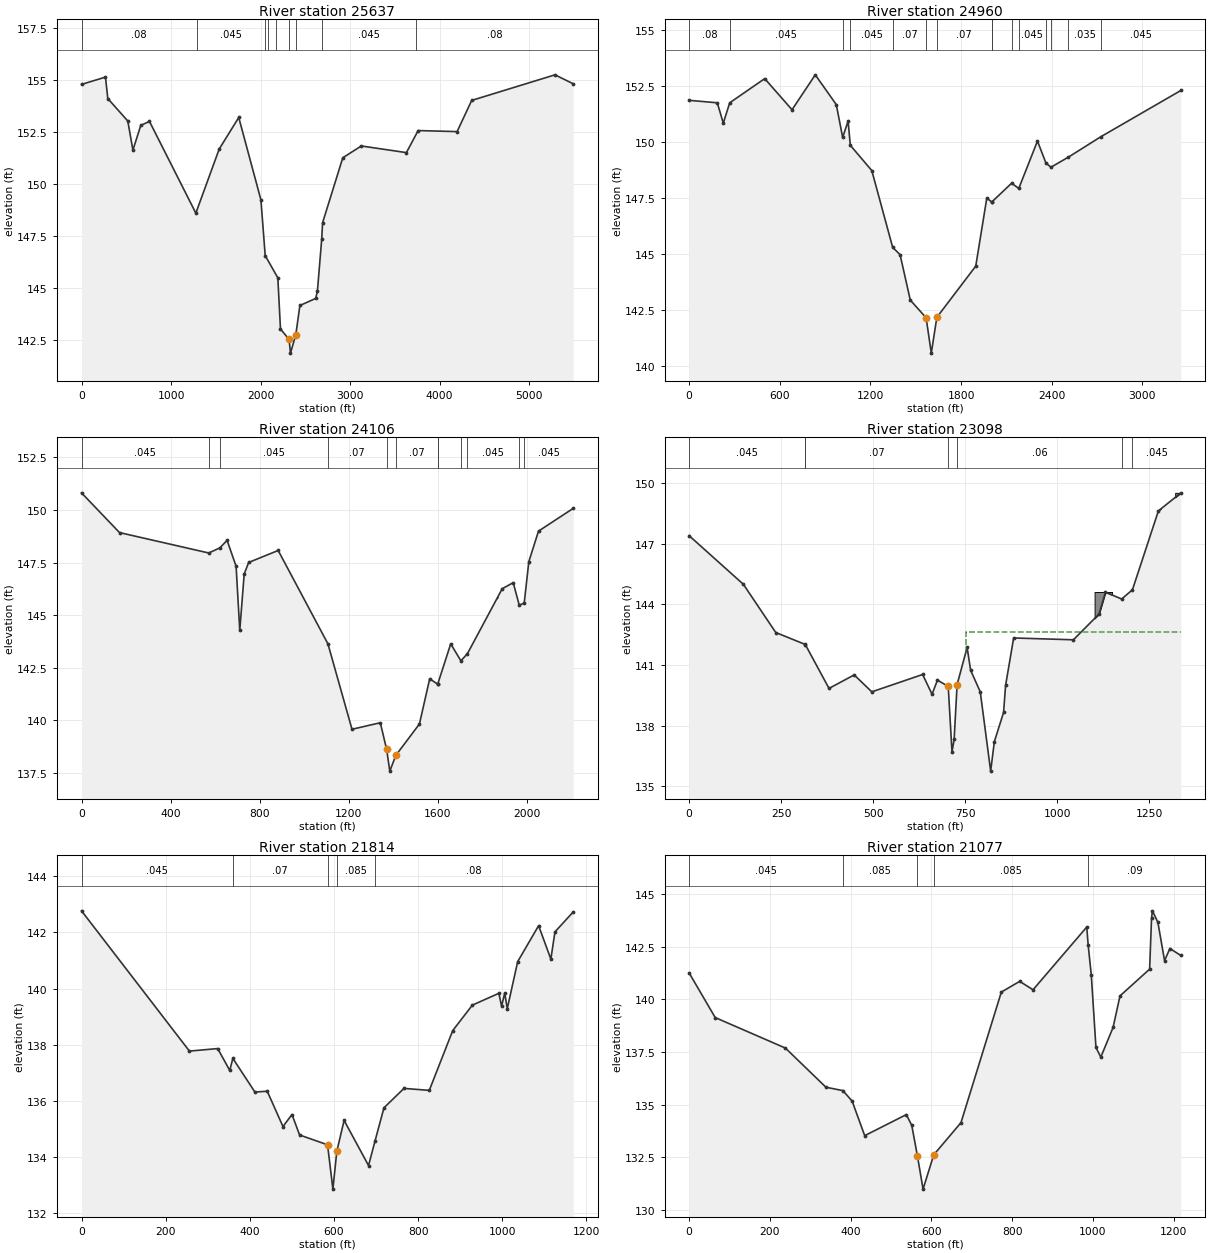
Type RM Length L Ch R = 1 ,25637   ,512.13,677.41,666.59
XS GIS Cut Line= 3
2305674.82592773747303.5778808592305305.33807376745099.504699707
2304694.99707034741900.031921402
#Sta/Elev= 30
       0  154.81  267.84  155.16  293.77  154.13  517.03  153.05  574.36  151.65
   662.1  152.84  759.16  153.03 1277.21  148.62 1537.92   151.7 1756.38  153.22
 2003.98  149.26 2051.81  146.58 2192.92  145.51 2222.56  143.05 2318.81  142.55
  2334.2  141.89 2393.48  142.77 2439.41  144.18 2615.99  144.52 2635.29  144.88
 2683.39  147.39 2692.86  148.16 2918.42  151.28 3125.19  151.85 3629.16  151.53
 3760.02  152.59 4195.34  152.54 4358.46  154.04  5288.5  155.27    5492  154.84
#Mann= 9 ,-1 , 0
       0     .08       0 1288.42    .045       0 2051.81    .045       0
 2080.37    .045       0 2175.38     .07       0 2318.81     .05       0
 2393.48     .07       0 2683.39    .045       0 3730.71     .08       0
Bank Sta=2318.81,2393.48
XS Rating Curve= 0 ,0
Exp/Cntr=0.3,0.1

Type RM Length L Ch R = 1 ,24960   ,887.85,853.88,737.85
BEGIN DESCRIPTION:
Survyed Section
END DESCRIPTION:
XS GIS Cut Line= 6
2306473.25189213746128.4074707032305781.43707274745136.812927261
2305780.04772952744803.9321289062305781.42028809744721.682312012
 2305812.6506958744370.5344848632305632.10632323743105.754699737
#Sta/Elev= 30
       0  151.87  186.29  151.76  226.08  150.85   268.5  151.76  500.21  152.84
  681.07  151.45  834.88  153.01  973.98  151.68 1016.07 150.213 1052.19  150.94
 1066.84  149.86 1209.08  148.73 1347.06   145.3 1396.25  144.971463.881  142.94
1568.563  142.15 1602.92  140.571639.593  142.17  1897.2  144.46 1970.22   147.5
  2002.2  147.33 2002.52  147.32 2134.66 148.167 2181.85  147.93 2305.61  150.05
  2361.5  149.07  2394.7  148.88 2510.23  149.33 2724.38  150.24 3254.55  152.31
#Mann= 15 ,-1 , 0
       0     .08       0   268.5    .045       0 1016.07    .045       0
 1066.84    .045       0 1347.06     .07       01568.563     .05       0
1639.593     .07       0  2002.2     .07       0 2002.52    .045       0
 2134.66    .035       0 2181.85    .045       0  2361.5    .035       0
  2394.7    .045       0 2510.23    .035       0 2724.38    .045       0
Bank Sta=1568.563,1639.593
XS Rating Curve= 0 ,0
Exp/Cntr=0.3,0.1

Type RM Length L Ch R = 1 ,24106   ,947.17,1007.13,889.09
XS GIS Cut Line= 4
2307163.94848633745800.1555175782306711.44952393744902.142272949
2306449.46508789 744212.250122072306329.64147948743762.258483902
#Sta/Elev= 30
       0  150.82  170.77  148.93  571.74  147.96  621.01   148.2  654.18  148.56
  694.63  147.33  711.13  144.28  730.98  146.96  751.05  147.51  883.67  148.08
 1107.26  143.64  1215.3  139.58 1342.57  139.89 1371.04  138.62 1385.27  137.59
 1412.35  138.34 1518.34  139.83  1564.5  141.98 1600.79  141.72 1601.23  141.75
 1658.93  143.64 1704.63 142.834 1733.79  143.17  1890.2  146.26 1939.75  146.55
 1966.86  145.48 1989.17  145.58 2009.93  147.55 2053.38     149 2209.21  150.08
#Mann= 12 ,-1 , 0
       0    .045       0  571.74    .045       0  621.01    .045       0
 1107.26     .07       0 1371.04     .05       0 1412.35     .07       0
 1600.79     .07       0 1601.23    .045       0 1704.63    .035       0
 1733.79    .045       0 1966.86    .035       0 1989.17    .045       0
#XS Ineff= 2 , 0
       0                    1450       0
Permanent Ineff=
       F       F
#Block Obstruct= 1 ,-1
 1866.76 1872.71145.8678
Bank Sta=1371.04,1412.35
XS Rating Curve= 0 ,0
Exp/Cntr=0.3,0.1

Type RM Length L Ch R = 1 ,23098   ,1004.05,1251.92,1105.19
XS GIS Cut Line= 2
2307758.90509035744644.4354858552306972.46832278 743563.93951416
#Sta/Elev= 30
       0  147.41  147.42     145   235.5  142.61  315.52  142.02  315.66142.0162
  380.19  139.84  448.64  140.51  496.44  139.67  634.67  140.53  660.18  139.55
  674.92  140.25  704.18  139.94  714.43  136.69  720.26  137.31  728.34  140.03
  755.54  141.87  765.06  140.74  791.25  139.67  819.52  135.74  829.56   137.2
  854.63  138.65   860.1  139.99  882.01  142.34 1044.45  142.25 1114.18  143.53
 1131.63  144.61 1175.49  144.27 1204.89  144.73 1275.47  148.64  1336.4  149.53
#Mann= 7 ,-1 , 0
       0    .045       0  315.52       0       0  315.66     .07       0
  704.18     .05       0  728.34     .06       0 1175.49    .035       0
 1204.89    .045       0
#XS Ineff= 2 , 0
                          751.71          142.64
Permanent Ineff=
       F       F
#Block Obstruct= 3 ,-1
 1101.99 1149.52144.6207 1279.26 1281.87148.7446 1321.02  1336.4149.5346
Bank Sta=704.18,728.34
XS Rating Curve= 0 ,0
Exp/Cntr=0.3,0.1

Type RM Length L Ch R = 1 ,21814   ,681.79,736.89,690.04
XS GIS Cut Line= 2
2308394.89312746744056.3175048832307984.57830814742962.144470215
#Sta/Elev= 30
       0  142.77  256.49  137.77  323.71  137.86  352.38  137.08  359.69  137.51
  412.16  136.31  441.42  136.34  478.83  135.08  500.24  135.51  518.35  134.78
  584.76  134.43  597.47  132.85  606.84   134.2   624.1   135.3  682.21  133.69
  697.52  134.56  718.86  135.75  766.45  136.44  826.57  136.37  882.26   138.5
  929.02  139.41  991.96  139.83  998.42  139.37 1005.93  139.84 1011.85  139.28
 1036.69  140.96  1086.4  142.24 1115.49  141.05 1125.26  142.02 1168.58  142.73
#Mann= 5 ,-1 , 0
       0    .045       0  359.69     .07       0  584.76     .05       0
  606.84    .085       0  697.52     .08       0
#XS Ineff= 2 , 0
       0                     660       0
Permanent Ineff=
       F       F
Bank Sta=584.76,606.84
XS Rating Curve= 0 ,0
Exp/Cntr=0.3,0.1

Type RM Length L Ch R = 1 ,21077   ,1048.2,1070.21,1034.83
XS GIS Cut Line= 3
2309053.67759183743927.9413204192308768.62436004743126.438703954
2308473.51042594742908.456820801
#Sta/Elev= 30
       0  141.25   64.52  139.13  238.48  137.68  338.74  135.82  380.74  135.66
  403.63  135.16  434.76  133.52  537.81  134.52  551.26  134.01  565.44  132.54
  579.27  130.98  605.75  132.61  673.19  134.14  773.06  140.34  818.57  140.85
  851.59  140.45  984.62  143.43  988.18  142.56  995.82  141.16 1007.39  137.71
 1019.39  137.25 1049.78  138.66 1066.96  140.16  1140.3  141.43 1145.04  143.85
 1147.33   144.2 1160.79  143.65 1177.29  141.83 1190.39  142.41 1217.57  142.08
#Mann= 5 ,-1 , 0
       0    .045       0  380.74    .085       0  565.44     .05       0
  605.75    .085       0  988.18     .09       0
Bank Sta=565.44,605.75
XS Rating Curve= 0 ,0
Exp/Cntr=0.3,0.1

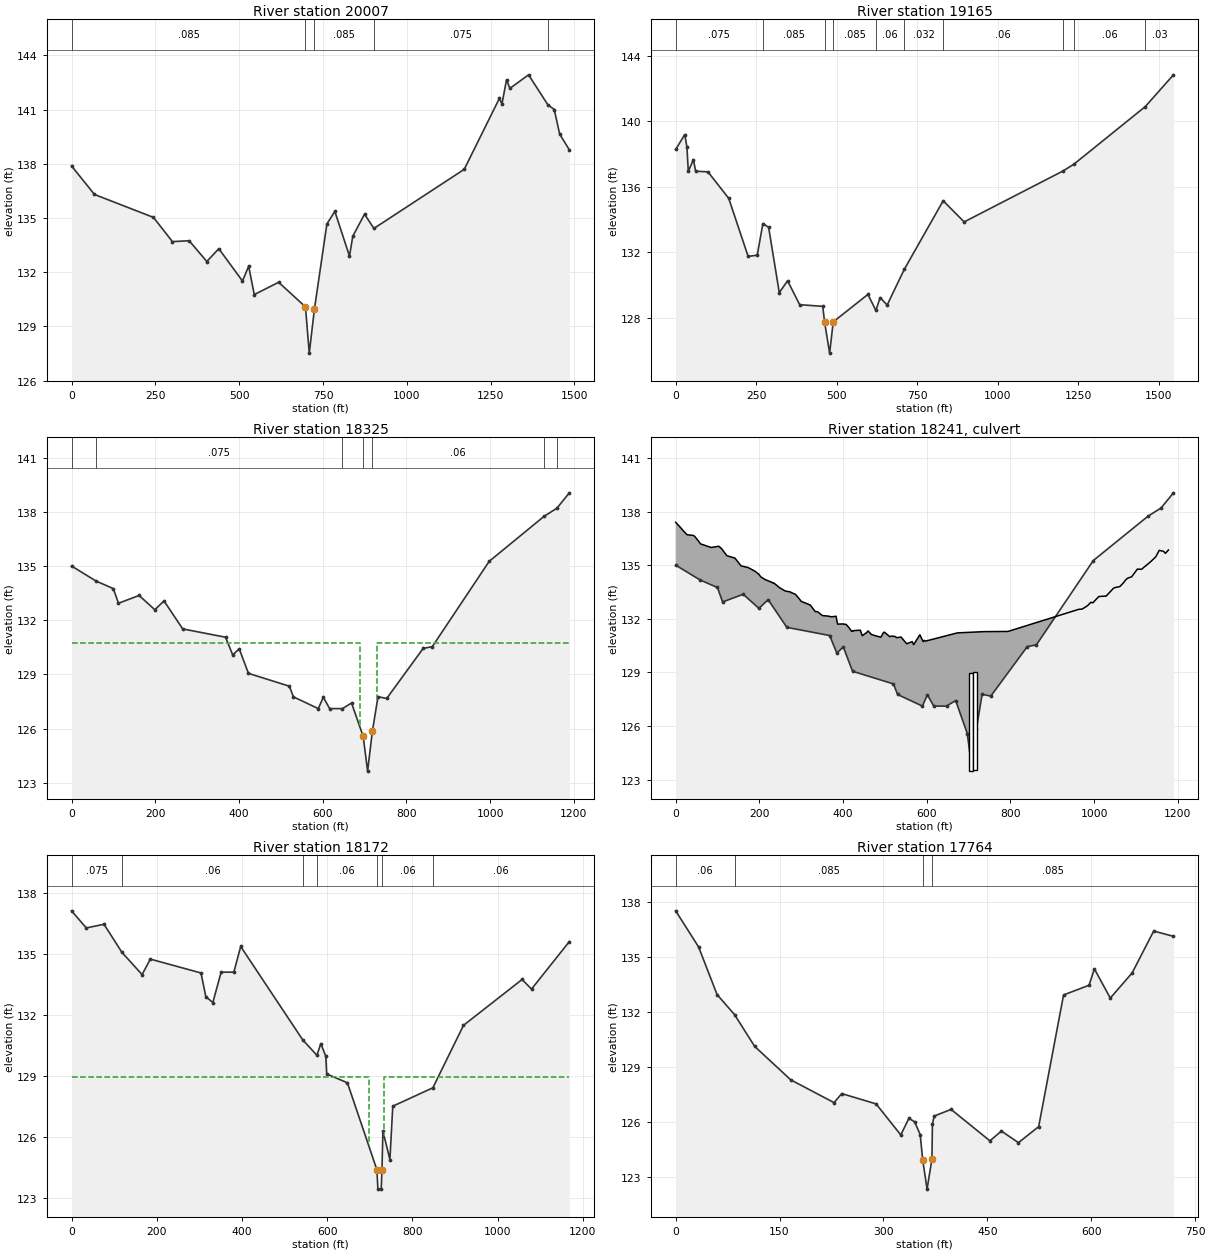
Type RM Length L Ch R = 1 ,20007   ,792.24,842.03,787.67
XS GIS Cut Line= 2
2310082.06086892743625.1138055772309513.50831176 742253.36795336
#Sta/Elev= 30
       0  137.88   68.36   136.3  244.36  135.03  300.94  133.69  350.94  133.74
  403.48  132.59  439.25   133.3  509.86  131.51  528.36  132.33  545.03  130.76
  617.79  131.44   697.8  130.08  709.07  127.52  724.58  129.97  761.73  134.67
  785.42  135.36  829.07  132.89  838.94  133.99  873.95  135.21  901.93  134.42
 1171.37  137.69 1276.34  141.62 1283.92  141.31 1297.58  142.65 1307.51  142.17
 1363.29  142.92  1420.9  141.26 1439.94     141 1456.04  139.64  1484.9  138.77
#Mann= 5 ,-1 , 0
       0    .085       0   697.8     .05       0  724.58    .085       0
  901.93    .075       0  1420.9    .045       0
Bank Sta=697.8,724.58
XS Rating Curve= 0 ,0
Exp/Cntr=0.3,0.1

Type RM Length L Ch R = 1 ,19165   ,725.78,839.62,874.53
XS GIS Cut Line= 2
2310769.98453049743197.1861896812310134.02464968 741788.46110487
#Sta/Elev= 30
       0  138.28    28.3  139.19   34.96  138.42   39.24  136.94   55.02  137.66
   61.95  136.95  100.27  136.91  164.71  135.29     225  131.74  253.29  131.82
  270.79  133.75  288.64  133.52  321.68  129.53  347.51  130.25  385.05  128.79
  456.63  128.69  462.38  127.72  478.01  125.83  489.16  127.74  596.85  129.42
  621.49  128.44  634.78  129.22  656.59  128.77  709.75  130.95  830.46  135.14
  895.66  133.85 1201.26  136.95 1235.88  137.37 1457.99   140.9 1545.41  142.84
#Mann= 10 ,-1 , 0
       0    .075       0  270.79    .085       0  462.38     .05       0
  489.16    .085       0  621.49     .06       0  709.75    .032       0
  830.46     .06       0 1201.26     .03       0 1235.88     .06       0
 1457.99     .03       0
#XS Ineff= 2 , 0
       0     385             595       0
Permanent Ineff=
       F       F
Bank Sta=462.38,489.16
XS Rating Curve= 0 ,0
Exp/Cntr=0.5,0.3

Type RM Length L Ch R = 1 ,18325   ,161.89,152.65,163.37
BEGIN DESCRIPTION:
Surveyed Section
END DESCRIPTION:
XS GIS Cut Line= 6
 2311272.1708014743113.983656421 2311337.5160162742487.296278492
2311346.07723452742443.1839127542311347.92782044742415.025465488
 2311337.5088141 742391.991102712311375.27295154741933.594569772
#Sta/Elev= 30
       0     135    58.4  134.17   99.74  133.75  112.13  132.94   161.4  133.37
     199  132.58  220.93  133.07  265.56  131.52  367.99  131.06  385.04  130.08
  400.57  130.42  422.65  129.06   520.4  128.35  530.18  127.76  589.54  127.11
  601.53  127.74  616.62  127.11  647.25  127.11  668.98  127.42  696.85  125.57
  707.37  123.65  718.73  125.85  732.21  127.77     753  127.67  840.08  130.44
  861.91  130.54  997.89  135.26 1129.06  137.75 1159.75   138.2 1189.37  139.05
#Mann= 7 ,-1 , 0
       0    .045       0    58.4    .075       0  647.25    .085       0
  696.85     .05       0  718.73     .06       0 1129.06     .03       0
 1159.75    .045       0
#XS Ineff= 2 , 0
       0     690  130.72     731       0  130.72
Permanent Ineff=
       F       F
Bank Sta=696.85,718.73
XS Rating Curve= 0 ,0
Exp/Cntr=0.5,0.3

Type RM Length L Ch R = 2 ,18241   ,,,
BEGIN DESCRIPTION:
2 Box Culverts at Nash St.
END DESCRIPTION:
Bridge Culvert--1,0,-1,-1, 0
Deck Dist Width WeirC Skew NumUp NumDn MinLoCord MaxHiCord MaxSubmerge Is_Ogee
30,70,2.6,0, 123, 123, , , 0.98, 0, 1,1,,
       0   12.31   17.22   27.46   40.93    42.5   45.28   53.81   59.56   67.27
    74.4   84.64   95.53  103.02  109.63  122.26  141.09  141.33  141.49  156.19
  156.26  172.74  188.21  189.21  190.27  198.76  203.21  213.12  229.68  232.47
  234.14  240.97  246.96  248.03  248.92  262.18  274.59  276.15  278.06  286.05
  290.84  300.29  318.34  320.18  321.13  323.21  333.48  336.69  339.29  350.31
  363.92  363.92  363.93  363.94  372.65  383.23  386.84  399.08  402.39  403.11
     407  415.21  420.28  422.95  423.54  426.36  441.22  445.81  456.35  459.69
  466.89  467.94  469.08  478.44  481.81  490.32  496.64  498.64  511.49  516.28
  523.52  528.46  538.35  546.59  552.03   565.1  568.64  583.29  583.42  591.57
  594.46  597.23 673.136 737.054 793.992  963.38  971.16  984.02  991.95  996.68
 1010.78  1014.2 1028.58 1041.83 1046.08  1050.6 1061.18 1069.15 1075.46 1079.87
 1089.53 1103.21 1103.36 1103.59 1113.33 1119.68 1127.14 1136.56 1147.17 1155.37
 1166.04 1170.04 1177.42
   137.4  137.09  136.95   136.7  136.67  136.66  136.62  136.37  136.19  136.13
  136.07  135.99  136.03  136.06  135.93  135.53   135.4   135.4   135.4  134.96
  134.96  134.87  134.68  134.66  134.65  134.49  134.35   134.2  134.04     134
  134.01  133.88  133.76  133.74  133.73  133.55   133.5  133.45  133.45  133.37
  133.24  132.97   132.8  132.77  132.78  132.72   132.4   132.4  132.39  132.18
  132.15  132.15  132.15  132.15  132.11  132.14   131.7  131.71   131.7  131.69
  131.69  131.47   131.3  131.32   131.3  131.34  131.36  131.05  131.23  131.32
  131.14  131.11  131.11  131.04  131.02  130.97  131.23  131.25     131  131.03
  131.01  130.94  130.98  130.75   130.6  130.72  130.55   131.1   131.1  130.72
  130.79  130.75  131.21  131.28  131.29  132.53  132.54  132.73  132.92  132.89
  133.24  133.25  133.27   133.6  133.71  133.75   133.8  133.99  134.18  134.27
  134.35  134.78  134.78  134.78  134.77   134.9  135.04  135.23  135.47  135.83
  135.77  135.66  135.85
                                                                                
                                                                                
                                                                                
                                                                                
                                                                                
                                                                                
                                                                                
                                                                                
                                                                                
                                                                                
                                                                                
                                                                                
                        
       0   12.31   17.22   27.46   40.93    42.5   45.28   53.81   59.56   67.27
    74.4   84.64   95.53  103.02  109.63  122.26  141.09  141.33  141.49  156.19
  156.26  172.74  188.21  189.21  190.27  198.76  203.21  213.12  229.68  232.47
  234.14  240.97  246.96  248.03  248.92  262.18  274.59  276.15  278.06  286.05
  290.84  300.29  318.34  320.18  321.13  323.21  333.48  336.69  339.29  350.31
  363.92  363.92  363.93  363.94  372.65  383.23  386.84  399.08  402.39  403.11
     407  415.21  420.28  422.95  423.54  426.36  441.22  445.81  456.35  459.69
  466.89  467.94  469.08  478.44  481.81  490.32  496.64  498.64  511.49  516.28
  523.52  528.46  538.35  546.59  552.03   565.1  568.64  583.29  583.42  591.57
  594.46  597.23 673.136 737.054 793.992  963.38  971.16  984.02  991.95  996.68
 1010.78  1014.2 1028.58 1041.83 1046.08  1050.6 1061.18 1069.15 1075.46 1079.87
 1089.53 1103.21 1103.36 1103.59 1113.33 1119.68 1127.14 1136.56 1147.17 1155.37
 1166.04 1170.04 1177.42
   137.4  137.09  136.95   136.7  136.67  136.66  136.62  136.37  136.19  136.13
  136.07  135.99  136.03  136.06  135.93  135.53   135.4   135.4   135.4  134.96
  134.96  134.87  134.68  134.66  134.65  134.49  134.35   134.2  134.04     134
  134.01  133.88  133.76  133.74  133.73  133.55   133.5  133.45  133.45  133.37
  133.24  132.97   132.8  132.77  132.78  132.72   132.4   132.4  132.39  132.18
  132.15  132.15  132.15  132.15  132.11  132.14   131.7  131.71   131.7  131.69
  131.69  131.47   131.3  131.32   131.3  131.34  131.36  131.05  131.23  131.32
  131.14  131.11  131.11  131.04  131.02  130.97  131.23  131.25     131  131.03
  131.01  130.94  130.98  130.75   130.6  130.72  130.55   131.1   131.1  130.72
  130.79  130.75  131.21  131.28  131.29  132.53  132.54  132.73  132.92  132.89
  133.24  133.25  133.27   133.6  133.71  133.75   133.8  133.99  134.18  134.27
  134.35  134.78  134.78  134.78  134.77   134.9  135.04  135.23  135.47  135.83
  135.77  135.66  135.85
                                                                                
                                                                                
                                                                                
                                                                                
                                                                                
                                                                                
                                                                                
                                                                                
                                                                                
                                                                                
                                                                                
                                                                                
                        
BR Coef=-1 , 0 , 0 ,, 0 ,,,0.8,0,,0,
WSPro=,,,, 1 ,,,, 0 ,,,, 0 ,,,,-1 ,-1 ,-1 , 0 , 0 , 0 , 0 , 0
Culvert=2,5.5,8,95,0.013,0.5,1,8,1,123.47,706,123.44,711,Culvert #2  , 0 ,17
Culvert Bottom n=0.013
Culvert=2,5.5,8,95,0.013,0.5,1,8,1,123.54,715,123.46,720,Culvert #1  , 0 ,17
Culvert Bottom n=0.013
BC Design=,, 0 ,, 0 ,,,,,,
BC Use User HTab Curves=0
BC User HTab FreeFlow(D)= 0

Type RM Length L Ch R = 1 ,18172   ,484.88,408.65,350.85
BEGIN DESCRIPTION:
Survyed Section
END DESCRIPTION:
XS GIS Cut Line= 6
2311403.84669319743107.4991220242311464.31689456742511.629882813
 2311468.0200806742411.0656738432311473.95550537742390.232116714
2311480.60168459742310.8040771482311506.23593403741945.500295445
#Sta/Elev= 30
       0  137.12   34.57  136.28   76.13  136.46  118.34  135.08  165.53  133.99
  184.85  134.75  303.77  134.07  315.22   132.9  331.61  132.62  351.03  134.11
  380.87  134.11  396.94  135.37  542.41  130.79  575.82  130.03  584.93   130.6
  596.57  129.99 598.811  129.11  647.39  128.68 716.598  124.41  718.89  123.47
  726.72  123.46  728.46   124.4 730.733  126.31 747.124  124.91 753.868  127.53
   847.9128.4328  919.84   131.5 1057.32  133.75 1079.49  133.28 1168.23  135.61
#Mann= 7 ,-1 , 0
       0    .075       0  118.34     .06       0  542.41    .035       0
  575.82     .06       0 716.598     .05       0  728.46     .06       0
   847.9     .06       0
#XS Ineff= 2 , 0
       0     697  128.94     734       0  128.96
Permanent Ineff=
       F       F
Bank Sta=716.598,728.46
XS Rating Curve= 0 ,0
Exp/Cntr=0.5,0.3

Type RM Length L Ch R = 1 ,17764   ,311.4,283.6,275.19
XS GIS Cut Line= 2
2311968.35009767742550.5247192382311712.38708498741878.895324722
#Sta/Elev= 30
       0   137.5   33.15  135.53   59.78  132.94   85.03  131.85  114.07  130.12
  166.14   128.3  228.64  127.06  239.83  127.55  289.39  126.99  325.05   125.3
  336.83  126.21  345.07  126.01  353.07  125.32  356.65  123.95     363  122.35
  370.04  123.99  370.73   125.9  373.36  126.33  397.67  126.69  453.74  124.98
  470.34  125.51  494.95  124.88  524.12  125.75  560.08  132.92  596.94  133.45
  604.59  134.34  627.57  132.75   659.1  134.12  690.25   136.4  718.75  136.11
#Mann= 4 ,-1 , 0
       0     .06       0   85.03    .085       0  356.65     .05       0
  370.04    .085       0
Bank Sta=356.65,370.04
XS Rating Curve= 0 ,0
Exp/Cntr=0.5,0.3

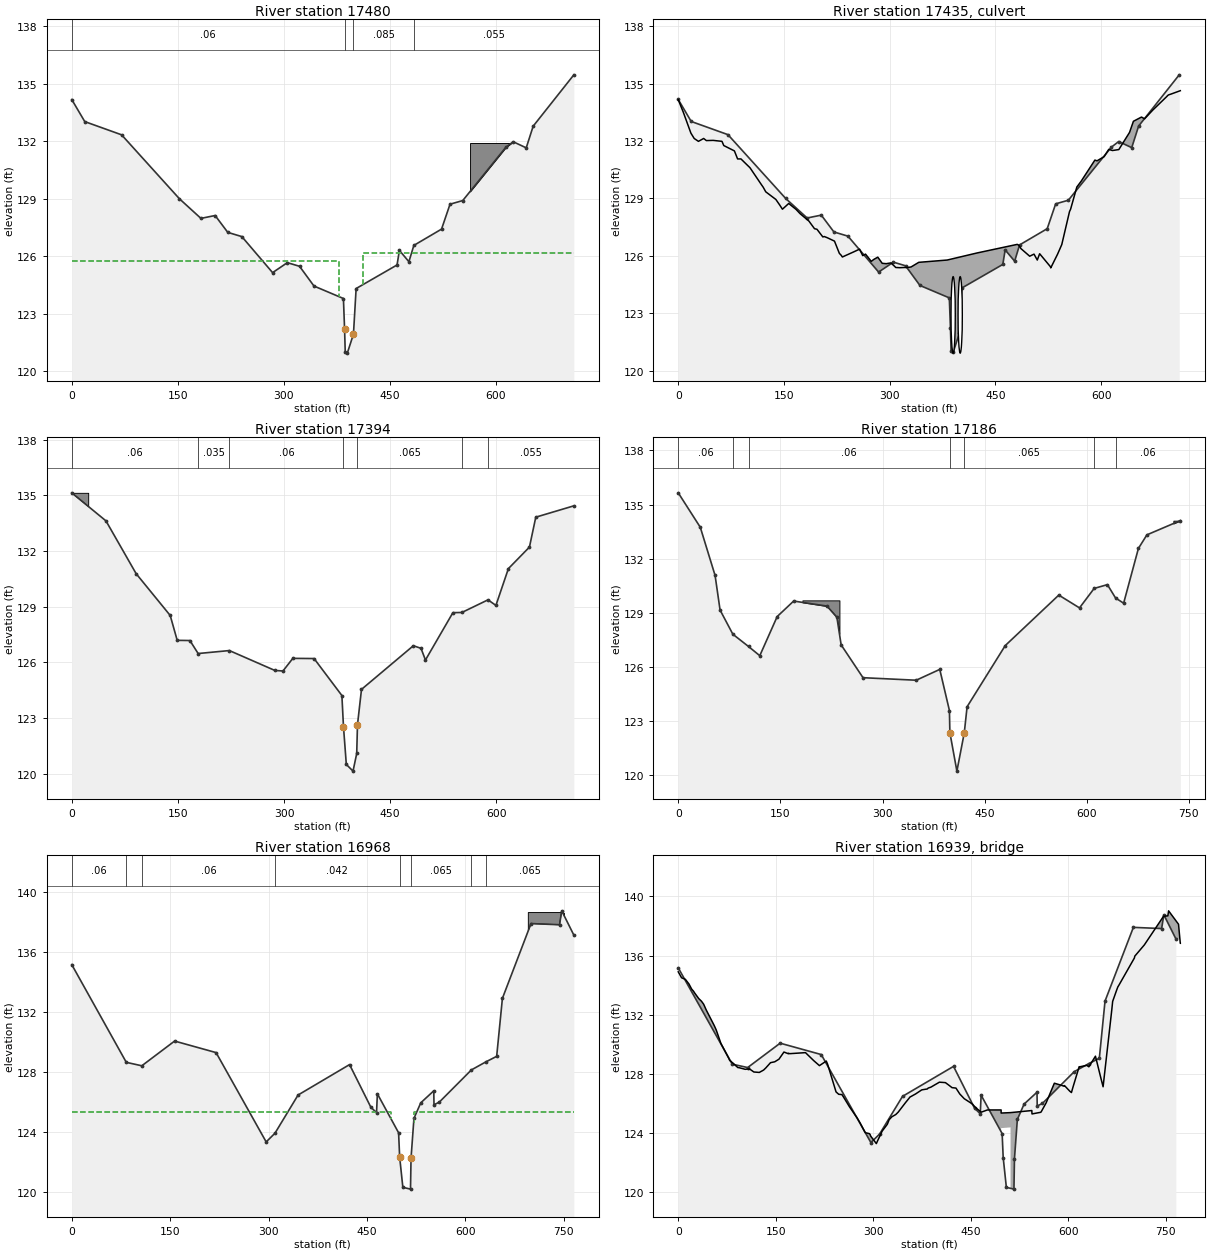
Type RM Length L Ch R = 1 ,17480   ,86.1,85.89,90.25
BEGIN DESCRIPTION:
Survyed Section
END DESCRIPTION:
XS GIS Cut Line= 6
  2312310.151458742417.4693052772312120.52392581742131.953918472
2312092.63867189742094.1616821292312087.20367432742083.204284683
2312067.24829102742028.8389282382311955.54685968741804.696486577
#Sta/Elev= 30
       0  134.18   18.39  133.03   70.53  132.34  152.48     129  182.85  127.98
  202.95  128.13  220.84  127.25  240.74  127.03  284.27  125.15   305.2  125.67
  322.44  125.48 342.876  124.45 384.556   123.8 386.164  122.23 387.129     121
 390.046  120.95 398.756  121.94 402.541  124.32 460.474  125.55  463.78  126.31
  477.26  125.72  484.23  126.57  523.45  127.42  535.46  128.72  553.46  128.91
  614.27  131.68  624.83  131.98  643.35  131.66  653.15  132.79  710.74  135.47
#Mann= 4 ,-1 , 0
       0     .06       0 386.164     .05       0 398.756    .085       0
  484.23    .055       0
#XS Ineff= 2 , 0
       0     378  125.78     412       0  126.15
Permanent Ineff=
       F       F
#Block Obstruct= 1 ,-1
  563.83  622.45131.9118
Bank Sta=386.164,398.756
XS Rating Curve= 0 ,0
Exp/Cntr=0.5,0.3

Type RM Length L Ch R = 2 ,17435   ,,,
Bridge Culvert--1,0,-1,-1, 0
Deck Dist Width WeirC Skew NumUp NumDn MinLoCord MaxHiCord MaxSubmerge Is_Ogee
32,24,2.6,0, 89, 89, , , 0.98, 0, 1,1,,
       0    7.02   17.96   22.64   28.64   36.06   39.89   49.53   62.04    64.6
   79.68    84.2   88.99   94.24  101.76  118.44  120.53  124.14  138.48  143.76
  147.82  156.76  167.13  172.76  185.36  193.31   196.8  205.11  207.15   211.3
  221.65  228.57  229.59  231.17  232.87   248.5  257.25  261.76  265.65  271.11
  273.71  277.77  283.11  287.97   289.3  295.01  301.72  307.26  308.55  314.23
  327.32   330.4  341.18 381.483 423.856  480.94  482.94   483.6  486.13   498.6
  504.72  509.35  512.72  527.58  528.06  528.48  538.18  544.11  555.11  556.63
  565.46  571.53  583.88  591.09  594.11  604.24  610.74  616.02  625.05  640.27
  645.74  657.15   661.6  673.33  693.48   694.1  695.55  698.84  712.27
  134.17  133.53  132.42  132.14  131.99  132.14  132.03  132.04  131.99  131.77
  131.49  131.07  131.07  130.88  130.61   129.7  129.59  129.35  128.95  128.67
  128.44  128.74  128.43  128.21  127.82  127.42  127.39  126.99  127.01  126.95
  126.77  126.13  126.09  126.03  125.94   126.2  126.35  126.01  126.09  125.84
  125.71  125.82  125.93  125.68  125.61  125.59  125.63  125.44  125.39  125.38
   125.4  125.42  125.66  125.78  126.15   126.6  126.56  126.53  126.38  125.98
  126.09  125.78  126.11  125.45  125.43  125.37  126.09  126.59  128.32  128.44
   129.6   129.9   130.6  131.01  130.97  131.19  131.57  131.51  131.56  132.46
  133.04  133.26  133.17  133.63  134.35  134.38  134.42  134.46  134.64
                                                                                
                                                                                
                                                                                
                                                                                
                                                                                
                                                                                
                                                                                
                                                                                
                                                                        
       0    7.02   17.96   22.64   28.64   36.06   39.89   49.53   62.04    64.6
   79.68    84.2   88.99   94.24  101.76  118.44  120.53  124.14  138.48  143.76
  147.82  156.76  167.13  172.76  185.36  193.31   196.8  205.11  207.15   211.3
  221.65  228.57  229.59  231.17  232.87   248.5  257.25  261.76  265.65  271.11
  273.71  277.77  283.11  287.97   289.3  295.01  301.72  307.26  308.55  314.23
  327.32   330.4  341.18 381.483 423.856  480.94  482.94   483.6  486.13   498.6
  504.72  509.35  512.72  527.58  528.06  528.48  538.18  544.11  555.11  556.63
  565.46  571.53  583.88  591.09  594.11  604.24  610.74  616.02  625.05  640.27
  645.74  657.15   661.6  673.33  693.48   694.1  695.55  698.84  712.27
  134.17  133.53  132.42  132.14  131.99  132.14  132.03  132.04  131.99  131.77
  131.49  131.07  131.07  130.88  130.61   129.7  129.59  129.35  128.95  128.67
  128.44  128.74  128.43  128.21  127.82  127.42  127.39  126.99  127.01  126.95
  126.77  126.13  126.09  126.03  125.94   126.2  126.35  126.01  126.09  125.84
  125.71  125.82  125.93  125.68  125.61  125.59  125.63  125.44  125.39  125.38
   125.4  125.42  125.66  125.78  126.15   126.6  126.56  126.53  126.38  125.98
  126.09  125.78  126.11  125.45  125.43  125.37  126.09  126.59  128.32  128.44
   129.6   129.9   130.6  131.01  130.97  131.19  131.57  131.51  131.56  132.46
  133.04  133.26  133.17  133.63  134.35  134.38  134.42  134.46  134.64
                                                                                
                                                                                
                                                                                
                                                                                
                                                                                
                                                                                
                                                                                
                                                                                
                                                                        
BR Coef=-1 , 0 , 0 ,, 0 ,,,0.8,-1,,0,
WSPro=,,,, 1 ,,,, 0 ,,,, 0 ,,,,-1 ,-1 ,-1 , 0 , 0 , 0 , 0 , 0
Multiple Barrel Culv=3,4,6.03,40,0.024,0.7,1,34,2,120.91,120.18, 2,Culvert #1  , 0 ,22
     390     387     400     397
Culvert Bottom n=0.024
BC Design=,, 0 ,, 0 ,,,,,,
BC Use User HTab Curves=0
BC User HTab FreeFlow(D)= 0

Type RM Length L Ch R = 1 ,17394   ,192.09,207.88,187.69
BEGIN DESCRIPTION:
Survyed Sections
END DESCRIPTION:
XS GIS Cut Line= 6
2312385.90570068742381.4149170072312198.79248051742094.722290054
2312163.42907716742045.996887222 2312160.2675171742040.066894546
2312149.97131349741994.4411010742312040.93323603741765.519207999
#Sta/Elev= 30
       0  135.13   48.34  133.62   90.96  130.78  139.13  128.53  149.04  127.19
  166.98  127.18  178.63  126.48  222.77  126.64  287.04  125.57  298.51  125.54
  312.47  126.22 342.505  126.21 381.802  124.22 384.068  122.54 388.073  120.51
  397.56  120.15 402.769   121.1 403.865  122.65 409.528  124.55  482.84   126.9
  493.66  126.76  499.92  126.13  538.73  128.68  551.42  128.69  588.33  129.37
  599.52  129.07  617.16  131.05  646.93  132.21  655.88  133.82  709.68  134.43
#Mann= 7 ,-1 , 0
       0     .06       0  178.63    .035       0  222.77     .06       0
 384.068     .05       0 403.865    .065       0  551.42    .035       0
  588.33    .055       0
#XS Ineff= 2 , 0
       0     375  124.09     409       0  124.09
Permanent Ineff=
       F       F
#Block Obstruct= 1 ,-1
       0   23.21135.1304
Bank Sta=384.068,403.865
XS Rating Curve= 0 ,0
Exp/Cntr=0.5,0.3

Type RM Length L Ch R = 1 ,17186   ,155.58,218.09,212.74
XS GIS Cut Line= 3
2312551.35809328742306.870483413 2312516.8131104742255.961914063
2312182.27191167741668.696716323
#Sta/Elev= 30
       0  135.65   32.39  133.74   54.12  131.07   61.45  129.15   80.23  127.81
  103.23  127.13  119.77  126.62  145.33  128.79  169.53  129.65  218.46  129.37
     233  128.75  239.27  127.22  271.37   125.4  349.49  125.26   384.1  125.86
  398.29  123.58  398.94  122.36  409.26  120.22  420.09  122.34  424.25  123.79
  480.25  127.18  558.92  129.98  589.34  129.27  610.85  130.35  630.31  130.56
  642.27  129.82  654.15  129.53  675.87  132.57  688.34  133.32  737.39  134.11
#Mann= 7 ,-1 , 0
       0     .06       0   80.23    .035       0  103.23     .06       0
  398.94     .05       0  420.09    .065       0  610.85    .035       0
  642.27     .06       0
#Block Obstruct= 2 ,-1
  182.38  236.74129.6882  727.21  737.39134.1069
Bank Sta=398.94,420.09
XS Rating Curve= 0 ,0
Exp/Cntr=0.5,0.3

Type RM Length L Ch R = 1 ,16968   ,61.08,58.31,55.03
BEGIN DESCRIPTION:
Survyed Sections
END DESCRIPTION:
XS GIS Cut Line= 6
2312665.76060197742279.8465574532312490.67907716 741847.77947998
2312487.17047118741813.9880981452312481.55712894741800.263916016
2312475.00372313741763.6909179842312384.48783274741570.637360737
#Sta/Elev= 30
       0  135.17   83.13  128.65  106.78  128.42  156.79  130.07  220.01   129.3
  296.38  123.34  309.78  123.92  345.03  126.47   423.5   128.5  455.92  125.66
  464.63  125.29 465.919  126.55 498.263  123.95 499.881  122.33  504.75  120.31
  516.44  120.19 517.226  122.25 521.671  124.91 532.079  125.95 551.905  126.75
  552.23  125.82   560.2  125.99  609.22128.1438  631.27  128.68  647.79  129.05
  656.54  132.92  700.15  137.91  743.61  137.83     747  138.76  765.45  137.14
#Mann= 8 ,-1 , 0
       0     .06       0   83.13    .035       0  106.78     .06       0
  309.78    .042       0 499.881    .032       0 517.226    .065       0
  609.22    .035       0  631.27    .065       0
#XS Ineff= 2 , 0
       0   486.7  125.34  521.21       0  125.34
Permanent Ineff=
       F       F
#Block Obstruct= 1 ,-1
  696.05   750.9138.6445
Bank Sta=499.881,517.226
XS Rating Curve= 0 ,0
Exp/Cntr=0.5,0.3

Type RM Length L Ch R = 3 ,16939   ,,,
BEGIN DESCRIPTION:
Concrete Golf Cart Path next to St. Andrews Drive
END DESCRIPTION:
Bridge Culvert--1,0,-1,-1, 0
Deck Dist Width WeirC Skew NumUp NumDn MinLoCord MaxHiCord MaxSubmerge Is_Ogee
25,10,2.6,0, 125, 125, , , 0.98, 0, 1,1,,
       0    5.12   11.02   16.61   20.67   23.49   25.41   31.52   35.76   39.08
   43.15   55.42   57.68   58.55   65.58   77.67   79.18   80.55    91.7   93.73
  103.13   107.8  108.79  109.88  116.32  124.68   131.3  134.61  141.94  148.46
     155  162.59  169.13  169.63  169.93  171.39  195.74  208.62  217.22  227.74
  229.75  242.77  246.89  251.82  254.88  263.32  272.18  274.94  279.75  287.68
  292.87  293.82  295.05  296.05  301.68  304.72  306.44  313.59  321.63  324.43
  328.69  334.65  338.34  349.69  354.68   356.4  365.01  374.65  375.98  383.15
  384.43  388.49  401.78     411  416.18   421.2  427.23  433.12  440.02  449.48
  452.82  458.16  466.15 475.573   496.7 496.703 511.214  511.25  543.94  544.18
  554.94  556.59  558.17  566.05  578.58  588.63  593.23  594.18  602.53  604.51
  604.88  607.01  616.75  617.48  628.51  631.66  641.81   650.7  653.57  666.94
  668.28  674.56  676.34  676.74  678.07  692.81  701.74  702.29  716.96  746.51
  753.15  754.31  769.62  772.33  772.35
   134.9   134.5  134.39  134.07  133.73  133.59  133.46  133.09  132.91  132.71
  132.31  131.26  131.04  130.95  130.06  129.05   128.9  128.86  128.42  128.41
   128.3  128.33  128.29  128.32  128.12  128.09  128.25  128.39  128.75  128.81
  128.99  129.47  129.36  129.39  129.37  129.36  129.43  128.88  128.55  128.86
  128.65  126.77  126.61  126.59  126.38  125.77   125.2  125.03  124.67  124.01
  123.96  123.95   123.9  123.78  123.45  123.27  123.44  124.11  124.58  124.89
  125.09  125.24   125.4  126.05  126.32  126.42  126.63  126.91  126.92  126.97
  127.03  127.09  127.43   127.4  127.23  127.06  127.03  126.63  126.31  126.04
  125.93  125.68   125.4  125.55  125.55  125.34  125.37  125.37  125.51  125.28
  125.37  125.38  125.41  126.04  127.36  127.23  127.16   127.2  126.81  126.75
  126.73  127.06  128.48  128.47  128.57  128.47  129.19  127.61  127.12  132.33
   132.9  133.68  133.89  133.91  134.01  135.15  135.84  135.96  136.72  138.66
  138.69  139.03  138.12  136.83  136.83
                                                                                
                                                                                
                                                                                
                                                                                
                                                                                
                                                                                
                                                                                
                                                                                
                                          124.32  124.37
                                                                                
                                                                                
                                                                                
                                        
       0    5.12   11.02   16.61   20.67   23.49   25.41   31.52   35.76   39.08
   43.15   55.42   57.68   58.55   65.58   77.67   79.18   80.55    91.7   93.73
  103.13   107.8  108.79  109.88  116.32  124.68   131.3  134.61  141.94  148.46
     155  162.59  169.13  169.63  169.93  171.39  195.74  208.62  217.22  227.74
  229.75  242.77  246.89  251.82  254.88  263.32  272.18  274.94  279.75  287.68
  292.87  293.82  295.05  296.05  301.68  304.72  306.44  313.59  321.63  324.43
  328.69  334.65  338.34  349.69  354.68   356.4  365.01  374.65  375.98  383.15
  384.43  388.49  401.78     411  416.18   421.2  427.23  433.12  440.02  449.48
  452.82  458.16  466.15 475.573   496.7 496.703 511.214  511.25  543.94  544.18
  554.94  556.59  558.17  566.05  578.58  588.63  593.23  594.18  602.53  604.51
  604.88  607.01  616.75  617.48  628.51  631.66  641.81   650.7  653.57  666.94
  668.28  674.56  676.34  676.74  678.07  692.81  701.74  702.29  716.96  746.51
  753.15  754.31  769.62  772.33  772.35
   134.9   134.5  134.39  134.07  133.73  133.59  133.46  133.09  132.91  132.71
  132.31  131.26  131.04  130.95  130.06  129.05   128.9  128.86  128.42  128.41
   128.3  128.33  128.29  128.32  128.12  128.09  128.25  128.39  128.75  128.81
  128.99  129.47  129.36  129.39  129.37  129.36  129.43  128.88  128.55  128.86
  128.65  126.77  126.61  126.59  126.38  125.77   125.2  125.03  124.67  124.01
  123.96  123.95   123.9  123.78  123.45  123.27  123.44  124.11  124.58  124.89
  125.09  125.24   125.4  126.05  126.32  126.42  126.63  126.91  126.92  126.97
  127.03  127.09  127.43   127.4  127.23  127.06  127.03  126.63  126.31  126.04
  125.93  125.68   125.4  125.55  125.55  125.34  125.37  125.37  125.51  125.28
  125.37  125.38  125.41  126.04  127.36  127.23  127.16   127.2  126.81  126.75
  126.73  127.06  128.48  128.47  128.57  128.47  129.19  127.61  127.12  132.33
   132.9  133.68  133.89  133.91  134.01  135.15  135.84  135.96  136.72  138.66
  138.69  139.03  138.12  136.83  136.83
                                                                                
                                                                                
                                                                                
                                                                                
                                                                                
                                                                                
                                                                                
                                                                                
                                          124.32  124.37
                                                                                
                                                                                
                                                                                
                                        
BR Coef=-1 , 0 , 0 ,, 0 ,,,0.8,0,,0,
WSPro=,,,, 1 ,,,, 0 ,,,, 0 ,,,,-1 ,-1 ,-1 , 0 , 0 , 0 , 0 , 0
BC Design=,, 0 ,, 0 ,,,,,,
BC Use User HTab Curves=0
BC User HTab FreeFlow(D)= 0