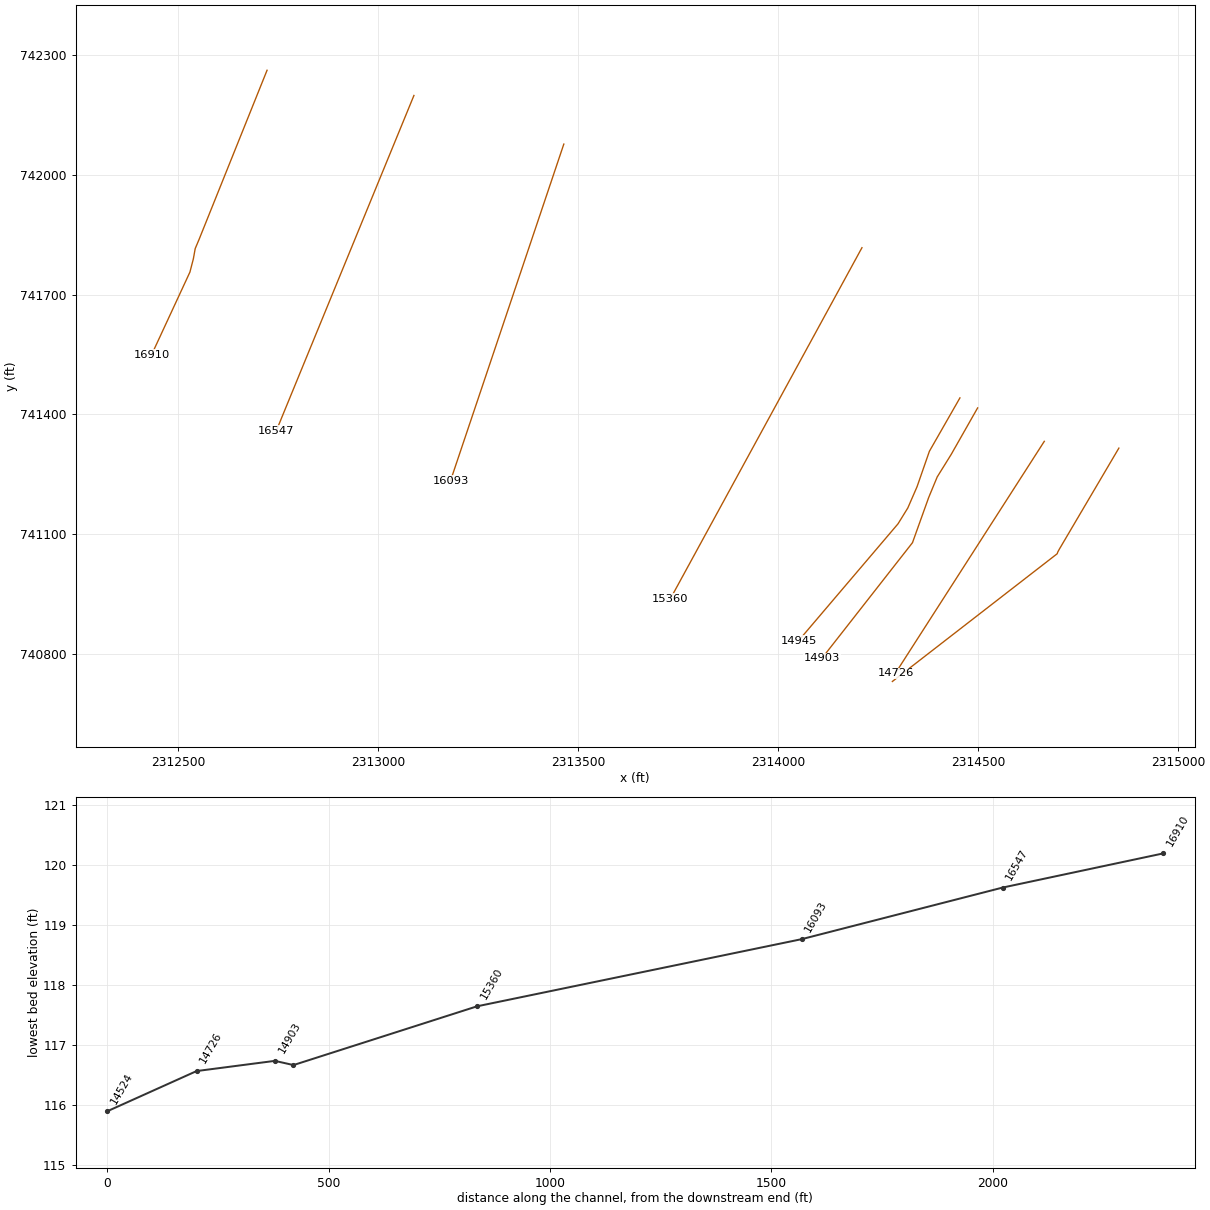
HEC-RAS study dtl_toisnot_swp_tri.prj: dtl_toisnot_swp_trib

--- dtl_toisnot_swp_tri.g01 (geometry) --- (continued)

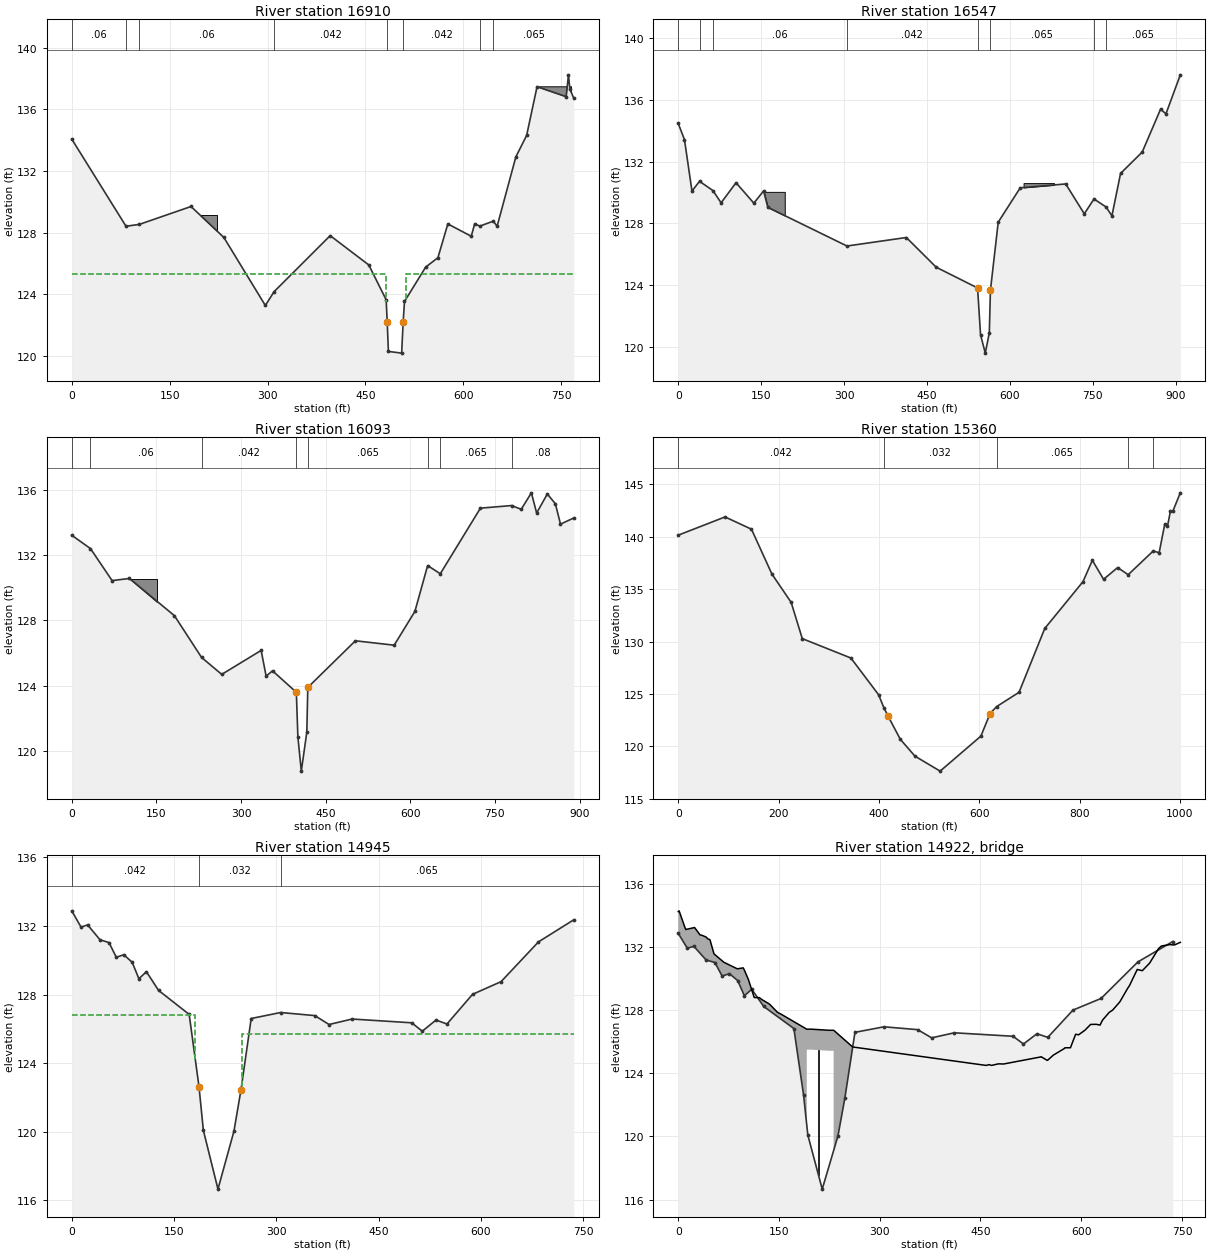
Type RM Length L Ch R = 1 ,16910   ,362.96,362.95,359.19
BEGIN DESCRIPTION:
Survyed Sections
END DESCRIPTION:
XS GIS Cut Line= 6
2312723.01970145742261.7647365782312553.72949223741839.469482422
2312543.43090819741814.9204712062312538.84667967741789.289489746
2312530.18872069741755.948303223  2312434.715113741549.541903049
#Sta/Elev= 30
       0  134.07   83.11  128.42  103.58  128.54   182.8   129.7  233.15  127.69
  296.68  123.28   310.2  124.18   396.1  127.81 455.237  125.91 481.875  123.65
 483.468  122.21 485.328   120.3 505.591  120.19 507.943  122.21 509.965  123.54
 542.446  125.77  561.21  126.38  576.41  128.57   612.3  127.77  617.49  128.57
  625.56  128.43   646.1  128.75  651.95  128.42  680.67  132.92  697.18  134.31
  713.16  137.47   757.8  136.82  761.29  138.24  763.37  137.33  769.54  136.71
#Mann= 8 ,-1 , 0
       0     .06       0   83.11    .035       0  103.58     .06       0
   310.2    .042       0 483.468    .032       0 507.943    .042       0
  625.56    .035       0   646.1    .065       0
#XS Ineff= 2 , 0
       0     482  125.34     512       0  125.34
Permanent Ineff=
       F       F
#Block Obstruct= 2 ,-1
  716.91  765.98137.4641   164.8   222.8129.1675
Bank Sta=483.468,507.943
XS Rating Curve= 0 ,0
Exp/Cntr=0.5,0.3

Type RM Length L Ch R = 1 ,16547   ,419.33,453.8,451.02
XS GIS Cut Line= 2
 2313090.0424805742198.5629272462312745.91290283 741358.03332521
#Sta/Elev= 30
       0  134.46    11.3  133.41   24.84  130.09   38.51  130.72   62.85  130.12
    77.5  129.33  104.57  130.63  136.76  129.31  154.42   130.1  162.04  129.04
  305.26  126.54   412.6  127.09  466.69  125.17   541.5  123.83  546.89   120.8
  555.42  119.62  562.73  120.93  564.75  123.68  578.85  128.08  618.68   130.3
  700.93  130.55  734.55  128.62  752.12  129.58  773.92  129.06  784.53  128.49
  800.17  131.23  839.35  132.61  872.55  135.38  882.27  135.08  908.25   137.6
#Mann= 8 ,-1 , 0
       0     .06       0   38.51    .035       0   62.85     .06       0
  305.26    .042       0   541.5    .032       0  564.75    .065       0
  752.12    .035       0  773.92    .065       0
#Block Obstruct= 2 ,-1
  153.82  192.69130.0395  624.67  679.76130.6042
Bank Sta=541.5,564.75
XS Rating Curve= 0 ,0
Exp/Cntr=0.3,0.1

Type RM Length L Ch R = 1 ,16093   ,745.48,733.48,720.71
XS GIS Cut Line= 2
2313464.62652588742076.7468872222313181.40447998741233.172119156
#Sta/Elev= 30
       0  133.22   33.19   132.4   71.48  130.44  102.19  130.57  181.92  128.29
  230.03  125.73   265.8  124.69  335.64  126.16  344.47  124.58  355.79  124.91
  398.03123.5941  400.73  120.87  406.82  118.76  416.57  121.15  418.33  123.89
  419.21  123.92   502.7  126.75  571.43  126.48  608.13  128.55  630.73  131.36
  653.15  130.86  724.25  134.88  779.42  135.04  796.61  134.81  814.58  135.82
  823.92  134.58  842.84  135.75  857.09  135.15  866.19   133.9  889.85  134.28
#Mann= 8 ,-1 , 0
       0    .035       0   33.19     .06       0  230.03    .042       0
  398.03    .032       0  419.21    .065       0  630.73    .035       0
  653.15    .065       0  779.42     .08       0
#Block Obstruct= 1 ,-1
    96.4  151.87130.5319
Bank Sta=398.03,419.21
XS Rating Curve= 0 ,0
Exp/Cntr=0.3,0.1

Type RM Length L Ch R = 1 ,15360   ,393.07,414.77,382.12
XS GIS Cut Line= 2
 2314209.6881703741817.2347863472313731.25006288740938.294190869
#Sta/Elev= 30
       0  140.15   93.31  141.89  145.98  140.72  186.71  136.44  225.07  133.74
  247.26  130.28  344.18  128.43  399.18  124.94  409.89  123.69   418.4  122.87
  442.73  120.67  471.81  119.07     522  117.64  603.23  120.98  621.45  123.12
  634.36  123.79  679.28  125.16  730.55  131.25  806.67  135.71  825.43  137.75
  847.76  135.94  875.82  137.06  896.84  136.38  946.68  138.64  958.58  138.48
  969.61  141.18  975.18  141.01  980.95  142.42  985.58  142.41 1000.72  144.19
#Mann= 5 ,-1 , 0
       0    .042       0  409.89    .032       0  634.36    .065       0
  896.84    .035       0  946.68    .065       0
Bank Sta=418.4,621.45
XS Rating Curve= 0 ,0
Exp/Cntr=0.5,0.3

Type RM Length L Ch R = 1 ,14945   ,51,42.05,66.94
BEGIN DESCRIPTION:
Survyed Section
END DESCRIPTION:
XS GIS Cut Line= 6
2314454.54705364741440.9881936612314378.25628665741307.337097168
 2314347.3817139 741218.461120622314324.22247317741165.109680176
2314299.84703059741125.5608738662314051.72426626740833.238102973
#Sta/Elev= 30
       0  132.89   13.58  131.94   23.25  132.07   41.44   131.2   54.57  131.04
   65.32  130.18   76.25  130.33   88.58  129.89   98.43  128.93  109.44  129.34
  127.27  128.25  172.16  126.85 186.619  122.62  192.94  120.09  214.37  116.66
  237.76  120.03 248.091  122.44 263.098  126.61  306.24  126.96  356.43  126.78
  377.28  126.26     411  126.58  498.46  126.36  513.99  125.87  534.07  126.52
  550.18  126.29  587.66  128.02  629.51  128.76  684.37  131.08  736.22  132.37
#Mann= 3 ,-1 , 0
       0    .042       0 186.619    .032       0  306.24    .065       0
#XS Ineff= 2 , 0
       0  181.38  126.81     249       0  125.68
Permanent Ineff=
       F       F
Bank Sta=186.619,248.091
XS Rating Curve= 0 ,0
Exp/Cntr=0.5,0.3

Type RM Length L Ch R = 3 ,14922   ,,,
BEGIN DESCRIPTION:
Golf Course Path
END DESCRIPTION:
Bridge Culvert--1,0,-1,-1, 0
Deck Dist Width WeirC Skew NumUp NumDn MinLoCord MaxHiCord MaxSubmerge Is_Ogee
15,10.3,2.6,0, 74, 74, , , 0.98, 0, 0,0,,
       0    1.28   10.42   11.42   12.83   24.36    32.3   35.84   41.73      44
   47.23   53.22   67.74   87.94    96.8   98.65  104.46  113.13  120.86  124.11
  135.48  136.25  136.35  144.06  147.69  147.75  147.79 155.201   191.3  191.38
 198.257 224.405 231.335   231.4 259.716   458.4   462.7  466.33  473.54   476.9
  484.35  539.93  540.53  540.65   540.7  548.99  549.77  558.34  574.71  575.28
  577.31   583.9  591.66  595.97  605.63  613.88   622.2  627.99   631.6  641.71
  646.73  657.38  657.58  657.95  669.34  671.73  683.37   690.9  701.78  715.17
  719.43  732.28  738.54  747.48
  134.27  134.32  133.21  133.13  133.15  133.26   132.8  132.76  132.65  132.54
  132.49  131.59  131.06  130.64   130.7  130.54  129.96  128.82  128.81   128.7
  128.41  128.38  128.38  128.04  127.88  127.88  127.88  127.71  126.81  126.81
  126.81  126.74  126.74  126.74  125.68  124.51  124.56  124.51  124.58  124.61
   124.6  125.05  125.04  125.04  125.05  124.84  124.83  125.16  125.58  125.62
  125.63  125.63  126.49  126.45  126.75  127.11  127.12  127.07  127.38  127.88
  128.02  128.54  128.56  128.58  129.42  129.57   130.6  130.52     131  131.93
  132.09  132.18  132.15  132.32
                                                                                
                                                                                
                                                                          125.51
  125.51  125.44  125.44
                                                                                
                                                                                
                                                                                
                                
       0    1.28   10.42   11.42   12.83   24.36    32.3   35.84   41.73      44
   47.23   53.22   67.74   87.94    96.8   98.65  104.46  113.13  120.86  124.11
  135.48  136.25  136.35  144.06  147.69  147.75  147.79 155.201   191.3  191.38
 198.257 224.405 231.335   231.4 259.716   458.4   462.7  466.33  473.54   476.9
  484.35  539.93  540.53  540.65   540.7  548.99  549.77  558.34  574.71  575.28
  577.31   583.9  591.66  595.97  605.63  613.88   622.2  627.99   631.6  641.71
  646.73  657.38  657.58  657.95  669.34  671.73  683.37   690.9  701.78  715.17
  719.43  732.28  738.54  747.48
  134.27  134.32  133.21  133.13  133.15  133.26   132.8  132.76  132.65  132.54
  132.49  131.59  131.06  130.64   130.7  130.54  129.96  128.82  128.81   128.7
  128.41  128.38  128.38  128.04  127.88  127.88  127.88  127.71  126.81  126.81
  126.81  126.74  126.74  126.74  125.68  124.51  124.56  124.51  124.58  124.61
   124.6  125.05  125.04  125.04  125.05  124.84  124.83  125.16  125.58  125.62
  125.63  125.63  126.49  126.45  126.75  127.11  127.12  127.07  127.38  127.88
  128.02  128.54  128.56  128.58  129.42  129.57   130.6  130.52     131  131.93
  132.09  132.18  132.15  132.32
                                                                                
                                                                                
                                                                          125.51
  125.51  125.44  125.44
                                                                                
                                                                                
                                                                                
                                
Pier Skew, UpSta & Num, DnSta & Num=  ,208.88, 2 ,208.88, 2 , 0 , 0 , 0 ,,
       1       1
     110     126
       1       1
     110     126
BR Coef=-1 , 0 , 0 ,, 0 ,,,0.8,0,,0,
WSPro=,,,, 1 ,,,, 0 ,,,, 0 ,,,,-1 ,-1 ,-1 , 0 , 0 , 0 , 0 , 0
BC Design=,, 0 ,, 0 ,,,,,,
BC Use User HTab Curves=0
BC User HTab FreeFlow(D)= 0

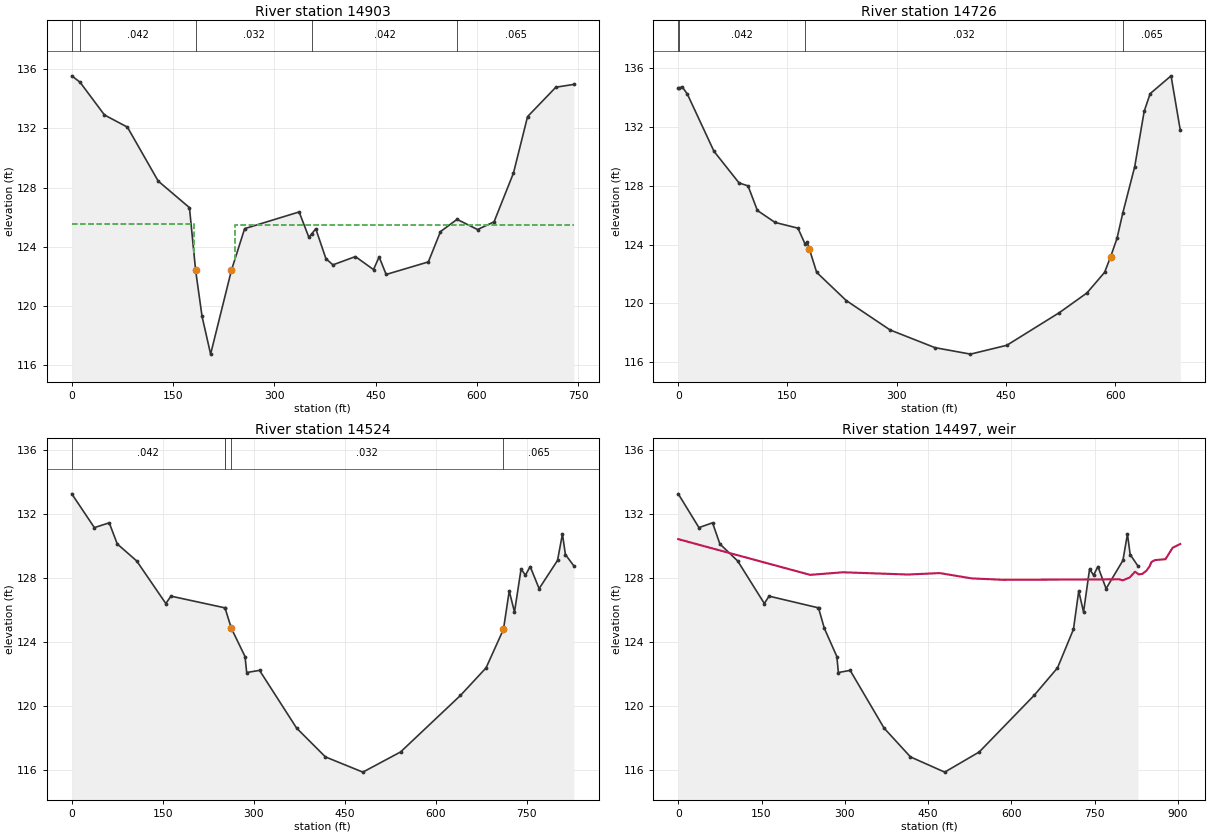
Type RM Length L Ch R = 1 ,14903   ,179.14,176.84,161.7
BEGIN DESCRIPTION:
Survyed Sections
END DESCRIPTION:
XS GIS Cut Line= 6
2314498.74706027741415.8745535612314432.63488771741299.230895996
2314397.81127934741243.1077270512314376.50091556741191.532104492
2314336.01067233741078.3472304642314109.98791134740789.038096398
#Sta/Elev= 30
       0  135.56   12.19  135.13   48.46  132.91   82.37  132.09  127.98  128.44
 174.275  126.64 183.424  122.39  192.94  119.28   205.6  116.73 236.527  122.42
 255.975  125.22  336.68  126.35  351.14  124.63  355.46  124.88  361.32  125.21
  376.36  123.19  386.71  122.77  420.02  123.33  446.83  122.45  455.16  123.31
  465.53  122.12  528.03  122.97     546  125.02  570.56  125.85  600.91  125.16
  625.32  125.68  654.06  128.98  674.94   132.8  716.84  134.79  743.49  134.98
#Mann= 5 ,-1 , 0
       0     .03       0   12.19    .042       0 183.424    .032       0
  355.46    .042       0  570.56    .065       0
#XS Ineff= 2 , 0
       0  181.38  125.51  241.34       0  125.44
Permanent Ineff=
       F       F
Bank Sta=183.424,236.527
XS Rating Curve= 0 ,0
Exp/Cntr=0.5,0.3

Type RM Length L Ch R = 1 ,14726   ,197.89,201.66,48.61
XS GIS Cut Line= 2
2314665.40808104741332.197875991 2314293.5808716740751.660888687
#Sta/Elev= 30
       0  134.59     .69   134.6    5.32  134.71   12.43  134.22   49.06  130.33
   83.52  128.18   95.84  127.98  108.69  126.31  132.92   125.5  164.38  125.11
  174.28  124.02  176.94  124.18  179.93  123.71  190.11  122.11  230.61   120.2
  290.93   118.2  352.51     117  401.26  116.56  451.17  117.16  523.43  119.38
  561.13  120.71  585.43  122.11  593.78  123.18  602.44  124.41  610.47  126.15
  626.78  129.28  639.78  133.04  647.99  134.24  676.69  135.45   689.4  131.75
#Mann= 4 ,-1 , 0
       0     .03       0     .69    .042       0  174.28    .032       0
  610.47    .065       0
Bank Sta=179.93,593.78
XS Rating Curve= 0 ,0
Exp/Cntr=0.5,0.3

Type RM Length L Ch R = 1 ,14524   ,159.33,194.42,456.86
XS GIS Cut Line= 6
  2314851.753479741315.1920776522314702.82611084741061.798706055
2314700.81671144741058.1190796052314698.95568849741054.723693863
2314697.64550784741050.6129150392314285.70972622740730.644447813
#Sta/Elev= 30
       0  133.27   37.28  131.16   61.78  131.46      75  130.14  107.03  129.08
  155.08  126.42  163.57  126.88  252.54  126.15  252.82  126.13  263.06  124.88
  285.68  123.11  288.42  122.11  309.63122.2452  370.74  118.64  418.31  116.84
     480  115.89  542.19  117.15  640.93  120.68  683.12   122.4  711.86  124.81
  721.36   127.2  730.03  125.89  740.88  128.57  748.09  128.19  755.93  128.73
  770.63  127.35  800.96  129.11  809.11  130.76  813.99  129.48   827.9  128.77
#Mann= 5 ,-1 , 0
       0    .042       0  252.54    .032       0  252.82     .05       0
  263.06    .032       0  711.86    .065       0
Bank Sta=263.06,711.86
XS Rating Curve= 0 ,0
Exp/Cntr=0.5,0.3

Type RM Length L Ch R = 5 ,14497   ,,,
BEGIN DESCRIPTION:
Country Club Drive
END DESCRIPTION:
IW Pilot Flow=0
#Inline Weir SE= 20
       0  130.44  237.55  128.21 296.668  128.37 413.863  128.23 470.889  128.32
 528.057  127.99 585.188   127.9  795.14  127.93  800.72  127.87  813.03  128.04
  822.76  128.41  829.24  128.24  835.95  128.27  843.38  128.47  849.08  128.75
  852.52  129.02  858.58  129.13  877.68  129.19  890.43   129.9  904.33  130.14
IW Dist,WD,Coef,Skew,MaxSub,Min_El,Is_Ogee,SpillHt,DesHd
25,30,2.6,0,0.98,, 0 ,,,1,1,