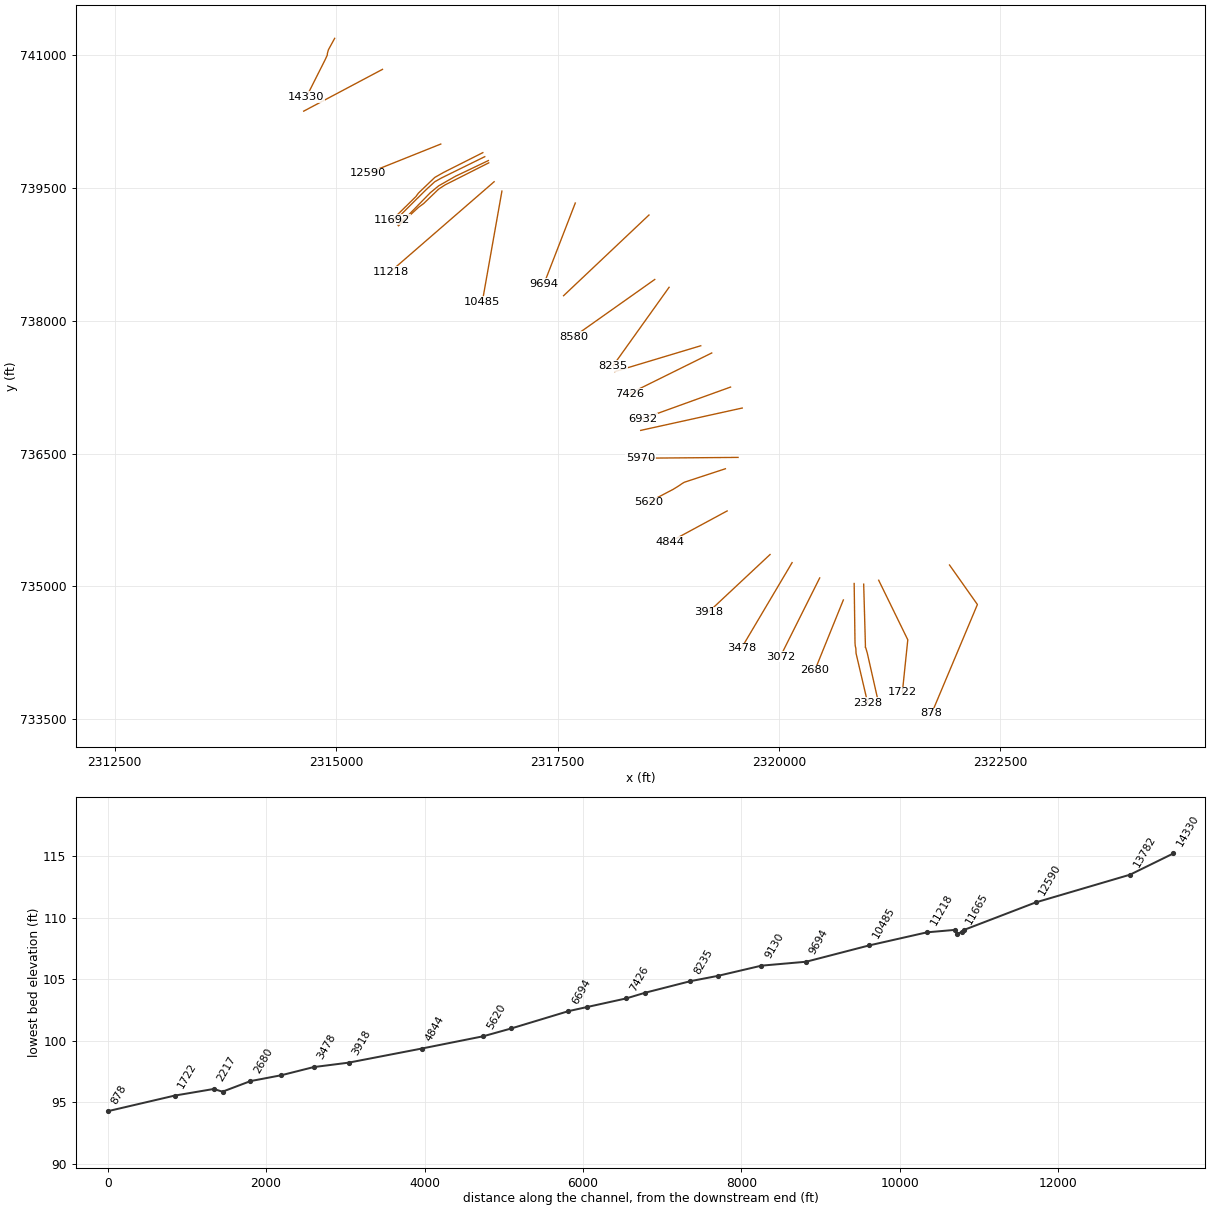
HEC-RAS study dtl_toisnot_swp_tri.prj: dtl_toisnot_swp_trib

--- dtl_toisnot_swp_tri.g01 (geometry) --- (continued)

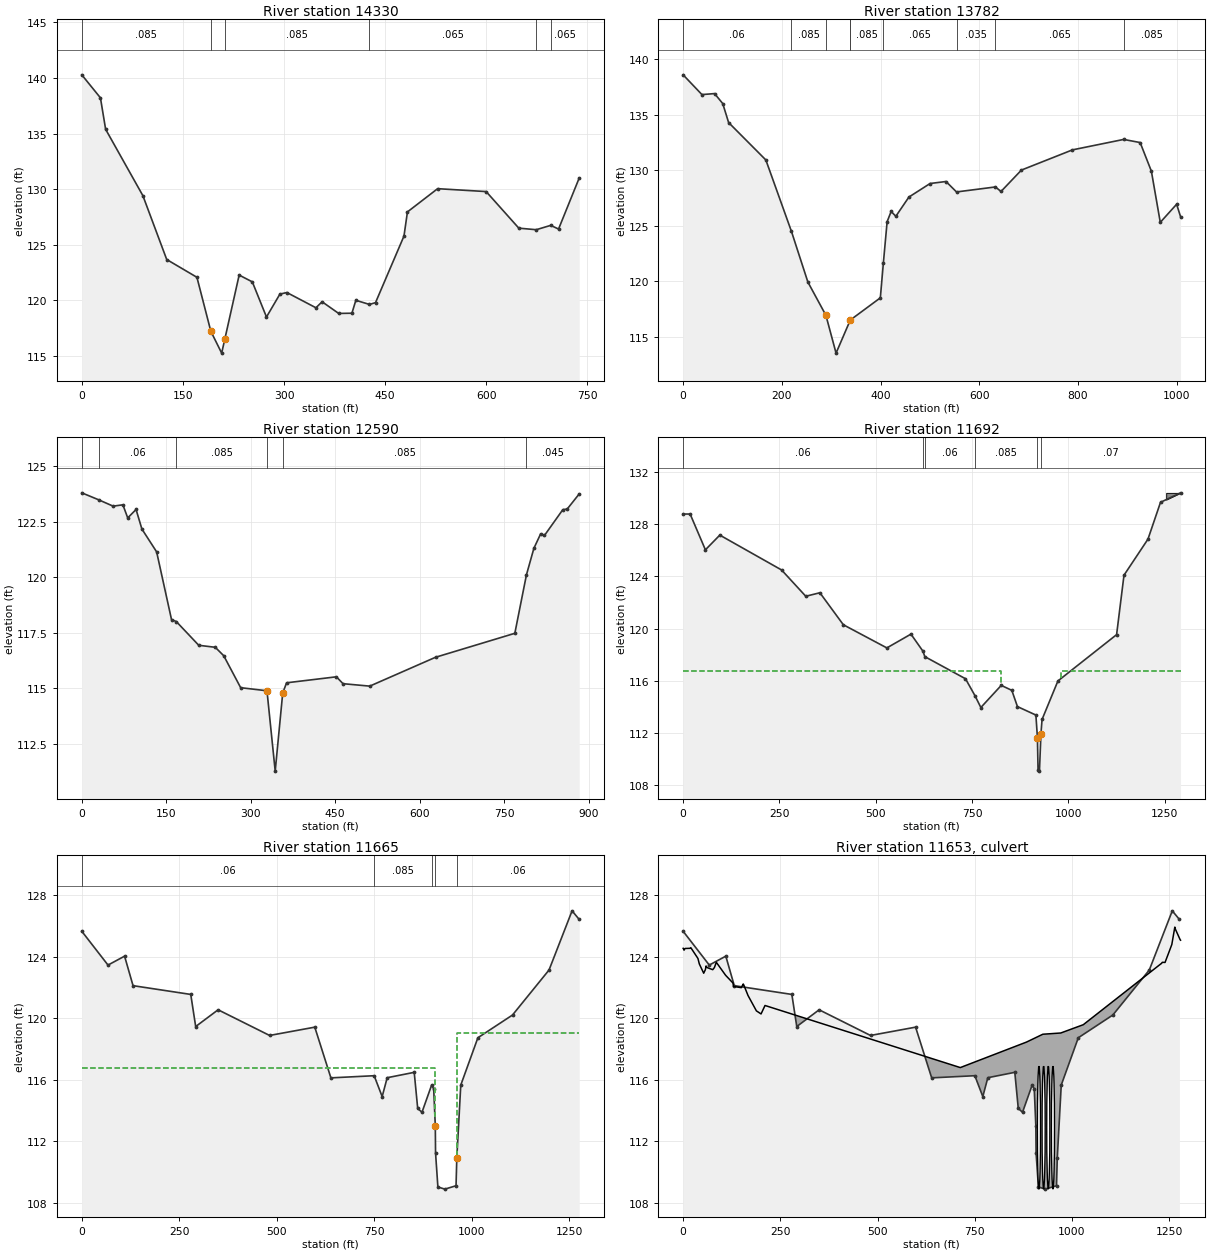
Type RM Length L Ch R = 1 ,14330   ,573.76,547.75,396.37
BEGIN DESCRIPTION:
Survyed Sections
END DESCRIPTION:
XS GIS Cut Line= 6
2314983.38769533741192.6362915192314912.10351561741062.167297363
2314900.18609624741017.4373169092314900.78271484741004.792297378
2314874.03051759740947.1281128082314664.23229983740530.409912109
#Sta/Elev= 30
       0  140.28   27.67  138.21   35.38  135.38   90.65  129.41     126  123.67
  170.82  122.07  191.42  117.22  207.52  115.25  212.16   116.5  233.46  122.27
  252.99  121.66     274   118.5  293.94  120.56  304.28   120.7  347.37  119.33
  356.52  119.87  381.12  118.82  400.76  118.84  406.57     120  426.83  119.63
  435.76  119.79     478  125.78  483.12  127.95  527.91  130.04  599.89  129.78
  648.36  126.49  674.19  126.35  695.66  126.74  707.32  126.41  737.95     131
#Mann= 6 ,-1 , 0
       0    .085       0  191.42     .05       0  212.16    .085       0
  426.83    .065       0  674.19    .035       0  695.66    .065       0
Bank Sta=191.42,212.16
XS Rating Curve= 0 ,0
Exp/Cntr=0.5,0.3

Type RM Length L Ch R = 1 ,13782   ,1074.33,1192.36,1000.29
XS GIS Cut Line= 2
2315523.61219579740842.151478603 2314633.4463968740369.537678123
#Sta/Elev= 30
       0  138.59    38.1  136.81   63.74   136.9   80.27     136   92.17  134.29
  167.62  130.92  219.51  124.48  252.78  119.92  289.25  116.93  309.87  113.52
  338.69   116.5  399.57   118.5  405.66  121.61  413.34  125.36  421.45  126.28
  431.04  125.85  457.49  127.58  500.41   128.8  532.61  128.98  553.91  128.04
  632.83  128.49  644.05  128.08  685.46  130.01  788.86  131.83  892.55  132.77
     926  132.49  948.76  129.91   966.8   125.3  999.88  126.93 1007.85  125.82
#Mann= 9 ,-1 , 0
       0     .06       0  219.51    .085       0  289.25     .05       0
  338.69    .085       0  338.69    .085       0  405.66    .065       0
  553.91    .035       0  632.83    .065       0  892.55    .085       0
Bank Sta=289.25,338.69
XS Rating Curve= 0 ,0
Exp/Cntr=0.3,0.1

Type RM Length L Ch R = 1 ,12590   ,349.14,897.93,513.33
XS GIS Cut Line= 2
2316181.60687254739997.9517212062315361.52807619739669.658081055
#Sta/Elev= 30
       0   123.8   29.77123.4883   55.63   123.2      73  123.26   81.57  122.67
   96.39  123.05  106.73  122.17  132.91  121.14  159.34  118.09  167.84     118
  207.73  116.93  237.06  116.84  252.07  116.46  282.15  115.02  328.87  114.88
  343.48  111.26  356.83  114.78   363.7  115.24  452.16  115.51  463.89   115.2
  511.37  115.09  628.19  116.39  769.03  117.47  789.71  120.11  802.87   121.3
  814.86  121.95  821.68  121.88   854.2  123.04  862.04  123.07  883.35  123.75
#Mann= 6 ,-1 , 0
       0    .035       0   29.77     .06       0  167.84    .085       0
  328.87     .05       0  356.83    .085       0  789.71    .045       0
Bank Sta=328.87,356.83
XS Rating Curve= 0 ,0
Exp/Cntr=0.3,0.1

Type RM Length L Ch R = 1 ,11692   ,38.75,26.96,27.58
BEGIN DESCRIPTION:
Survyed Sections
END DESCRIPTION:
XS GIS Cut Line= 6
2316656.58336242739900.835822105 2316213.2439023 739677.15700081
2316114.12873597 739620.902446972315928.60089113739442.975708008
2315900.51409915739404.1867065582315633.28624003 739141.39934513
#Sta/Elev= 30
       0   128.8   18.17   128.8   57.82  126.05   95.23  127.18  255.58   124.5
  318.35  122.48  354.96  122.75  415.85  120.29  528.84  118.51  591.31  119.57
  622.43  118.26  627.34  117.84  732.91  116.14  757.48  114.84  772.76  113.93
   825.7  115.63  853.12  115.25 867.744     114 915.631  113.35 919.585  111.62
  921.23  109.14  924.87  109.04  928.79  111.92 931.612  113.01 972.794  115.97
 1125.11  119.53 1144.32   124.1 1206.53  126.87 1239.08   129.7 1291.09  130.43
#Mann= 6 ,-1 , 0
       0     .06       0  622.43    .085       0  627.34     .06       0
  757.48    .085       0 919.585    .055       0  928.79     .07       0
#XS Ineff= 2 , 0
       0   825.7   116.7     982       0   116.7
Permanent Ineff=
       F       F
#Block Obstruct= 1 ,-1
 1253.84 1291.09130.4266
Bank Sta=919.585,928.79
XS Rating Curve= 0 ,0
Exp/Cntr=0.5,0.3

Type RM Length L Ch R = 1 ,11665   ,62.55,67,67.81
BEGIN DESCRIPTION:
Surveyed Section
END DESCRIPTION:
XS GIS Cut Line= 6
2316678.34188853739855.1385643782316189.74906011739614.750892773
2316113.52857888739571.7547238922316015.81001318739481.853643462
2315853.89874756739321.9654574692315653.54515083739120.993485466
#Sta/Elev= 30
       0  125.66   67.26  123.46  109.77  124.04  131.51  122.12  279.57  121.55
   292.2  119.46 349.751  120.55  481.85  118.88  597.76  119.42   639.1  116.12
  750.12  116.26  770.65   114.9  783.52  116.13  852.88  116.48   861.8  114.13
  872.75  113.88  897.52  115.65  902.86   115.4  906.96     113  907.61  111.23
   913.6  109.02 931.469  108.88  960.17   109.1  962.12  110.89  972.32  115.65
  1016.2  118.73 1105.04  120.21 1198.77  123.141257.849  126.99 1276.15  126.43
#Mann= 5 ,-1 , 0
       0     .06       0  750.12    .085       0  897.52     .06       0
  906.96     .05       0  962.12     .06       0
#XS Ineff= 3 ,-1
                               0     906  116.79   962.5    1276  119.04
Permanent Ineff=
       F       T       T
Bank Sta=906.96,962.12
XS Rating Curve= 0 ,0
Exp/Cntr=0.5,0.3

Type RM Length L Ch R = 2 ,11653   ,,,
BEGIN DESCRIPTION:
Lake Wilson Road
END DESCRIPTION:
Bridge Culvert--1,0,-1,-1, 0
Deck Dist Width WeirC Skew NumUp NumDn MinLoCord MaxHiCord MaxSubmerge Is_Ogee
8,40,2.6,0, 43, 43, , , 0.98, 0, 0,0,,
       0    1.82   2.329    4.96   17.67   19.47   19.85  38.079   41.69   52.88
   57.18   59.01   61.39   76.13  80.429   85.35  109.39  109.41  127.13  128.22
  129.49  149.53  154.54  155.89  166.86  188.42  200.36 210.579  712.72     883
     925     971    1029 1229.031229.989 1232.13 1239.18 1249.861256.671 1264.35
 1265.95 1278.08 1279.09
  124.55  124.47  124.43  124.54  124.55  124.59  124.59  123.89  123.53  122.93
  123.16   123.4   123.3  123.16   123.3  123.64  122.79  122.79  122.32  122.29
  122.07  121.99  122.23  122.17  121.48  120.48  120.28  120.83  116.79  118.45
  118.96  119.04  119.58  123.55  123.56  123.64  123.63  124.34   124.8  125.93
  125.79  125.11  125.08
                                                                                
                                                                                
                                                                                
                                                                                
                        
       0    1.82   2.329    4.96   17.67   19.47   19.85  38.079   41.69   52.88
   57.18   59.01   61.39   76.13  80.429   85.35  109.39  109.41  127.13  128.22
  129.49  149.53  154.54  155.89  166.86  188.42  200.36 210.579  712.72     883
     925     971    1029 1229.031229.989 1232.13 1239.18 1249.861256.671 1264.35
 1265.95 1278.08 1279.09
  124.55  124.47  124.43  124.54  124.55  124.59  124.59  123.89  123.53  122.93
  123.16   123.4   123.3  123.16   123.3  123.64  122.79  122.79  122.32  122.29
  122.07  121.99  122.23  122.17  121.48  120.48  120.28  120.83  116.79  118.45
  118.96  119.04  119.58  123.55  123.56  123.64  123.63  124.34   124.8  125.93
  125.79  125.11  125.08
                                                                                
                                                                                
                                                                                
                                                                                
                        
BR Coef=-1 , 0 , 0 ,, 0 ,,,0.8,0,,0,
WSPro=,,,, 1 ,,,, 0 ,,,, 0 ,,,,-1 ,-1 ,-1 , 0 , 0 , 0 , 0 , 0
Multiple Barrel Culv=1,8,,59,0.027,0.5,1,2,1,108.88,108.67, 4,Culvert #1  , 0 ,8
     915     907     927     919     939     931     951     943
Culvert Bottom n=0.027
BC Design=,, 0 ,, 0 ,,,,,,
BC Use User HTab Curves=0
BC User HTab FreeFlow(D)= 0

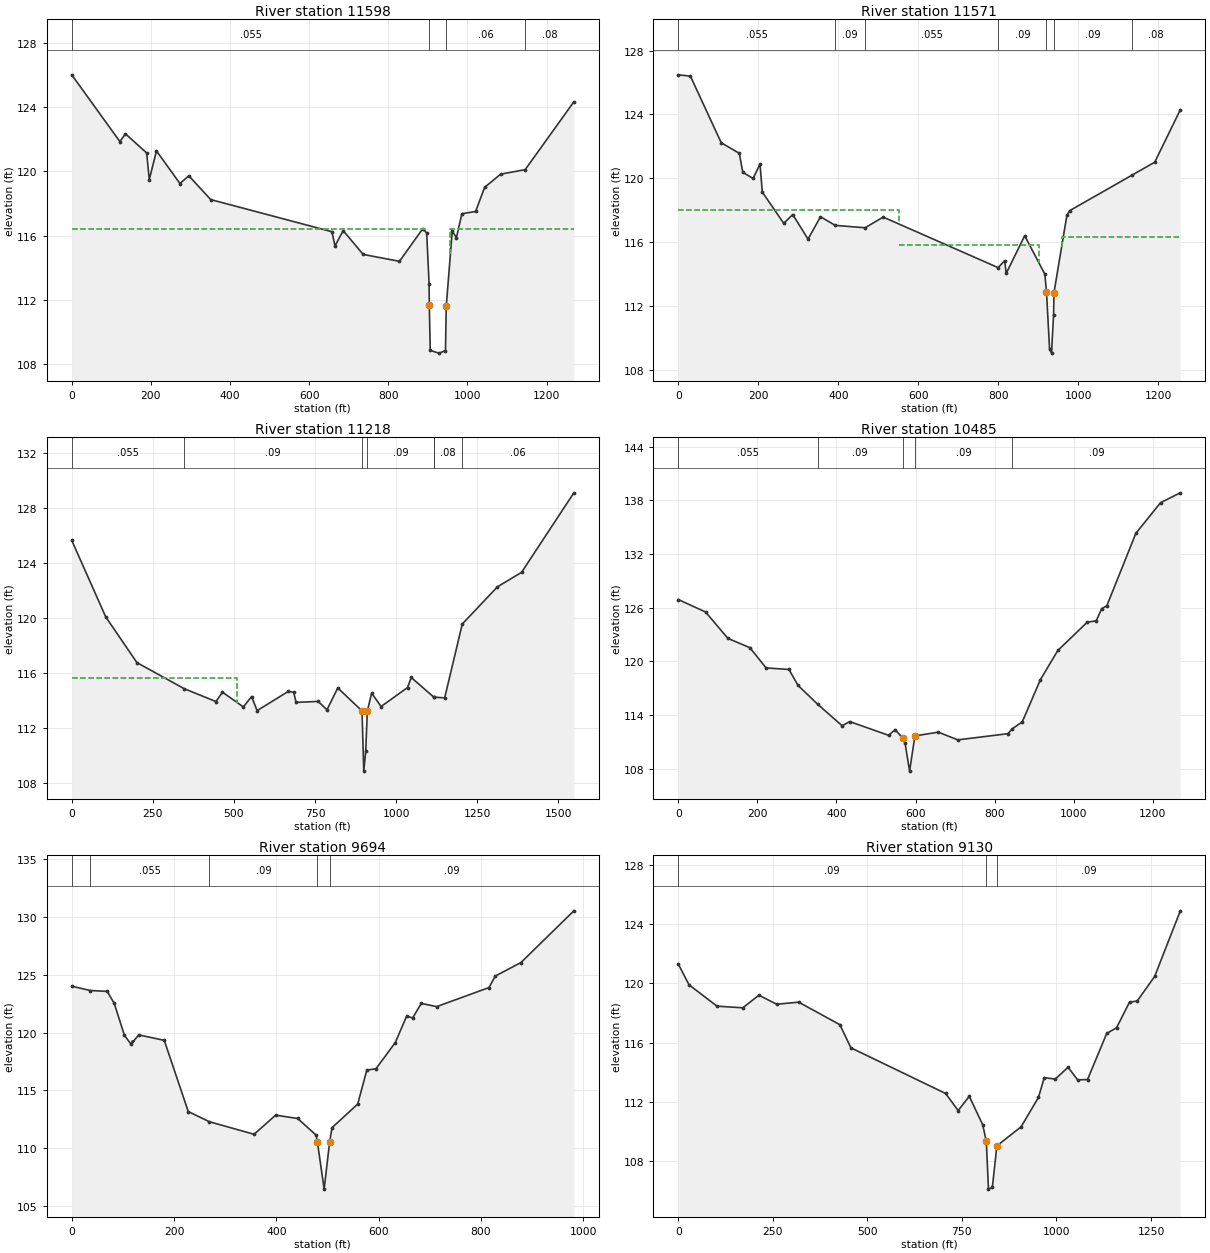
Type RM Length L Ch R = 1 ,11598   ,29.8,26.88,15.4
BEGIN DESCRIPTION:
Surveyed Section
END DESCRIPTION:
XS GIS Cut Line= 6
2316719.10885265739811.3407978712316346.43467277739633.248711884
2316157.34924819739525.513993233  2316061.707202739446.361955032
2315816.45268781739195.0611045512315695.86950457739085.608676732
#Sta/Elev= 30
       0  126.01   121.5  121.86  135.77  122.34  189.28  121.15  195.92  119.49
  214.01  121.28  273.38  119.25  295.78  119.73  351.19  118.25  657.67  116.25
  665.22  115.37  685.97  116.32  736.39  114.84  828.18  114.41  887.13  116.44
 897.029  116.17     903  113.03  903.54  111.72 905.951  108.87  927.65   108.7
   944.5  108.85  946.43  111.61  961.56  116.29   972.1  115.88  985.94  117.37
 1020.59  117.51 1043.44  119.011083.689  119.83 1145.81  120.11 1268.89  124.33
#Mann= 4 ,-1 , 0
       0    .055       0  903.54     .05       0  946.43     .06       0
 1145.81     .08       0
#XS Ineff= 2 , 0
       0     893   116.4     957       0  116.45
Permanent Ineff=
       F       F
Bank Sta=903.54,946.43
XS Rating Curve= 0 ,0
Exp/Cntr=0.5,0.3

Type RM Length L Ch R = 1 ,11571   ,363.72,352.79,345.23
BEGIN DESCRIPTION:
Surveyed Section
END DESCRIPTION:
XS GIS Cut Line= 6
2316723.55306931739785.647926092 2316230.6560261739536.520616218
2316156.98934846739488.3024272022315987.93267824739325.361877456
2315932.92370608739285.1499023592315704.27412936739074.429638177
#Sta/Elev= 30
       0  126.48   30.37   126.4  107.46  122.22  152.59  121.56  161.28  120.37
  187.09  119.98  204.35  120.89  210.06  119.13  263.62  117.17  286.09  117.72
  324.34  116.18  355.44  117.58  392.42  117.04  466.82  116.89  512.06  117.56
   799.4  114.39  815.67  114.83  819.49  114.03  865.71  116.39  916.07  113.98
  920.18  112.88   927.9  109.26  932.76  109.03  937.88  111.45  938.97  112.83
  971.18  117.68  978.63  117.97 1134.61   120.2 1190.58     121 1254.55  124.29
#Mann= 7 ,-1 , 0
       0    .055       0  392.42     .09       0  466.82    .055       0
   799.4     .09       0  920.18     .05       0  938.97     .09       0
 1134.61     .08       0
#XS Ineff= 3 ,-1
       0  552.28     118  552.28  901.07  115.84     958 1254.55   116.3
Permanent Ineff=
       F       F       F
Bank Sta=920.18,938.97
XS Rating Curve= 0 ,0
Exp/Cntr=0.3,0.1

Type RM Length L Ch R = 1 ,11218   ,388.04,732.95,791.36
XS GIS Cut Line= 2
2316784.31508347739572.1811865272315615.43833993738557.472838432
#Sta/Elev= 30
       0  125.61  104.66  120.05  200.95  116.72  346.41  114.83  444.41  113.89
  464.66  114.57  528.99   113.5  554.29  114.25  571.45  113.23  667.63  114.63
  684.11  114.56  691.62  113.83  759.76   113.9  786.79  113.29  820.06  114.88
  894.76  113.21  900.22  108.83  906.21  110.27  911.27  113.21  924.47   114.5
  953.69  113.53 1035.24  114.91 1046.45  115.64 1115.86  114.22 1116.02  114.21
 1149.66  114.16 1203.93  119.53 1312.13  122.23  1386.8  123.29 1547.87  129.07
#Mann= 7 ,-1 , 0
       0    .055       0  346.41     .09       0  894.76     .05       0
  911.27     .09       0 1115.86     .09       0 1116.02     .08       0
 1203.93     .06       0
#XS Ineff= 2 , 0
       0     510   115.6 1046.45       0  115.64
Permanent Ineff=
       F       F
Bank Sta=894.76,911.27
XS Rating Curve= 0 ,0
Exp/Cntr=0.3,0.1

Type RM Length L Ch R = 1 ,10485   ,796.58,791.25,760.85
XS GIS Cut Line= 2
2316872.12604575739466.3983183062316650.85829175738216.534518763
#Sta/Elev= 30
       0  126.92   68.98  125.53  125.52  122.58  181.16  121.54  222.16  119.28
  279.89  119.11  302.95  117.33  352.86  115.21  414.38  112.83  433.43  113.29
  531.78  111.76  548.39   112.4  567.69  111.42   573.6  110.85   584.9  107.76
  598.24  111.69  657.58  112.11  706.62  111.25  833.38  111.94  844.97   112.5
  869.78  113.26  915.69  117.98  959.65  121.23  1033.6  124.37 1056.75  124.55
 1070.58   125.9 1083.43  126.21 1156.94  134.31 1219.28  137.73  1269.3  138.83
#Mann= 5 ,-1 , 0
       0    .055       0  352.86     .09       0  567.69     .05       0
  598.24     .09       0  844.97     .09       0
Bank Sta=567.69,598.24
XS Rating Curve= 0 ,0
Exp/Cntr=0.3,0.1

Type RM Length L Ch R = 1 ,9694    ,546.18,564.17,447.61
XS GIS Cut Line= 2
2317700.72869875739331.5789184722317346.37707523738416.427124023
#Sta/Elev= 30
       0  124.02   36.21123.6463   69.21  123.57   82.95  122.54  102.89  119.77
  115.74     119  131.05   119.8  180.77  119.33  227.71  113.16  269.19112.2751
  356.41  111.19  398.45  112.85   441.5  112.56   477.8  111.11  480.18   110.5
   493.3  106.44  503.96   110.5  508.64  111.76   558.9  113.81  576.66  116.75
  594.61  116.87  632.38  119.14  654.59  121.43  666.24  121.27   683.2  122.53
  713.22  122.25  815.38   123.9   827.9   124.9  877.97  126.07  981.36  130.55
#Mann= 5 ,-1 , 0
       0    .032       0   36.21    .055       0  269.19     .09       0
  480.18     .05       0  503.96     .09       0
#Block Obstruct= 1 ,-1
  116.39  179.15119.3305
Bank Sta=480.18,503.96
XS Rating Curve= 0 ,0
Exp/Cntr=0.3,0.1

Type RM Length L Ch R = 1 ,9130    ,546.92,549.62,489.49
XS GIS Cut Line= 2
2318532.68487552739196.0006714022317568.23187254738283.930297866
#Sta/Elev= 30
       0  121.31   28.56   119.9  102.46  118.46  170.75  118.35  213.26   119.2
  260.26  118.59  318.48  118.73  427.36  117.21  456.57  115.65  707.07  112.57
  740.03  111.42  769.48  112.38  805.03  110.46   814.5  109.34  820.22  106.12
  830.45  106.23  842.39  109.04  906.37  110.32  952.27   112.3  967.77  113.64
  996.72  113.54 1030.71  114.34 1055.89  113.49 1082.07  113.51 1132.87  116.62
 1158.74     117  1193.1  118.73 1213.64  118.81 1259.68  120.47 1327.42  124.89
#Mann= 3 ,-1 , 0
       0     .09       0   814.5     .05       0  842.39     .09       0
Bank Sta=814.5,842.39
XS Rating Curve= 0 ,0
Exp/Cntr=0.3,0.1

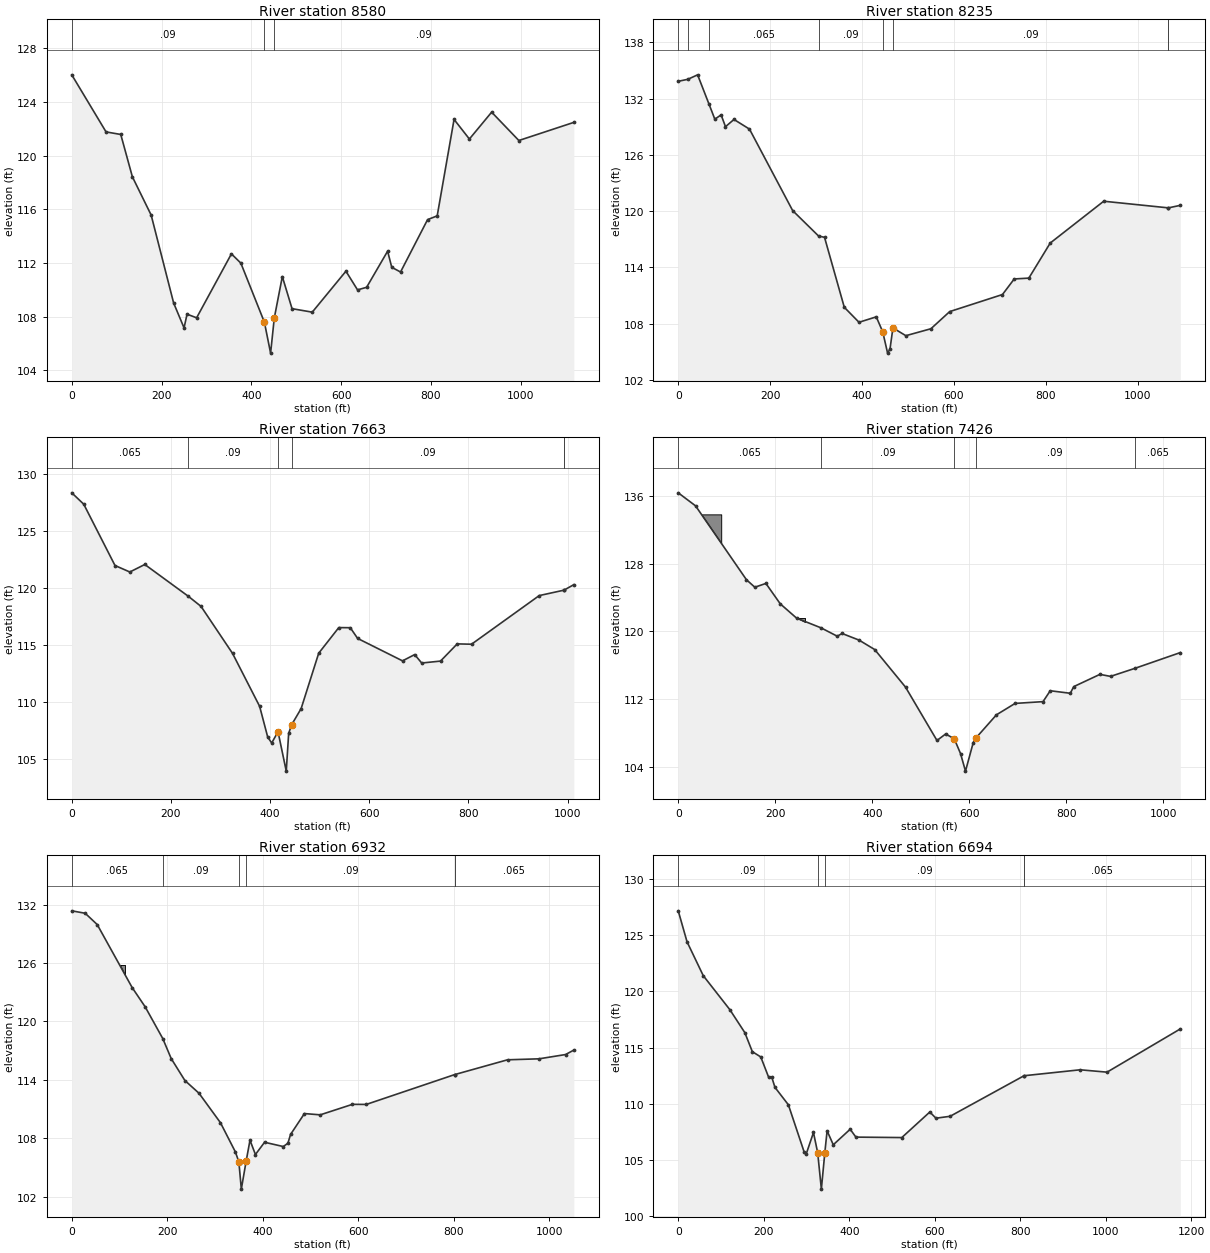
Type RM Length L Ch R = 1 ,8580    ,276.16,345.82,387.16
XS GIS Cut Line= 2
2318597.88440859738467.5838265422317685.07977466 737821.52371031
#Sta/Elev= 30
       0  126.01   76.36  121.76  109.12  121.57  134.97  118.42  176.81  115.57
  226.92  109.02  250.08  107.17  256.78  108.19  278.09  107.92  355.59  112.68
  376.62  111.99  429.06  107.59  442.87  105.29  451.07   107.9  468.97  110.99
  490.62   108.6  535.66  108.34  610.66  111.39  636.48     110  656.71  110.19
  703.51  112.88   712.7  111.68  732.29  111.33  792.54  115.23  813.95  115.51
  851.49  122.69  885.64  121.23  935.21  123.23  995.81  121.12  1118.3  122.47
#Mann= 3 ,-1 , 0
       0     .09       0  429.06     .05       0  451.07     .09       0
Bank Sta=429.06,451.07
XS Rating Curve= 0 ,0
Exp/Cntr=0.3,0.1

Type RM Length L Ch R = 1 ,8235    ,557.18,571.74,389.03
XS GIS Cut Line= 2
2318760.03008629738379.235954076 2318124.9535791737489.556703091
#Sta/Elev= 30
       0  133.85   20.88134.0623   42.19  134.54   66.79  131.44   79.68  129.81
   93.33  130.27  102.89  129.01  121.36  129.78  155.13  128.75  249.14  120.06
  305.52  117.35   318.5  117.21  361.52  109.75  393.55  108.15  431.17  108.73
  445.22  107.13  455.81  104.86  461.08  105.31  467.41  107.55  495.55  106.72
  550.12  107.46  591.02  109.29   705.9  111.11  731.51  112.77   763.3  112.86
  809.88   116.6  926.32  121.06 1066.75120.3533 1066.97  120.35 1093.09  120.62
#Mann= 8 ,-1 , 0
       0    .065       0   20.88     .09       0   66.79    .065       0
  305.52     .09       0  445.22     .05       0  467.41     .09       0
 1066.75     .09       0 1066.97    .065       0
Bank Sta=445.22,467.41
XS Rating Curve= 0 ,0
Exp/Cntr=0.3,0.1

Type RM Length L Ch R = 1 ,7663    ,209.42,236.93,222.08
XS GIS Cut Line= 2
2319117.61820963737718.413102046  2318147.839219737426.621193364
#Sta/Elev= 30
       0  128.35   24.18  127.35   87.19  121.97  117.12   121.4  147.32  122.06
  235.05  119.27  260.75  118.38  324.22  114.26  378.92  109.61  395.29   106.9
  403.29  106.39  416.03  107.38  432.64  103.92   437.5  107.23  443.47  107.99
  462.64  109.41  498.08  114.27  538.59  116.52  561.79  116.51  576.58  115.57
  667.16   113.6  691.66  114.15  705.84  113.41  743.81  113.58   777.5  115.09
  806.37  115.06  942.92  119.33  993.28  119.81  993.38  119.82 1012.73  120.29
#Mann= 6 ,-1 , 0
       0    .065       0  235.05     .09       0  416.03     .05       0
  443.47     .09       0  993.28     .09       0  993.38    .065       0
Bank Sta=416.03,443.47
XS Rating Curve= 0 ,0
Exp/Cntr=0.3,0.1

Type RM Length L Ch R = 1 ,7426    ,471.53,493.56,443.77
XS GIS Cut Line= 2
2319241.38830571737636.8532715142318313.91107176737177.736694336
#Sta/Elev= 30
       0  136.42   35.66  134.88  140.67  126.12  157.89  125.24  180.64  125.69
  210.29  123.27  243.92  121.58  294.22  120.43  327.66  119.44  337.67  119.76
  372.52  118.98  404.85  117.86  468.37  113.41   533.2  107.09  551.09  107.86
  568.81  107.29  581.73  105.54  591.96  103.46  607.93  106.84   612.6  107.33
  655.77  110.13  694.19  111.48  751.75  111.69  766.61  112.98  807.93  112.68
  815.08  113.47  869.02  114.92  890.86  114.68  940.41  115.62 1034.65   117.5
#Mann= 5 ,-1 , 0
       0    .065       0  294.22     .09       0  568.81     .05       0
   612.6     .09       0  940.41    .065       0
#Block Obstruct= 2 ,-1
    48.7   88.57133.8694  243.91   261.6121.5784
Bank Sta=568.81,612.6
XS Rating Curve= 0 ,0
Exp/Cntr=0.3,0.1

Type RM Length L Ch R = 1 ,6932    ,250.4,238.39,229.82
XS GIS Cut Line= 2
2319453.99932863737251.6884765632318464.89587402736894.255310059
#Sta/Elev= 30
       0  131.38   28.09  131.13   53.27  129.97  126.47  123.49  153.71  121.51
  190.57  118.25  208.35  116.18  236.97  113.93  266.55  112.62  311.45  109.59
  342.69  106.59  350.01  105.56  355.18  102.76  365.46  105.69  373.33  107.79
  384.71  106.32  403.85  107.58  443.05  107.14  452.76  107.48  458.25  108.38
  487.33  110.53  520.48   110.4  587.93  111.48   616.9  111.47  802.14  114.54
  802.24114.5409  912.79  116.06  978.64  116.16 1034.29   116.6 1051.71  117.06
#Mann= 6 ,-1 , 0
       0    .065       0  190.57     .09       0  350.01     .05       0
  365.46     .09       0  802.14     .09       0  802.24    .065       0
#Block Obstruct= 1 ,-1
   100.6  112.26125.7777
Bank Sta=350.01,365.46
XS Rating Curve= 0 ,0
Exp/Cntr=0.3,0.1

Type RM Length L Ch R = 1 ,6694    ,553.74,723.48,540.94
XS GIS Cut Line= 2
2319585.91423237737014.7592353222318439.31461678736761.965619296
#Sta/Elev= 30
       0  127.14   20.56  124.39   58.52  121.38  120.71  118.36  155.74  116.32
  173.28  114.63  193.02  114.16  211.09  112.39  218.66  112.37  226.17  111.46
  257.57  109.91  294.17  105.75  299.53  105.57  316.25  107.45  326.06  105.66
  334.71  102.42  342.74  105.64  348.11   107.6  362.55  106.36  402.07  107.74
  415.45  107.04  522.79     107  588.31  109.27  602.65  108.72  635.83  108.89
  808.63112.4918  808.75112.4926  939.78  113.02 1002.75  112.81 1174.08  116.65
#Mann= 5 ,-1 , 0
       0     .09       0  326.06     .05       0  342.74     .09       0
  808.63     .09       0  808.75    .065       0
Bank Sta=326.06,342.74
XS Rating Curve= 0 ,0
Exp/Cntr=0.3,0.1

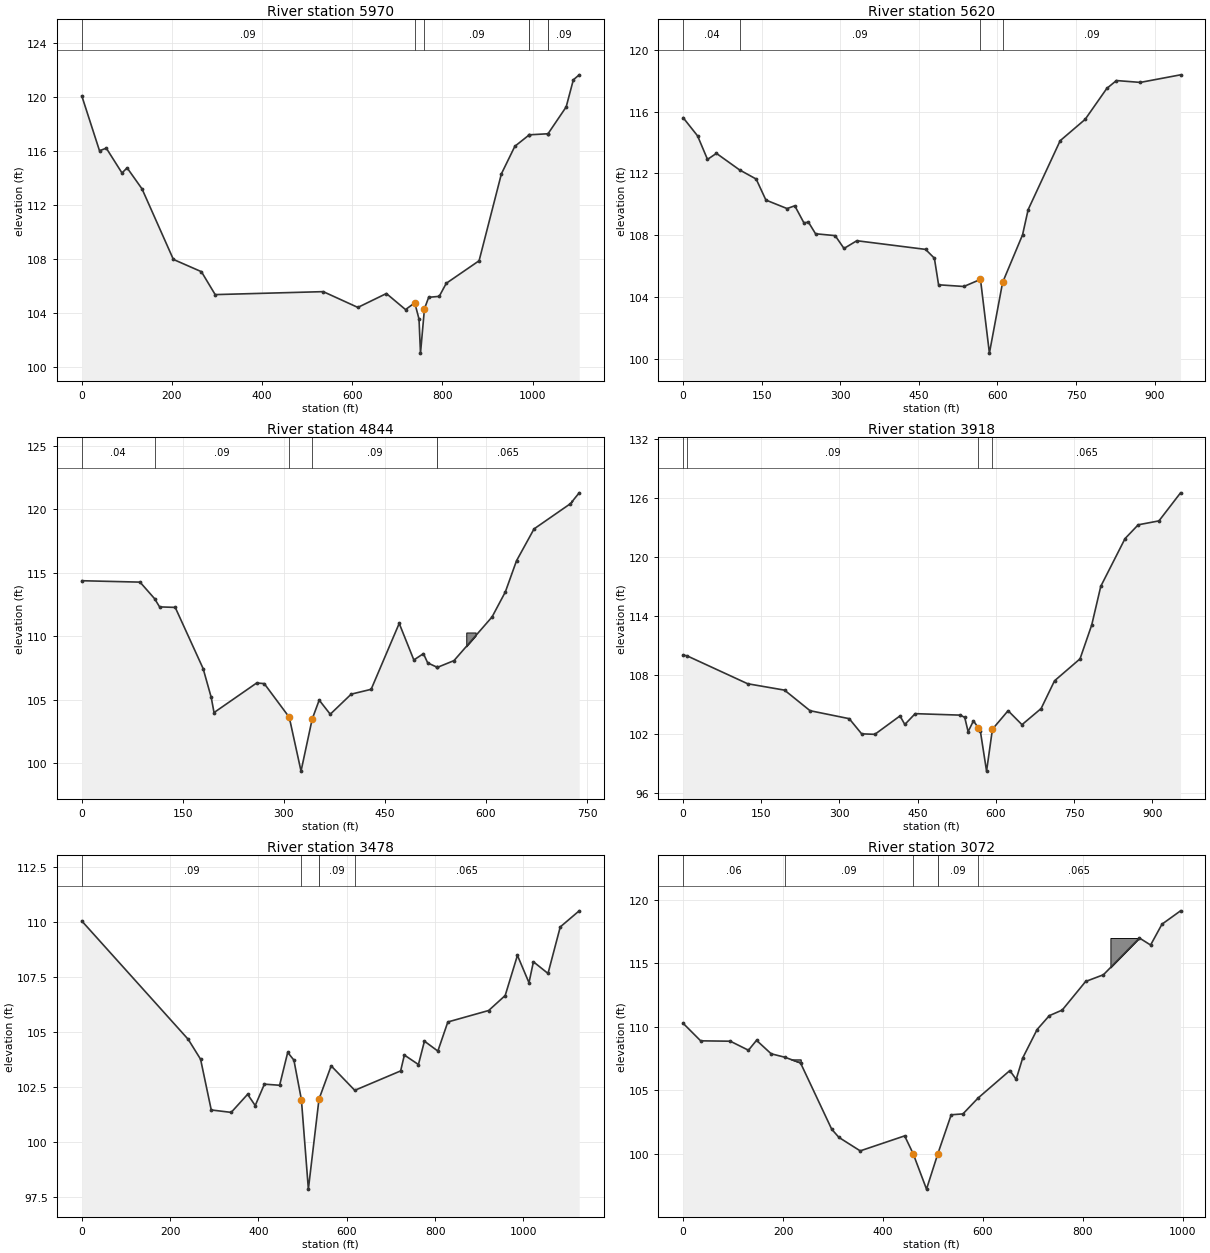
Type RM Length L Ch R = 1 ,5970    ,292.12,350.06,392.02
XS GIS Cut Line= 2
2319538.96684654736456.8076113612318435.70327944736447.779267937
#Sta/Elev= 30
       0  120.09    39.3  116.02   54.39  116.21   89.19  114.37  100.55  114.75
  133.63  113.19  203.16  107.96  265.33  107.05  295.89  105.35  535.58  105.57
  612.35   104.4  675.63  105.43  718.07  104.24  738.55  104.74  747.98  103.54
  751.28  101.01  760.06   104.3  769.43  105.15   792.8  105.22  808.49  106.19
  881.24  107.86  930.76  114.31  960.56  116.35   992.2  117.19  992.31   117.2
 1034.23  117.28 1034.34  117.29  1074.4  119.27 1090.31  121.28  1103.3  121.65
#Mann= 7 ,-1 , 0
       0     .09       0  738.55     .05       0  760.06     .09       0
   992.2     .09       0  992.31    .065       0 1034.23       0       0
 1034.34     .09       0
Bank Sta=738.55,760.06
XS Rating Curve= 0 ,0
Exp/Cntr=0.3,0.1

Type RM Length L Ch R = 1 ,5620    ,490.34,776.84,510.12
BEGIN DESCRIPTION:
Survyed Section
END DESCRIPTION:
XS GIS Cut Line= 6
2319395.86871339736328.500671402 2318932.8477173736176.407714844
2318903.57611088736159.0275268552318876.63208011736139.732299834
2318807.59747314736096.6940917972318530.14031985735951.299926758
#Sta/Elev= 30
       0  115.61   27.62  114.43    46.5  112.91   63.58   113.3  107.77  112.23
  139.42  111.64  158.02  110.28  198.45  109.73  213.13  109.91   230.5  108.81
  239.24  108.85  252.77   108.1   290.2  107.98  307.12  107.15  331.58  107.65
  462.75  107.09  479.62  106.52 487.612   104.8  535.93  104.69   567.6  105.15
  584.65  100.38 609.834  104.95  647.91  108.03  658.61  109.66  719.74  114.12
  767.42   115.5  808.73   117.5  827.12  118.01  872.75  117.89  949.51  118.38
#Mann= 4 ,-1 , 0
       0     .04       0  107.77     .09       0   567.6     .05       0
 609.834     .09       0
Bank Sta=567.6,609.834
XS Rating Curve= 0 ,0
Exp/Cntr=0.3,0.1

Type RM Length L Ch R = 1 ,4844    ,784.89,925.07,839.21
XS GIS Cut Line= 2
2319415.51470949735851.7606811522318765.89093021735500.754272461
#Sta/Elev= 30
       0  114.37   86.45  114.26  108.03  112.96   115.5  112.31  138.71  112.27
  180.15  107.45  192.11  105.19  196.32  103.99  259.64  106.32  270.85  106.27
  307.98  103.62  325.46   99.38  342.02  103.48  352.43  104.97  368.84  103.86
  399.93  105.44  429.52  105.82  471.19  111.01  492.94  108.13  507.16  108.63
  513.49   107.9  527.87  107.55  528.02 107.552  552.52  108.08  609.04  111.52
  628.76  113.49  645.32  115.94  671.36  118.45  725.21  120.43  738.39  121.29
#Mann= 6 ,-1 , 0
       0     .04       0  108.03     .09       0  307.98     .05       0
  342.02     .09       0  527.87     .09       0  528.02    .065       0
#Block Obstruct= 2 ,-1
  570.75   584.7110.2955  726.35  728.53120.6857
Bank Sta=307.98,342.02
XS Rating Curve= 0 ,0
Exp/Cntr=0.3,0.1

Type RM Length L Ch R = 1 ,3918    ,325.94,440.77,441.96
XS GIS Cut Line= 2
2319900.11309816735359.3038940582319203.33911131 734707.06072998
#Sta/Elev= 30
       0  110.02    7.35  109.95  123.79  107.11  194.61  106.46  243.54  104.37
  318.69  103.56  342.53  102.02   367.9  101.97  416.13  103.84  425.37  102.97
  445.26  104.07  531.94  103.92  540.32  103.69  546.84  102.24  557.08  103.34
  566.54  102.62  570.16  102.35  582.22   98.23  593.48  102.49  623.52  104.37
  650.19  102.95  686.91  104.59  712.64  107.41  761.55  109.64  783.98  113.08
  801.36  117.01  847.94  121.86  873.14  123.26  913.02  123.66  954.42  126.51
#Mann= 4 ,-1 , 0
       0     .04       0    7.35     .09       0  566.54     .05       0
  593.48    .065       0
Bank Sta=566.54,593.48
XS Rating Curve= 0 ,0
Exp/Cntr=0.3,0.1

Type RM Length L Ch R = 1 ,3478    ,377.2,406.11,403.62
XS GIS Cut Line= 2
2320148.96087648 735267.623107942319575.30108643734298.426330566
#Sta/Elev= 30
       0  110.03  241.07  104.66  268.97  103.76  293.13  101.46  338.31  101.35
  375.46  102.17  392.69  101.66  413.47  102.63  447.94  102.58  466.26  104.07
  480.27  103.72  497.24  101.93  513.03   97.87  537.09  101.95  564.65  103.46
  618.08  102.35  721.93  103.23  730.38  103.95  762.26  103.52  775.82  104.58
  806.22  104.13   828.8  105.45  921.27  105.97  958.67  106.65   986.4  108.47
 1012.54  107.23 1022.58  108.18 1055.61  107.65 1083.36  109.76 1126.25  110.49
#Mann= 5 ,-1 , 0
       0     .09       0  497.24     .05       0  537.09     .09       0
  537.09     .09       0  618.08    .065       0
Bank Sta=497.24,537.09
XS Rating Curve= 0 ,0
Exp/Cntr=0.3,0.1

Type RM Length L Ch R = 1 ,3072    ,372.86,391.39,391.58
XS GIS Cut Line= 2
2320460.67547607735094.7395019532320015.36889648734204.126098648
#Sta/Elev= 30
       0  110.26   35.07  108.88   94.45  108.85  130.77  108.14  146.93  108.92
  176.25  107.86  203.53  107.59  235.02  107.14  297.36  101.93  311.89  101.28
   354.5  100.22  443.44   101.4  460.46     100  487.21   97.21  510.02  100.01
  536.65  103.06  560.14  103.13  590.47  104.38  654.01  106.54  666.69  105.85
  679.65  107.52  708.61  109.77  732.99  110.86  758.84   111.3  805.74  113.55
  841.39  114.08  913.48  116.97  935.79  116.42  958.61  118.06  995.74  119.11
#Mann= 6 ,-1 , 0
       0     .06       0  203.53     .09       0  460.46     .05       0
  510.02     .09       0  510.02     .09       0  590.47    .065       0
#Block Obstruct= 2 ,-1
  215.29  235.41107.4216  855.35  914.15116.9745
Bank Sta=460.46,510.02
XS Rating Curve= 0 ,0
Exp/Cntr=0.3,0.1

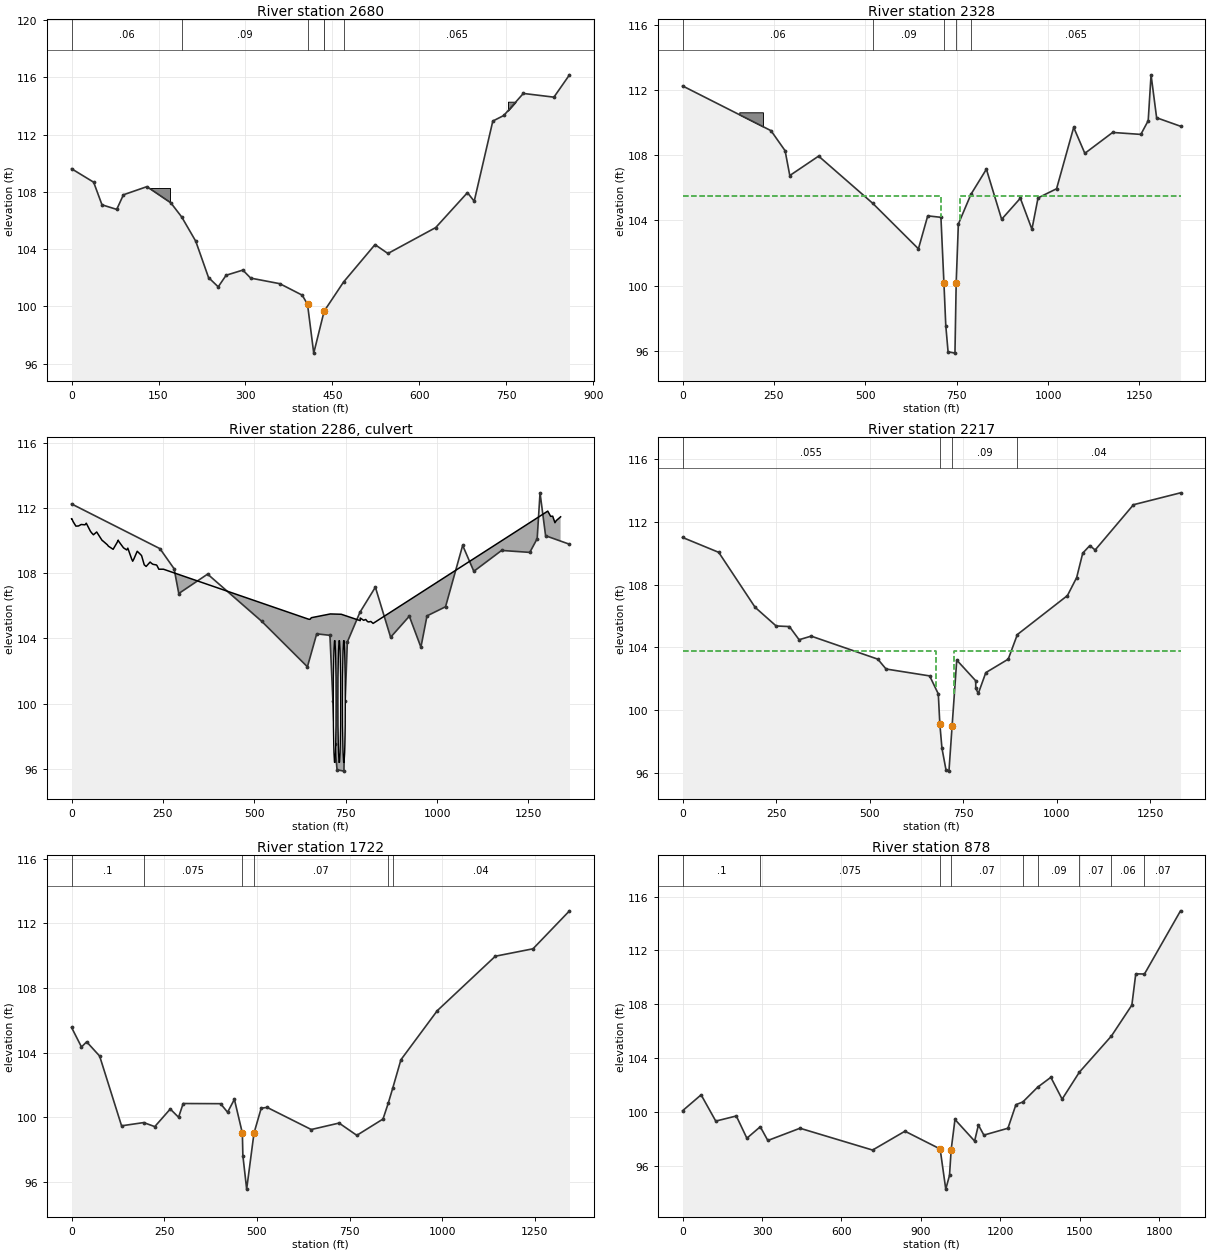
Type RM Length L Ch R = 1 ,2680    ,267.04,352.44,366.75
XS GIS Cut Line= 2
 2320727.8594971734845.8914795072320405.66711426734049.578491211
#Sta/Elev= 30
       0  109.61    38.1  108.67   52.49  107.09    77.9  106.77   89.49  107.79
  130.03  108.36  171.41  107.22  190.02  106.24  214.22  104.55  236.29  102.01
  253.01  101.36  266.63  102.17  295.49  102.53  309.04  101.97  359.31  101.58
   397.9  100.78  407.07  100.14  417.78   96.73  435.74   99.66  469.28   101.7
  523.49  104.31  545.77  103.69   628.2   105.5  682.98  107.94  694.62  107.34
  726.73  112.94  745.67  113.33  779.38  114.87  832.14  114.61  859.02  116.17
#Mann= 6 ,-1 , 0
       0     .06       0  190.02     .09       0  407.07     .05       0
  435.74     .09       0  435.74     .09       0  469.28    .065       0
#Block Obstruct= 2 ,-1
  132.39  169.33108.2773  752.85  766.08114.2934
Bank Sta=407.07,435.74
XS Rating Curve= 0 ,0
Exp/Cntr=0.5,0.3

Type RM Length L Ch R = 1 ,2328    ,154.58,111.13,130.08
BEGIN DESCRIPTION:
Survyed Cross Sections
END DESCRIPTION:
XS GIS Cut Line= 6
2320849.88460566735031.6181022232320859.51367188734360.793090835
2320862.59368899 734324.755676272320869.11352542734296.894104019
2320871.10089116734243.6065063482321001.70403501733685.524073541
#Sta/Elev= 30
       0  112.24  241.84   109.5  280.51  108.27  293.32  106.75  372.22  107.94
  520.15  105.05  645.28  102.26 670.711  104.28  706.87  104.19  715.08  100.15
  720.11   97.56  726.39   95.95  745.24   95.87   748.6  100.19 754.556  103.78
 788.995   105.6  831.25  107.14  872.92  104.07  924.12  105.36  955.83  103.46
  972.54  105.38 1023.24  105.94 1070.07   109.7 1100.61  108.11 1176.65  109.39
 1253.78  109.27 1273.96  110.11 1281.76  112.92 1296.98  110.29 1362.37  109.77
#Mann= 5 ,-1 , 0
       0     .06       0  520.15     .09       0  715.08     .05       0
   748.6     .09       0 788.995    .065       0
#XS Ineff= 2 , 0
       0  706.25   105.5  758.75       0   105.5
Permanent Ineff=
       F       F
#Block Obstruct= 1 ,-1
  155.12  219.83110.6243
Bank Sta=715.08,748.6
XS Rating Curve= 0 ,0
Exp/Cntr=0.5,0.3

Type RM Length L Ch R = 2 ,2286    ,,,
BEGIN DESCRIPTION:
Tilghman Road
END DESCRIPTION:
Bridge Culvert--1,0,-1,-1, 0
Deck Dist Width WeirC Skew NumUp NumDn MinLoCord MaxHiCord MaxSubmerge Is_Ogee
42,30,2.6,0, 58, 58, , , 0.98, 0, 1,1,,
       0     .66     4.1   11.88   19.19   26.24   36.89   40.21   51.71   55.23
   59.84   68.74   82.83   84.13   84.89   97.71  100.88   113.7  124.65  127.67
  128.92  142.09  150.94  153.89  164.36  167.21  170.33  179.59  188.88   191.6
  198.85  204.04  214.96  219.28  222.82  232.24   233.8  238.75  251.39   648.3
  652.41 656.093 708.089 737.945  789.73  789.76  799.16  804.91  809.78  813.15
  818.75  824.97 1302.89 1310.81  1316.4  1322.6 1326.13 1338.05
  111.33  111.34  111.16  110.88  110.89  110.98  110.96  111.06  110.56  110.46
  110.35  110.52  110.03  109.99  109.99  109.74  109.65  109.46  109.88  110.02
  109.95  109.55  109.42  109.53  108.87  108.73  108.86  109.34  109.14  109.07
  108.51  108.41  108.68  108.59  108.54   108.5  108.46  108.24  108.24  105.18
  105.17  105.27   105.5  105.48  105.09  105.25  105.11  105.16  105.03  105.01
  105.04  104.92   111.8  111.48  111.49  111.09  111.22  111.45
                                                                                
                                                                                
                                                                                
                                                                                
                                                                                
                                                                
       0     .66     4.1   11.88   19.19   26.24   36.89   40.21   51.71   55.23
   59.84   68.74   82.83   84.13   84.89   97.71  100.88   113.7  124.65  127.67
  128.92  142.09  150.94  153.89  164.36  167.21  170.33  179.59  188.88   191.6
  198.85  204.04  214.96  219.28  222.82  232.24   233.8  238.75  251.39   648.3
  652.41 656.093 708.089 737.945  789.73  789.76  799.16  804.91  809.78  813.15
  818.75  824.97 1302.89 1310.81  1316.4  1322.6 1326.13 1338.05
  111.33  111.34  111.16  110.88  110.89  110.98  110.96  111.06  110.56  110.46
  110.35  110.52  110.03  109.99  109.99  109.74  109.65  109.46  109.88  110.02
  109.95  109.55  109.42  109.53  108.87  108.73  108.86  109.34  109.14  109.07
  108.51  108.41  108.68  108.59  108.54   108.5  108.46  108.24  108.24  105.18
  105.17  105.27   105.5  105.48  105.09  105.25  105.11  105.16  105.03  105.01
  105.04  104.92   111.8  111.48  111.49  111.09  111.22  111.45
                                                                                
                                                                                
                                                                                
                                                                                
                                                                                
                                                                
BR Coef=-1 , 0 , 0 ,, 0 ,,,0.8,0,,0,
WSPro=,,,, 1 ,,,, 0 ,,,, 0 ,,,,-1 ,-1 ,-1 , 0 , 0 , 0 , 0 , 0
Multiple Barrel Culv=1,7.5,,57,0.019,0.5,1,2,1,96.38,96.28, 3,Culvert #1  , 0 ,31
     720     692   732.5   704.5     745     717
Culvert Bottom n=0.019
BC Design=,, 0 ,, 0 ,,,,,,
BC Use User HTab Curves=0
BC User HTab FreeFlow(D)= 0

Type RM Length L Ch R = 1 ,2217    ,419.4,494.3,470.2
BEGIN DESCRIPTION:
Survyed Cross Sections
END DESCRIPTION:
XS GIS Cut Line= 6
2320957.40339763735024.2872755082320977.21807863734325.193908691
 2320975.4343262734310.4575195462320979.81811523734307.663330093
2320997.64947513734247.1945190432321118.23132513733713.651350483
#Sta/Elev= 30
       0  111.01   96.53  110.06  193.77  106.55  249.89  105.36   285.4  105.32
  311.28  104.48  343.57  104.71  521.53  103.24   543.6  102.61 660.039  102.17
  683.17  101.02  687.21   99.12  692.88   97.56  703.71   96.17  711.62   96.09
 720.074   98.98 732.442  103.18 783.111  101.86  783.27  101.37  790.01  101.05
  810.09  102.38  870.01  103.24  894.34  104.81 1028.16   107.3 1052.83  108.45
 1069.05  110.01 1087.94  110.49 1102.19  110.21 1204.53   113.1 1330.27  113.86
#Mann= 4 ,-1 , 0
       0    .055       0  687.21     .05       0 720.074     .09       0
  894.34     .04       0
#XS Ineff= 2 , 0
       0  678.25  103.78     726       0  103.78
Permanent Ineff=
       F       F
Bank Sta=687.21,720.074
XS Rating Curve= 0 ,0
Exp/Cntr=0.5,0.3

Type RM Length L Ch R = 1 ,1722    ,1003.28,844.31,539.64
XS GIS Cut Line= 3
2321126.95599034735068.3461375242321455.46419802734395.470705166
 2321394.2937042733804.155931294
#Sta/Elev= 30
       0  105.56   26.77  104.35   40.71  104.67    75.7  103.79  134.89   99.47
  194.64   99.67  224.47   99.42  266.25  100.51  288.66     100  301.07  100.85
  401.88  100.84  420.93  100.31  439.25  101.11  460.74   99.02  462.12   97.63
  472.35   95.55  492.16   99.02   511.6  100.56  527.62  100.61  646.62   99.24
  721.67   99.64  769.51   98.88  840.19   99.89  854.44  100.88   866.4   101.8
  888.49  103.56  986.61   106.6 1143.18  109.97 1244.85  110.43 1343.26  112.78
#Mann= 6 ,-1 , 0
       0      .1       0  194.64    .075       0  460.74     .05       0
  492.16     .07       0  854.44     .09       0   866.4     .04       0
Bank Sta=460.74,492.16
XS Rating Curve= 0 ,0
Exp/Cntr=0.3,0.1

Type RM Length L Ch R = 1 ,878     ,836.19,877.99,872.83
XS GIS Cut Line= 3
2321926.70355806735240.529749841 2322241.6183227734794.211702123
2321725.06748573733564.005103588
#Sta/Elev= 30
       0   100.1   69.99  101.28  125.33   99.33  202.89   99.71  242.82   98.06
  293.36   98.91  321.95   97.89   443.4    98.8  717.55   97.18  839.85   98.58
  972.69   97.26  993.91   94.28 1008.08    95.3 1014.33   97.21 1028.72   99.45
 1102.83   97.85 1117.23   99.04 1137.85   98.29 1228.79    98.8 1258.87  100.55
 1284.94  100.75 1340.98  101.85 1390.82  102.58 1433.35  100.96 1498.37  102.96
 1619.66  105.65 1696.71  107.94 1711.47  110.26 1744.34  110.25 1880.49  114.94
#Mann= 9 ,-1 , 0
       0      .1       0  293.36    .075       0  972.69     .05       0
 1014.33     .07       0 1284.94     .04       0 1340.98     .09       0
 1498.37     .07       0 1619.66     .06       0 1744.34     .07       0
Bank Sta=972.69,1014.33
XS Rating Curve= 0 ,0
Exp/Cntr=0.3,0.1
Stream Node=Toisnot_Smp_Trib,Main            , 0 , 0 ,Upstream end
Stream Node=Toisnot_Smp_Trib,Main            , 0 , 1 ,Downstream end

Chan Stop Cuts=-1
Use User Specified Reach Order=0