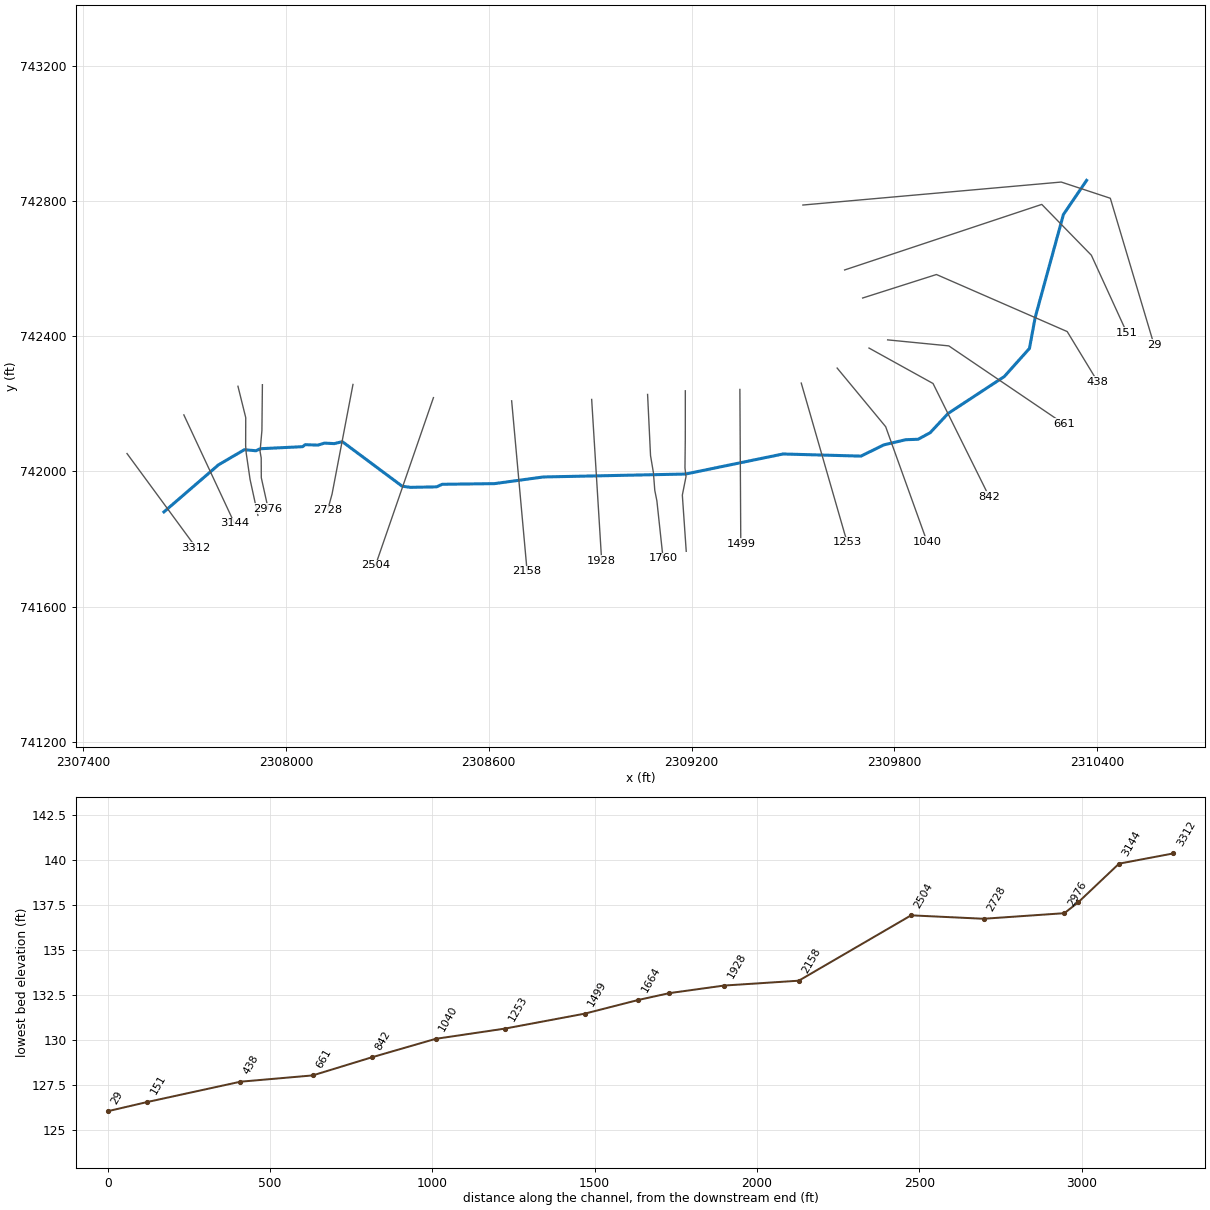
--- dtl_trib_2_tosinot_swp_trib.prj (project) ---

Proj Title=dtl_Trib2_to_Toisnot_Smp_Trib
Current Plan=p01
Default Exp/Contr=0.3,0.1
English Units
Geom File=g02
Flow File=f01
Flow File=f02
Plan File=p01
Plan File=p03
Y Axis Title=Elevation
X Axis Title(PF)=Main Channel Distance
X Axis Title(XS)=Station
BEGIN DESCRIPTION:
END DESCRIPTION:
DSS File=dss
DSS Export Rating Curves= 0
DSS Export Rating Curve Sorted= 0
DSS Export Volume Flow Curves= 0
DXF OffsetX= 0
DXF OffsetY= 0
DXF ScaleX= 1
DXF ScaleY= 10

--- dtl_trib_2_tosinot_swp_trib.p01 (plan) ---

Plan Title=dtl_Tributary 2 to Toisnot Swamp Trib
Program Version=4.00
Short Identifier=dtl_Tributar
Geom File=g02
Flow File=f01
Subcritical Flow
K Sum by GR= 0
Std Step Tol= 0.01
Critical Tol= 0.01
Num of Std Step Trials= 20
Max Error Tol= 0.3
Flow Tol Ratio= 0.001
Split Flow NTrial= 30
Split Flow Tol= 0.02
Split Flow Ratio= 0.02
Log Output Level= 0
Friction Slope Method= 1
Unsteady Friction Slope Method= 2
Unsteady Bridges Friction Slope Method= 1
Parabolic Critical Depth
Global Vel Dist= 0 , 0 , 0
Global Log Level= 0
CheckData=True
Encroach Param=-1 ,10,10, 2
Encroach River=Trib2 to Toisnot
Encroach Reach=1
Encroach Node=3312
       1     192  232.56
Encroach Node=3144
       1     150     223
Encroach Node=3019
       1   170.9  209.46
Encroach Node=2976
       1  169.26  207.83
Encroach Node=2728
       1     155  196.24
Encroach Node=2504
       1  254.33  283.41
Encroach Node=2158
       1  213.18  249.35
Encroach Node=1928
       1     200  246.01
Encroach Node=1760
       1  210.48  249.48
Encroach Node=1664
       1     216     255
Encroach Node=1499
       1     198  242.78
Encroach Node=1253
       1  199.16  229.39
Encroach Node=1040
       1  255.44  285.67
Encroach Node=842
       1  304.25   330.5
Encroach Node=661
       1     315     388
Encroach Node=438
       1     495  557.72
Encroach Node=151
       1     680     723
Encroach Node=29
       1   812.1  858.01
Computation Interval=1HOUR
Output Interval=1HOUR
Run HTab= 0
Run UNet= 0
Run PostProcess= 0
Run WQNet= 0
UNET Theta= 1
UNET Theta Warmup= 1
UNET ZTol= 0.02
UNET ZSATol= 0.05
UNET MxIter= 20
UNET MaxInSteps= 0
UNET DtIC= 0
UNET DtMin= 0
UNET MaxCRTS= 20
UNET WFStab= 2
UNET SFStab= 1
UNET WFX= 1
UNET SFX= 1
UNET DSS MLevel= 4
UNET DZMax Abort= 100
UNET Convert EG Bridges= 0
UNET Use Existing IB Tables=-1
UNET Froude Reduction=False
UNET Froude Limit= 1
UNET Froude Power= 10
UNET Time Slicing=0,0, 5
Instantaneous Interval=1HOUR
DSS File=dss
Write IC File= 0
Echo Input=False
Echo Output=False
Write Detailed= 0
Detailed Automatic Start=False, 10
WQ ULTIMATE=-1
WQ Max Comp Step=1HOUR
WQ Output Interval=15MIN
WQ Output Selected Increments= 0
WQ Output face flow=0
WQ Output face velocity=0
WQ Output face area=0
WQ Output face dispersion=0
WQ Output cell volume=0
WQ Output cell surface area=0
WQ Output cell continuity=0
WQ Output face conc=0
WQ Output face dconc_dx=0
WQ Output face courant=0
WQ Output face peclet=0
WQ Output face adv mass=0
WQ Output face disp mass=0
WQ Output cell mass=0
WQ Output cell source sink temp=0
WQ Output cell source sink nsm=0
WQ Output MaxMinRange=-1
WQ Daily Max Min Mean=-1
WQ Daily Range=0
WQ Daily Time=0
WQ Create Restart=0
WQ Fixed Restart=0
WQ System Summary=False
Sorting and Armoring Iterations= 10
XS Update Threshold= 0.02
Hydraulics Update Threshold= 0.02
Energy Slope Method= 1
Volume Change Method= 0
XS Weighting Method= 0
Number of US Weighted Cross Sections= 1
Number of DS Weighted Cross Sections= 1
Upstream XS Weight=0.25
Main XS Weight=0.5
Downstream XS Weight=0.25
Number of DS XS's Weighted with US Boundary= 1
Upstream Boundary Weight= 1
Weight of XSs Associated with US Boundary= 0
Number of US XS's Weighted with DS Boundary= 1
Downstream Boundary Weight= 0.5
Weight of XSs Associated with DS Boundary= 0.5
Sediment Output Level= 4
Mass or Volume Output= 0
Output Increment Type= 1
Profile and TS Output Increment= 10
XS Output Flag= 0
XS Output Increment= 10
Disregard all LS=0
Disregard all Conn=0
Disregard all Breaches=0
Disregard all Pumps=0

--- dtl_trib_2_tosinot_swp_trib.p03 (plan) ---

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Plan Title=dtl_Trib 2 to Toisnot Swamp Trib FUTURE
Program Version=3.13
Short Identifier=FUTURE
Geom File=g02
Flow File=f02

--- dtl_trib_2_tosinot_swp_trib.f01 (steady flow) ---

Flow Title=dtl_Trib 2 to Toisnot Swamp Trib
Program Version=3.13
Number of Profiles= 6
Profile Names=100yr,FW,10yr,25yr,50yr,500yr
River Rch & RM=Trib2 to Toisnot,1               ,3312
     330     330     130     200     260     560
Boundary for River Rch & Prof#=Trib2 to Toisnot,1               , 1
Up Type= 0
Dn Type= 3
Dn Slope=0.00418
Boundary for River Rch & Prof#=Trib2 to Toisnot,1               , 2
Up Type= 0
Dn Type= 3
Dn Slope=0.00418
Boundary for River Rch & Prof#=Trib2 to Toisnot,1               , 3
Up Type= 0
Dn Type= 3
Dn Slope=0.00418
Boundary for River Rch & Prof#=Trib2 to Toisnot,1               , 4
Up Type= 0
Dn Type= 3
Dn Slope=0.00418
Boundary for River Rch & Prof#=Trib2 to Toisnot,1               , 5
Up Type= 0
Dn Type= 3
Dn Slope=0.00418
Boundary for River Rch & Prof#=Trib2 to Toisnot,1               , 6
Up Type= 0
Dn Type= 3
Dn Slope=0.00418
DSS Import GetInterval= 0
DSS Import GetPeak= 0
DSS Import FillOption= 0

--- dtl_trib_2_tosinot_swp_trib.f02 (steady flow) ---

Flow Title=dtl_Trib 2 to Toisnot Swamp Trib FUTURE
Program Version=3.13
Number of Profiles= 3
Profile Names=QF10%,QF20%,QF35%
River Rch & RM=Trib2 to Toisnot,1               ,3312
     600     760     930
Boundary for River Rch & Prof#=Trib2 to Toisnot,1               , 1
Up Type= 0
Dn Type= 3
Dn Slope=0.00418
Boundary for River Rch & Prof#=Trib2 to Toisnot,1               , 2
Up Type= 0
Dn Type= 3
Dn Slope=0.00418
Boundary for River Rch & Prof#=Trib2 to Toisnot,1               , 3
Up Type= 0
Dn Type= 3
Dn Slope=0.00418
DSS Import GetInterval= 0
DSS Import GetPeak= 0
DSS Import FillOption= 0

--- dtl_trib_2_tosinot_swp_trib.g02 (geometry) ---

Geom Title=dtl_Trib2_to_Toisnot_Smp_Trib
Program Version=4.00

River Reach=Trib2 to Toisnot,1
Reach XY= 30
 2307639.1985847  741879.9805703 2307800.4745923   742019.162377
 2307877.0244431  742063.9372317 2307911.6394906  742060.9209828
    2307923.8049     742066.8833  2308049.525157  742072.9859786
  2308056.850333  742078.8748456 2308094.7688913  742077.5821675
 2308114.0154322  742083.4710345 2308143.0288745  742082.0347254
 2308167.0152352  742087.7799615 2308344.0306968  741955.9651028
 2308368.6865753  741952.6776524  2308445.477552  741954.0941857
 2308462.5288424  741961.6976439 2308617.0344133  741963.6680203
 2308761.5369059  741983.3605234  2309182.615477  741992.0583633
 2309470.5923012  742051.3656923 2309701.2998489  742045.0477294
  2309768.759388  742078.2679859 2309833.5694589  742093.5533799
 2309870.1643501  742094.8967782  2309905.917357  742114.2227279
 2309959.0637185  742171.2342793 2310125.2668855  742280.4258948
 2310199.6717916  742363.5274783  2310216.766124  742455.5703925
 2310300.1667298  742759.7094461 2310368.7206379  742860.6428163

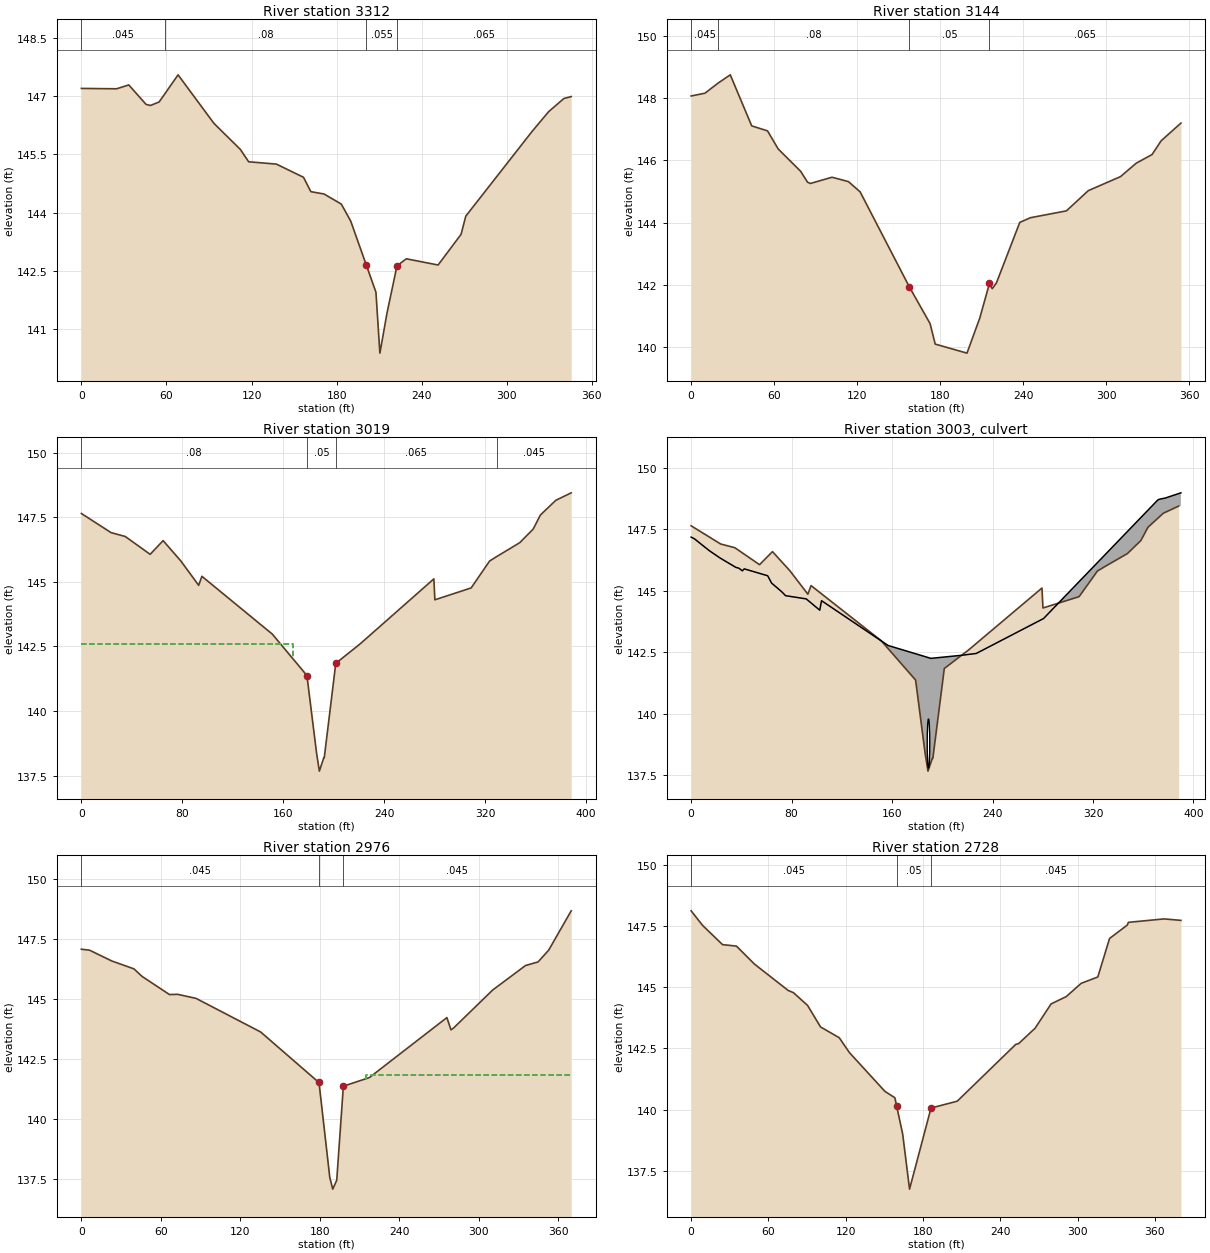
Type RM Length L Ch R = 1 ,3312    ,201.1,167.59,138.66
XS GIS Cut Line= 2
 2307529.9909682  742052.6414659 2307734.4310592   741774.226342
#Sta/Elev= 30
       0   147.2   24.79  147.19   33.41  147.29   45.56  146.79   48.67  146.76
   54.77  146.85   59.03  147.07   68.17  147.55   93.45   146.3  112.05  145.63
  117.95  145.31  137.51  145.25  156.62  144.91   161.8  144.54   171.1  144.48
  183.29  144.22  189.94  143.78     201  142.64  207.71  141.95   210.5  140.38
   215.5  141.41  222.56  142.63  229.17  142.81  251.53  142.65  267.74  143.44
  271.08  143.91  317.78  146.09  329.48   146.6  340.24  146.94  345.41  146.99
#Mann= 4 ,-1 , 0
       0    .045       0   59.03     .08       0     201    .055       0
  222.56    .065       0
Bank Sta=201,222.56
XS Rating Curve= 0 ,0
Exp/Cntr=0.3,0.1

Type RM Length L Ch R = 1 ,3144    ,186.65,125.29,75.32
XS GIS Cut Line= 2
  2307698.116043  742166.9665169 2307847.8303862  741846.3820589
#Sta/Elev= 30
       0  148.07      10  148.16   19.67  148.49   28.28  148.75   43.76  147.11
   55.19  146.95   62.86  146.37   79.14  145.65    84.1   145.3   86.17  145.26
  101.78  145.46  113.63  145.32  122.09  144.99  157.61  141.94   172.6  140.76
  176.33   140.1  199.27  139.81  208.55  140.94   215.5  142.05   217.5  141.88
   220.5  142.06  237.42  144.01  245.13  144.16  271.11  144.38  286.92  145.03
  310.18  145.48  321.49  145.91  332.97  146.19  339.52  146.63  353.82   147.2
#Mann= 4 ,-1 , 0
       0    .045       0   19.67     .08       0  157.61     .05       0
   215.5    .065       0
Bank Sta=157.61,215.5
XS Rating Curve= 0 ,0
Exp/Cntr=0.5,0.3

Type RM Length L Ch R = 1 ,3019    ,69.46,42.92,34.47
BEGIN DESCRIPTION:
surveyed section
END DESCRIPTION:
XS GIS Cut Line= 6
 2307858.1711143  742251.7015546 2307881.1918644  742158.9661601
    2307880.9346     742075.6682     2307882.763     742052.9029
    2307894.0263     741975.9314 2307917.2093114  741869.7288495
#Sta/Elev= 26
       0  147.64   23.52   146.9   34.78  146.75   54.48  146.06   64.77  146.59
    78.7  145.81   92.96  144.86  95.498  145.21 151.361  142.97 178.751  141.37
 186.362  138.38 188.602  137.67 192.109  138.19  192.49  138.19 201.607  141.84
  220.83  142.59 279.356  145.11  280.17   144.3  308.94  144.76  323.52   145.8
  329.05  145.97   347.4  146.51  358.13  147.04  363.78  147.58     376  148.15
  388.21  148.44
#Mann= 4 ,-1 , 0
       0     .08       0 178.751     .05       0 201.607    .065       0
  329.05    .045       0
#XS Ineff= 2 , 0
       0     168   142.6     220       0   142.4
Permanent Ineff=
       F       F
Bank Sta=178.751,201.607
XS Rating Curve= 0 ,0
Exp/Cntr=0.5,0.3

Type RM Length L Ch R = 2 ,3003    ,,,
BEGIN DESCRIPTION:
surveyed section str_284
END DESCRIPTION:
Bridge Culvert--1,0,-1,-1, 0
Deck Dist Width WeirC Skew NumUp NumDn MinLoCord MaxHiCord MaxSubmerge Is_Ogee
13,13,2.6,0, 24, 24, , , 0.98, 0, 1,1,,
       0    2.66   14.46   23.08   35.62   37.92   40.82    42.3   60.94   64.09
   71.93    75.2   91.63  102.41  103.85  156.85   190.9  215.26  227.05  280.63
   371.6  372.94  377.68  390.02
  147.18  147.11  146.63  146.33  145.95  145.92  145.81  145.89  145.61  145.31
  144.97   144.8  144.67  144.21 144.596 142.776 142.253 142.377 142.452 143.871
  148.69  148.72  148.77  148.98
                                                                                
                                                                                
                                
       0    2.66   14.46   23.08   35.62   37.92   40.82    42.3   60.94   64.09
   71.93    75.2   91.63  102.41  103.85  156.85   190.9  215.26  227.05  280.63
   371.6  372.94  377.68  390.02
  147.18  147.11  146.63  146.33  145.95  145.92  145.81  145.89  145.61  145.31
  144.97   144.8  144.67  144.21 144.596 142.776 142.253 142.377 142.452 143.871
  148.69  148.72  148.77  148.98
                                                                                
                                                                                
                                
BR Coef=-1 , 0 , 0 ,, 0 ,,,0.8,-1,,0,
WSPro=,,,, 1 ,,,, 0 ,,,, 0 ,,,,-1 ,-1 ,-1 , 0 , 0 , 0 , 0 , 0
Culvert=1,2,,22,0.013,0.2,1,1,3,137.7922,189,137.1588,190,Culvert #1  , 0 ,13
Culvert Bottom n=0.013
BC Design=,, 0 ,, 0 ,,,,,,
BC Use User HTab Curves=0
BC User HTab FreeFlow(D)= 0

Type RM Length L Ch R = 1 ,2976    ,265.41,248.7,204.88
BEGIN DESCRIPTION:
surveyed section
END DESCRIPTION:
XS GIS Cut Line= 6
 2307930.4961652  742256.3130235 2307929.0721001     742120.9967
    2307923.5963     742058.9514    2307926.9372     742039.5737
 2307927.2395001     741981.0694 2307947.5792629  741889.3427765
#Sta/Elev= 24
       0  147.06    6.15  147.02   22.93  146.57   39.72  146.24   45.72  145.93
   66.52  145.17   72.68  145.18   86.61  145.01 135.366  143.61 179.263  141.51
 179.428  141.51  187.58  137.55 189.821  137.06  192.83  137.43  197.83  141.35
 217.499  141.71  276.02  144.21  279.09   143.7  280.97  143.77  310.62  145.36
  335.41  146.38  344.88  146.53  352.89  147.02   369.9  148.66
#Mann= 3 ,-1 , 0
       0    .045       0 179.263     .05       0  197.83    .045       0
#XS Ineff= 2 , 0
       0     165   141.8     215       0   141.8
Permanent Ineff=
       F       F
Bank Sta=179.263,197.83
XS Rating Curve= 0 ,0
Exp/Cntr=0.5,0.3

Type RM Length L Ch R = 1 ,2728    ,239.06,223.45,195.56
XS GIS Cut Line= 3
 2308198.4562658   742257.081557 2308136.5407392   741932.616706
 2308123.1362322  741884.5163911
#Sta/Elev= 30
       0  148.11    8.81  147.52    24.4  146.73    35.2  146.67   49.06  145.94
   75.35  144.86   79.42  144.77   90.39  144.25  100.48  143.37     115  142.93
  122.94  142.32  150.47  140.74  158.18  140.48  159.52  140.15  164.23     139
  169.57  136.75  186.24  140.06  206.61  140.34  252.07  142.66  254.27  142.69
  267.07  143.32  279.45  144.31  291.24  144.61   302.8  145.15  315.72  145.41
  324.84  146.98  338.62  147.53  339.47  147.64  367.22  147.78  380.25  147.72
#Mann= 3 ,-1 , 0
       0    .045       0  159.52     .05       0  186.24    .045       0
Bank Sta=159.52,186.24
XS Rating Curve= 0 ,0
Exp/Cntr=0.3,0.1

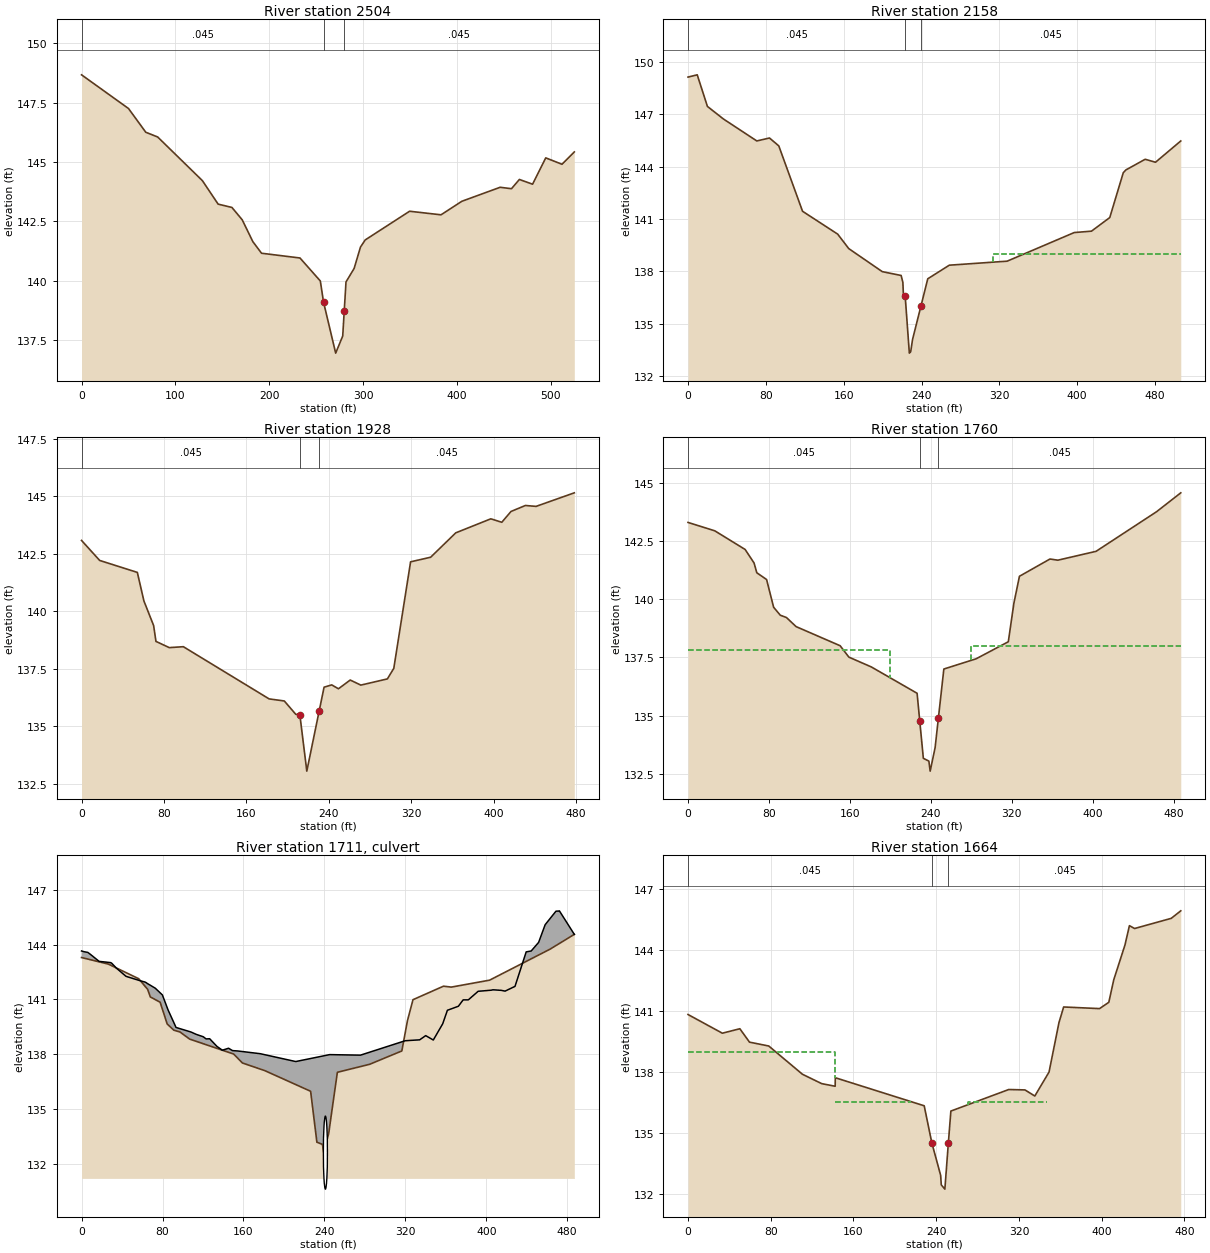
Type RM Length L Ch R = 1 ,2504    ,239.15,345.87,429.96
XS GIS Cut Line= 2
 2308436.5213718  742218.0765396  2308265.048412  741722.0537242
#Sta/Elev= 30
       0  148.67   50.01  147.25    68.4  146.25   81.07  146.05  128.71  144.21
  145.46  143.22  160.17  143.08  171.11  142.56  182.43  141.64  191.71  141.15
  232.66  140.95  254.33  139.98  257.73  139.09  270.67  136.94  278.16  137.66
  279.78  138.72  281.66  139.94  290.33  140.51  297.08  141.41  302.09  141.71
  349.38  142.92  382.88  142.77  405.05  143.34  445.84  143.93  457.91  143.87
  466.33  144.26  480.38  144.06  494.41  145.17   511.7   144.9  524.83  145.42
#Mann= 3 ,-1 , 0
       0    .045       0  257.73     .05       0  279.78    .045       0
Bank Sta=257.73,279.78
XS Rating Curve= 0 ,0
Exp/Cntr=0.3,0.1

Type RM Length L Ch R = 1 ,2158    ,236.13,230.22,222.75
XS GIS Cut Line= 2
 2308667.8614747  742208.6615354 2308713.5914951  741704.2863109
#Sta/Elev= 30
       0  149.13    9.48  149.26   19.93  147.45   36.36  146.73   70.71  145.47
    83.7  145.64   93.27  145.19  117.71  141.44  153.83  140.13  165.21   139.3
  199.65  137.98  219.04  137.76  220.83  137.36  221.32  136.72  223.18  136.59
  227.48  133.31  228.85  133.39   230.8   134.1  239.35     136   246.4  137.57
  268.55  138.35     328  138.58  396.92  140.22  414.67   140.3  433.46  141.08
  447.34  143.65  450.04  143.81  469.85  144.42  480.48  144.25  506.44  145.47
#Mann= 3 ,-1 , 0
       0    .045       0  223.18     .05       0  239.35    .045       0
#XS Ineff= 2 , 0
       0                  313.54       0     139
Permanent Ineff=
       F       F
Bank Sta=223.18,239.35
XS Rating Curve= 0 ,0
Exp/Cntr=0.3,0.1

Type RM Length L Ch R = 1 ,1928    ,165.84,168.3,181.14
XS GIS Cut Line= 2
 2308904.5815801  742212.6965372 2308934.1715933  741735.2213246
#Sta/Elev= 30
       0  143.07   17.59   142.2   54.16  141.68   60.53  140.44   69.97  139.37
   72.24  138.68   85.17  138.41   98.82  138.45   182.1  136.18  196.84  136.09
  207.98  135.51  211.94  135.49  218.69  133.04  230.62  135.64  235.46  136.69
  242.89  136.79  249.39  136.62  260.83     137  271.15  136.78  296.93  137.05
  303.15  137.51  319.44  142.14  338.92  142.34  363.29   143.4  397.34  144.01
     408  143.86  416.95  144.33  430.93  144.59  441.25  144.55  478.39  145.14
#Mann= 3 ,-1 , 0
       0    .045       0  211.94     .05       0  230.62    .045       0
Bank Sta=211.94,230.62
XS Rating Curve= 0 ,0
Exp/Cntr=0.5,0.3

Type RM Length L Ch R = 1 ,1760    ,111.2,95.84,70.88
BEGIN DESCRIPTION:
surveyed xs
END DESCRIPTION:
XS GIS Cut Line= 6
 2309070.0166538  742227.4915438    2309078.7286     742046.5914
    2309087.2915     741995.8423    2309091.2785     741943.9318
    2309097.4965     741912.7606 2309115.7466741  741743.2913282
#Sta/Elev= 30
       0  143.29   26.47  142.93   56.45  142.13   65.27  141.55   67.99  141.13
   77.66  140.84   84.62  139.65   91.18  139.31   97.28  139.21  106.82  138.82
  150.34     138  159.01  137.51 181.176  137.09 226.398  135.96  229.05  134.76
 232.581  133.17 238.029  133.05 239.322  132.62 244.219  133.63  247.43  134.89
 252.841     137 284.782  137.44  316.55  138.17  322.05  139.82  327.56  140.98
   357.7  141.72  365.48  141.67  403.28  142.05   463.1  143.75     487  144.56
#Mann= 3 ,-1 , 0
       0    .045       0  229.05     .05       0  247.43    .045       0
#XS Ineff= 2 , 0
       0     200   137.8     280       0     138
Permanent Ineff=
       F       F
Bank Sta=229.05,247.43
XS Rating Curve= 0 ,0
Exp/Cntr=0.5,0.3

Type RM Length L Ch R = 2 ,1711    ,,,
BEGIN DESCRIPTION:
surveyed section
END DESCRIPTION:
Bridge Culvert--1,0,-1,-1, 0
Deck Dist Width WeirC Skew NumUp NumDn MinLoCord MaxHiCord MaxSubmerge Is_Ogee
43,12,2.6,0, 59, 59, , , 0.98, 0, 2,2,,
       0    2.46    6.25    9.08   17.35   27.58    28.9   29.96   34.42   43.93
   58.41   62.54   63.32   64.24   64.95   72.85   79.89    85.5   92.39   93.31
   96.84   108.1  113.33  120.23  123.13  126.61  133.82  139.16  145.26  149.18
  154.33  176.62  211.67   245.2  275.63  319.81  334.17  340.13  347.63  356.94
  361.57  372.41  377.17  382.23  391.96  404.87  406.33  407.44  414.93  418.58
  428.39  439.43   444.4  451.72  458.18  468.85  472.07  472.24     487
  143.65  143.61  143.57  143.45  143.08  143.02  143.01  142.97  142.71  142.26
  142.01  141.95  141.93   141.9  141.87  141.61  141.24  140.42  139.58  139.46
   139.4  139.21  139.08  138.95  138.83  138.84  138.42  138.21  138.32  138.19
  138.17  138.02  137.59  137.97  137.94  138.73  138.78  139.01  138.77  139.66
   140.4  140.62  140.97  140.97  141.44   141.5  141.52  141.52  141.49  141.45
  141.71   143.6  143.65  144.12  145.09  145.83  145.84  145.85  144.56
                                                                                
                                                                                
                                                                                
                                                                                
                                                                                
                                                                        
       0    2.46    6.25    9.08   17.35   27.58    28.9   29.96   34.42   43.93
   58.41   62.54   63.32   64.24   64.95   72.85   79.89    85.5   92.39   93.31
   96.84   108.1  113.33  120.23  123.13  126.61  133.82  139.16  145.26  149.18
  154.33  176.62  211.67   245.2  275.63  319.81  334.17  340.13  347.63  356.94
  361.57  372.41  377.17  382.23  391.96  404.87  406.33  407.44  414.93  418.58
  428.39  439.43   444.4  451.72  458.18  468.85  472.07  472.24     487
  143.65  143.61  143.57  143.45  143.08  143.02  143.01  142.97  142.71  142.26
  142.01  141.95  141.93   141.9  141.87  141.61  141.24  140.42  139.58  139.46
   139.4  139.21  139.08  138.95  138.83  138.84  138.42  138.21  138.32  138.19
  138.17  138.02  137.59  137.97  137.94  138.73  138.78  139.01  138.77  139.66
   140.4  140.62  140.97  140.97  141.44   141.5  141.52  141.52  141.49  141.45
  141.71   143.6  143.65  144.12  145.09  145.83  145.84  145.85  144.56
                                                                                
                                                                                
                                                                                
                                                                                
                                                                                
                                                                        
BR Coef=-1 , 0 , 0 ,, 0 ,,,0.8,-1,,0,
WSPro=,,,, 1 ,,,, 0 ,,,, 0 ,,,,-1 ,-1 ,-1 , 0 , 0 , 0 , 0 , 0
Culvert=1,4,,17,0.024,0.9,1,2,3,130.5978,241,131.9764,247.7,Culvert #1  , 0 ,43
Culvert Bottom n=0.024
BC Design=,, 0 ,, 0 ,,,,,,
BC Use User HTab Curves=0
BC User HTab FreeFlow(D)= 0

Type RM Length L Ch R = 1 ,1664    ,161.87,164.81,164.27
BEGIN DESCRIPTION:
surveyed xs
END DESCRIPTION:
XS GIS Cut Line= 6
 2309181.6517035  742238.2515486    2309181.5693     742095.9638
    2309180.5724     742010.0978     2309183.701     741984.5853
    2309172.8187     741929.7408 2309184.3417047  741763.4663372
#Sta/Elev= 30
       0  140.83   33.19  139.91   50.13  140.13   59.45  139.47   78.08  139.28
  110.67  137.89  129.25  137.43  142.29   137.3 142.433  137.72 228.392  136.34
  235.79  134.51 244.295  132.92 244.903  132.45 248.371  132.24  251.73  134.49
 254.186  136.08 310.157  137.14  325.86  137.12  335.36  136.82  349.13     138
  358.71  140.43  363.25   141.2  397.95  141.12  406.91  141.43  411.71  142.54
  422.55  144.25  426.86   145.2  431.82  145.06   467.3  145.56  476.51  145.93
#Mann= 3 ,-1 , 0
       0    .045       0  235.79     .05       0  251.73    .045       0
#XS Ineff= 3 ,-1
       0  142.43     139  142.43     216  136.54     271  346.71  136.54
Permanent Ineff=
       T       F       F
Bank Sta=235.79,251.73
XS Rating Curve= 0 ,0
Exp/Cntr=0.5,0.3

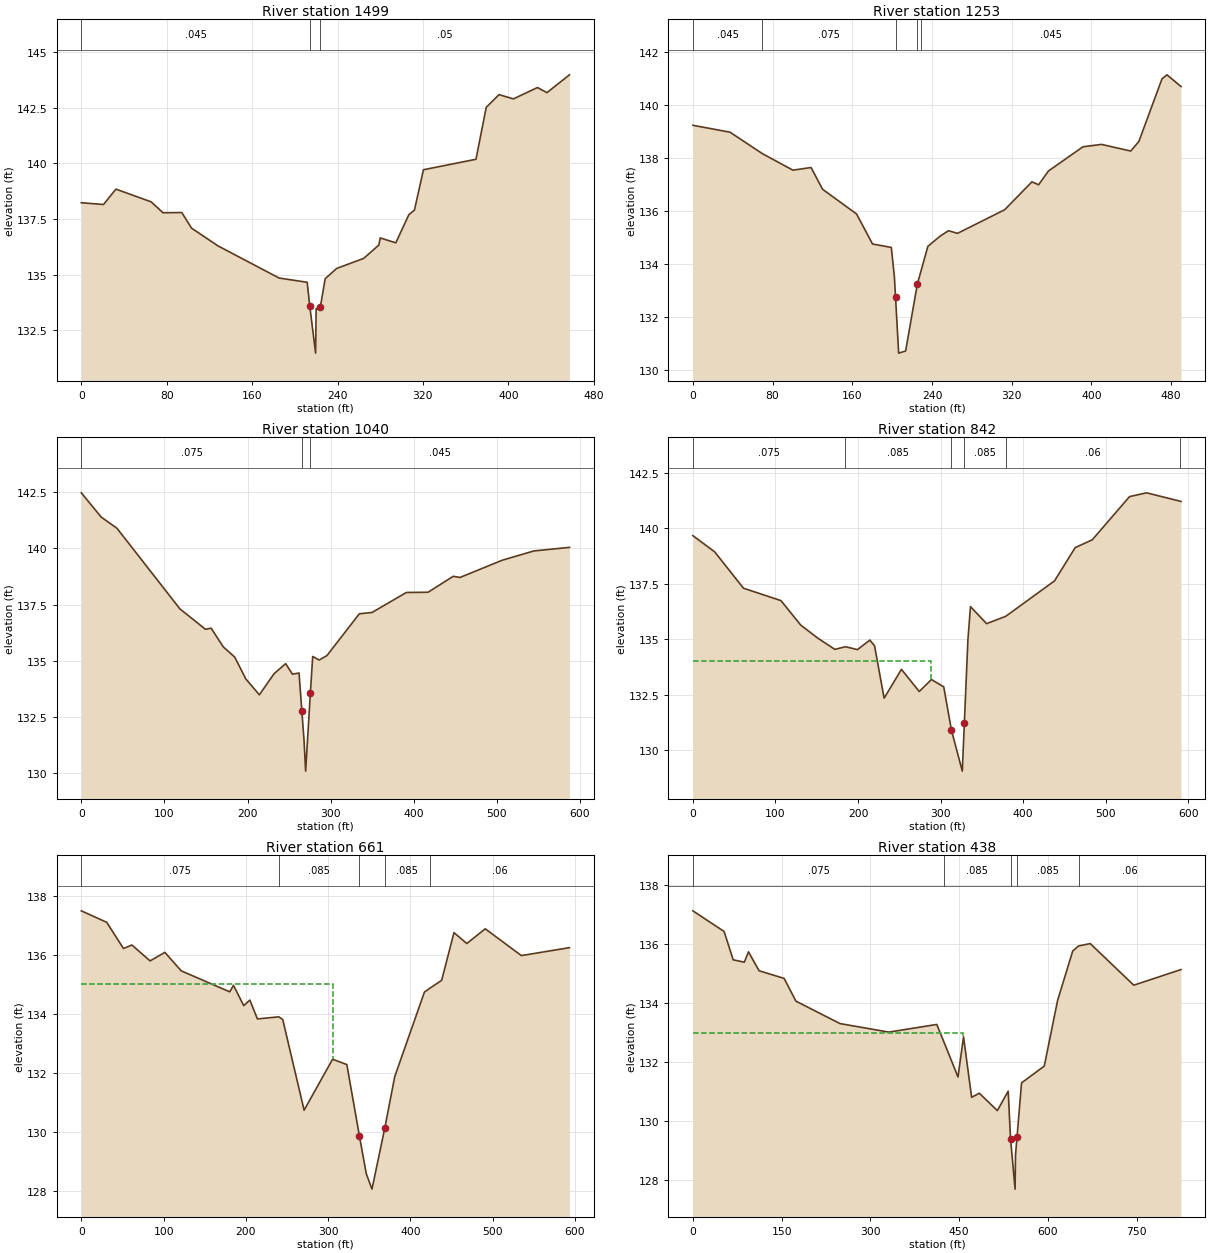
Type RM Length L Ch R = 1 ,1499    ,186.54,245.72,300.15
XS GIS Cut Line= 2
 2309343.0517753  742242.2865504 2309345.7417765  741784.9863468
#Sta/Elev= 30
       0  138.23   20.79  138.15   32.42  138.84   65.41  138.27   76.53  137.78
   94.11  137.79  103.23  137.09  128.13  136.29  185.27  134.85   211.6  134.66
  213.97  133.61  219.49  131.48  219.97  133.47  223.93  133.55  228.45  134.82
  239.22  135.28  264.44  135.73  278.74  136.33     280  136.65  294.61  136.43
  306.81  137.69  312.09   137.9  320.51  139.71  369.71  140.18  379.33  142.51
  391.29  143.08  404.83  142.89  427.29   143.4  436.19  143.17  457.31  143.97
#Mann= 3 ,-1 , 0
       0    .045       0  213.97     .05       0  223.93     .05       0
Bank Sta=213.97,223.93
XS Rating Curve= 0 ,0
Exp/Cntr=0.3,0.1

Type RM Length L Ch R = 1 ,1253    ,119.76,213.57,218.51
XS GIS Cut Line= 3
 2309524.6268561  742261.1165588 2309652.2992725  741817.9078079
 2309660.7260051  741790.5209268
#Sta/Elev= 30
       0  139.23   37.28  138.97   69.86  138.16  100.45  137.54  118.62  137.64
  130.19  136.82  164.31  135.89   180.3  134.76  199.16  134.63  202.27  133.52
   203.4  132.76  206.54  130.65  213.53  130.73  225.33  133.26  229.32  133.79
  235.84  134.67  247.96  135.05  256.53  135.26   265.6  135.16  312.94  136.05
  340.28   137.1  346.99  136.99  356.88  137.51  391.49  138.42  410.08  138.51
  439.41  138.26   447.6  138.62  470.83  140.98  475.81  141.13  489.89  140.69
#Mann= 5 ,-1 , 0
       0    .045       0   69.86    .075       0   203.4    .045       0
  225.33     .08       0  229.32    .045       0
Bank Sta=203.4,225.33
XS Rating Curve= 0 ,0
Exp/Cntr=0.3,0.1

Type RM Length L Ch R = 1 ,1040    ,119.1,197.46,210.52
XS GIS Cut Line= 3
 2309630.8053312  742305.4956467 2309774.3672586  742132.0249844
 2309896.9930716  741791.0654069
#Sta/Elev= 30
       0  142.48   23.92   141.4   42.92   140.9  118.65  137.31  149.42   136.4
  156.26  136.45  170.76  135.62  184.64  135.16  197.93  134.19  214.29  133.48
  231.94  134.42  245.93  134.87  254.06   134.4  262.03  134.45  265.44  132.75
  268.05  131.45  269.97  130.08  275.67  133.57  278.48  135.19  286.22  135.03
  295.66  135.23  334.57  137.09  349.91  137.15   391.2  138.04  417.33  138.05
   447.6  138.76  455.82  138.71  506.79  139.48  544.65  139.89  587.51  140.05
#Mann= 3 ,-1 , 0
       0    .075       0  265.44     .05       0  275.67    .045       0
#XS Ineff= 2 , 0
       0  245.93  134.87               0
Permanent Ineff=
       T       F
Bank Sta=265.44,275.67
XS Rating Curve= 0 ,0
Exp/Cntr=0.3,0.1

Type RM Length L Ch R = 1 ,842     ,65.58,181.02,286.83
XS GIS Cut Line= 3
 2309725.0319454  742364.6816049 2309914.4442951  742259.8868601
 2310081.0092955  741924.2953075
#Sta/Elev= 30
       0  139.67   26.41  138.94   61.24   137.3  106.67  136.74  130.78  135.63
  151.59  135.04  171.96  134.54  184.73  134.66  199.42  134.53  214.33  134.96
  220.03   134.7  231.62  132.34   252.6  133.64  274.13  132.64   288.9  133.18
  303.82  132.85  313.06  130.91  326.29  129.05   328.8  131.24  333.06  134.96
  336.19  136.47  355.66   135.7  378.85  136.03  437.99  137.63  462.99  139.13
  483.63  139.48  528.82  141.43  549.49   141.6  590.35  141.22  591.12  141.21
#Mann= 6 ,-1 , 0
       0    .075       0  184.73    .085       0  313.06     .05       0
   328.8    .085       0  378.85     .06       0  590.35     .03       0
#XS Ineff= 2 , 0
       0   288.9     134               0
Permanent Ineff=
       T       F
Bank Sta=313.06,328.8
XS Rating Curve= 0 ,0
Exp/Cntr=0.3,0.1

Type RM Length L Ch R = 1 ,661     ,262.32,222.69,192.4
XS GIS Cut Line= 3
 2309780.1769699  742388.8916156 2309961.1186178  742371.1119448
 2310302.0372022  742140.0665049
#Sta/Elev= 30
       0   137.5   30.86  137.11   51.27  136.22   61.44  136.34   83.59   135.8
  101.55  136.09   121.5  135.46  180.42  134.75  184.94  134.97  197.43  134.28
  204.86  134.47  214.04  133.83  240.01   133.9  244.82  133.81   270.8  130.73
  305.39  132.46  322.74  132.28  338.12  129.84  346.39  128.57  353.27  128.05
  368.77  130.11  380.94  131.87  417.03  134.74  423.57  134.87  437.99  135.14
  452.97  136.76  468.55  136.39  490.94  136.89  534.92  135.98  593.35  136.25
#Mann= 5 ,-1 , 0
       0    .075       0  240.01    .085       0  338.12     .05       0
  368.77    .085       0  423.57     .06       0
#XS Ineff= 2 , 0
       0  305.39     135               0
Permanent Ineff=
       T       F
Bank Sta=338.12,368.77
XS Rating Curve= 0 ,0
Exp/Cntr=0.3,0.1

Type RM Length L Ch R = 1 ,438     ,160.31,287.34,199.31
XS GIS Cut Line= 4
 2309706.2831975   742512.740952  2309924.548998  742582.2347235
 2310311.4253033   742413.432562 2310401.5672465  742265.1515606
#Sta/Elev= 30
       0  137.13    52.8  136.43   68.17  135.47   86.96  135.39   93.98  135.74
  111.85   135.1  154.24  134.84   174.1  134.07  248.49  133.31  331.06  133.02
  412.09  133.28  424.47  132.67  447.95   131.5  457.27  132.86     471  130.81
  483.93  130.95  514.43  130.36  532.74  131.02  536.73   129.4   544.4   127.7
  545.08  128.85  547.72  129.48  555.31   131.3  593.72  131.87  616.16  134.09
  641.78  135.77  651.75  135.94  671.36  136.02  744.88  134.61  824.69  135.14
#Mann= 5 ,-1 , 0
       0    .075       0  424.47    .085       0  536.73     .05       0
  547.72    .085       0  651.75     .06       0
#XS Ineff= 2 , 0
       0  457.07     133               0
Permanent Ineff=
       T       F
Bank Sta=536.73,547.72
XS Rating Curve= 0 ,0
Exp/Cntr=0.3,0.1

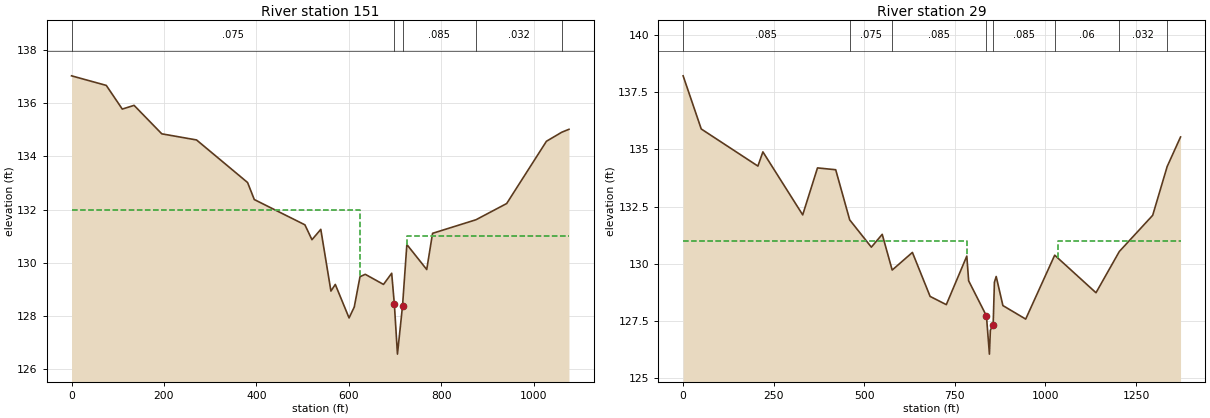
Type RM Length L Ch R = 1 ,151     ,138.24,121.6,112.29
XS GIS Cut Line= 4
 2309652.9117922  742595.6999141  2310236.139549  742789.6108904
 2310382.8791943  742639.2141822 2310487.6472849  742410.4116252
#Sta/Elev= 30
       0  137.03   75.19  136.67  109.84  135.78  135.35  135.92  195.29  134.85
   270.5  134.62  380.96  133.02  395.49  132.38  505.02  131.43  520.29  130.87
  539.39  131.26  561.32  128.94  570.77  129.19  600.57  127.93  611.78  128.34
  624.25  129.48  635.62  129.57  675.07  129.19   692.8  129.61   698.6  128.44
  705.28  126.57  716.29  128.39  725.62  130.69  768.64  129.75  781.22  131.11
  875.11  131.62  941.63  132.23 1027.67  134.57 1060.78  134.91 1076.39  135.02
#Mann= 5 ,-1 , 0
       0    .075       0   698.6     .05       0  716.29    .085       0
  875.11    .032       0 1060.78     .06       0
#XS Ineff= 2 , 0
       0  624.24     132  725.62       0     131
Permanent Ineff=
       T       F
Bank Sta=698.6,716.29
XS Rating Curve= 0 ,0
Exp/Cntr=0.3,0.1

Type RM Length L Ch R = 1 ,29      ,203.98,29.28,163.4
XS GIS Cut Line= 4
 2309529.4744625   742787.776762 2310293.6326431   742855.765747
 2310438.9208179  742807.8206493 2310568.3473208  742374.0966091
#Sta/Elev= 30
       0  138.21   49.99  135.89  206.36  134.27  220.15  134.89  330.02  132.14
  370.81  134.19  421.08  134.11  459.75  131.92  519.47  130.73  549.45  131.29
  576.99  129.73  632.76   130.5  681.62  128.58  726.34  128.22  782.91  130.34
  788.02  129.26   837.1  127.73  845.33  126.06  847.91   127.1  855.67  127.35
  859.13   129.2  864.01  129.45  882.52  128.18  945.43  127.59 1025.48  130.38
 1139.44  128.74  1203.8  130.54 1295.91  132.12 1335.87  134.25 1372.79  135.54
#Mann= 8 ,-1 , 0
       0    .085       0  459.75    .075       0  576.99    .085       0
   837.1     .05       0  855.67    .085       0 1025.48     .06       0
  1203.8    .032       0 1335.87     .06       0
#XS Ineff= 2 , 0
       0  782.91     131 1035.42       0     131
Permanent Ineff=
       F       F
Bank Sta=837.1,855.67
XS Rating Curve= 0 ,0
Exp/Cntr=0.3,0.1
Stream Node=Trib2 to Toisnot,1               , 0 , 0 ,Upstream end
Stream Node=Trib2 to Toisnot,1               , 0 , 1 ,Downstream end

Chan Stop Cuts=-1
Use User Specified Reach Order=0
User Specified Reach Order=Trib2 to Toisnot,1