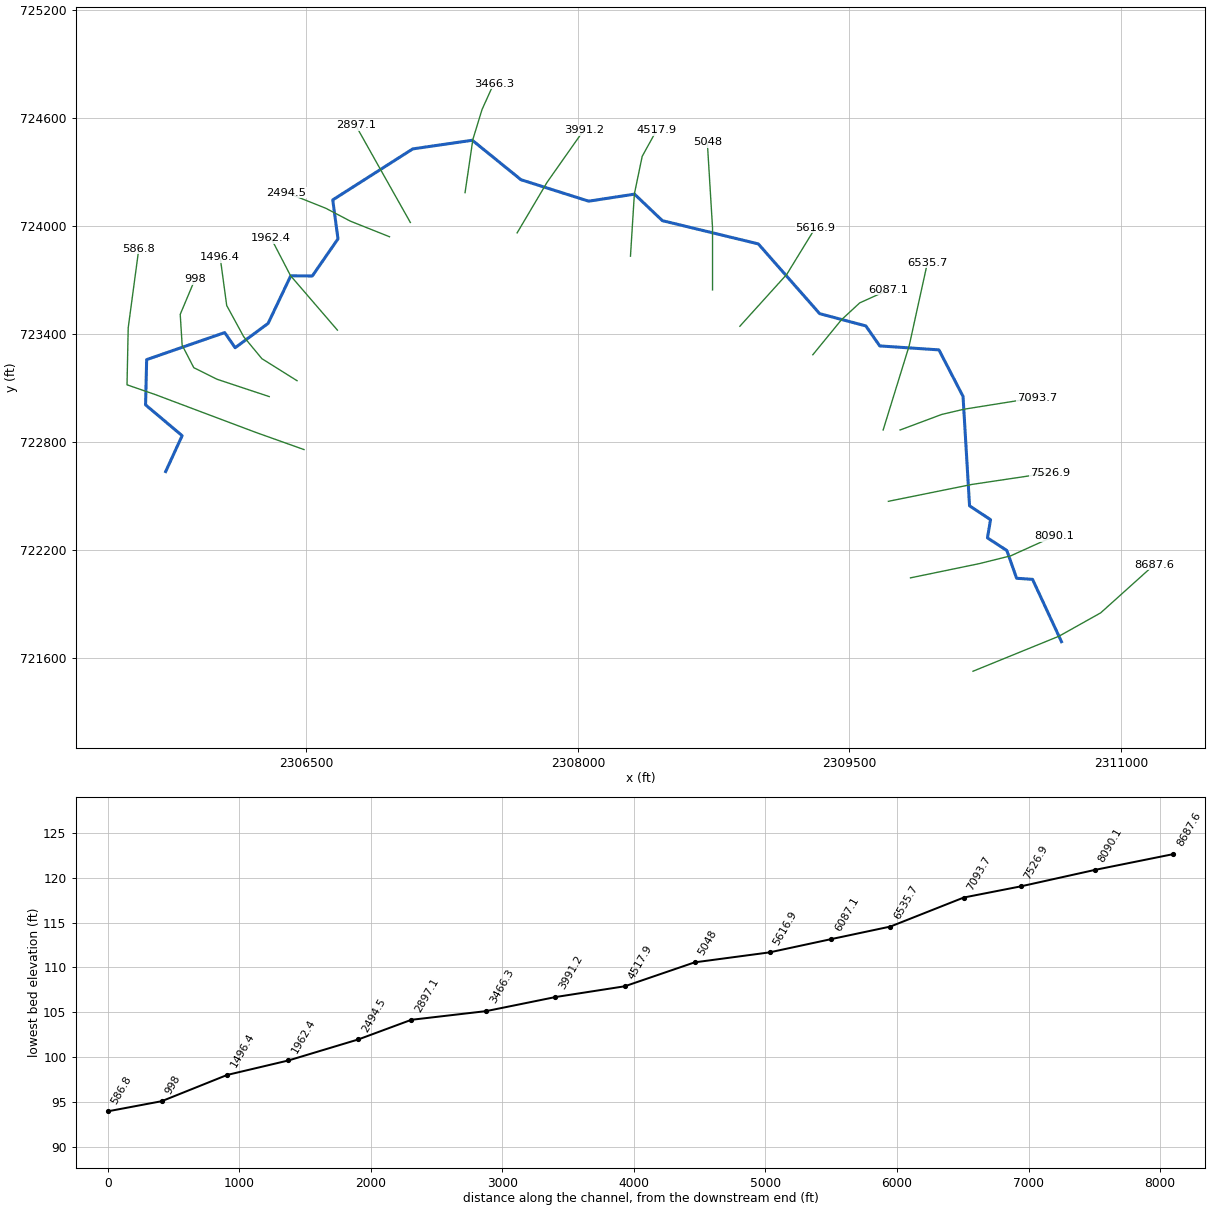
--- lds_bloomery_swp_trib2.prj (project) ---

Proj Title=lds_bloomery_swp_trib2
Current Plan=p02
Default Exp/Contr=0.3,0.1
English Units
Geom File=g01
Flow File=f01
Flow File=f02
Plan File=p02
Plan File=p01
Y Axis Title=Elevation
X Axis Title(PF)=Main Channel Distance
X Axis Title(XS)=Station
BEGIN DESCRIPTION:
END DESCRIPTION:
DSS File=dss
DSS Export Rating Curves= 0
DSS Export Rating Curve Sorted= 0
DSS Export Volume Flow Curves= 0
DXF OffsetX= 0
DXF OffsetY= 0
DXF ScaleX= 1
DXF ScaleY= 10

--- lds_bloomery_swp_trib2.p02 (plan) ---

Plan Title=lds_bloomery_swp_trib2
Program Version=4.00
Short Identifier=Plan 01
Geom File=g01
Flow File=f01
Subcritical Flow
K Sum by GR= 0
Std Step Tol= 0.01
Critical Tol= 0.01
Num of Std Step Trials= 20
Max Error Tol= 0.3
Flow Tol Ratio= 0.001
Split Flow NTrial= 30
Split Flow Tol= 0.02
Split Flow Ratio= 0.02
Log Output Level= 0
Friction Slope Method= 1
Unsteady Friction Slope Method= 2
Unsteady Bridges Friction Slope Method= 1
Parabolic Critical Depth
Global Vel Dist= 0 , 0 , 0
Global Log Level= 0
CheckData=True
Encroach Param=-1 ,10,10, 2
Encroach River=Bloomery Trib 2
Encroach Reach=Reach - 1
Encroach Node=8687.6
       4      .7
Encroach Node=8090.1
       4      .7
Encroach Node=7526.9
       1    4989    5018
Encroach Node=7093.7
       4      .7
Encroach Node=6535.7
       4      .7
Encroach Node=6087.1
       4      .7
Encroach Node=5616.9
       1    4965    5018
Encroach Node=5048
       4      .7
Encroach Node=4517.9
       4      .7
Encroach Node=3991.2
       4      .7
Encroach Node=3466.3
       4      .7
Encroach Node=2897.1
       4      .7
Encroach Node=2494.5
       1    4985    5020
Encroach Node=1962.4
       4      .7
Encroach Node=1496.4
       4      .7
Encroach Node=998
       1  4937.2  5042.1
Encroach Node=586.8
       4      .7
Computation Interval=1HOUR
Output Interval=1HOUR
Run HTab= 0
Run UNet= 0
Run PostProcess= 0
Run WQNet= 0
UNET Theta= 1
UNET Theta Warmup= 1
UNET ZTol= 0.02
UNET ZSATol= 0.05
UNET MxIter= 20
UNET MaxInSteps= 0
UNET DtIC= 0
UNET DtMin= 0
UNET MaxCRTS= 20
UNET WFStab= 2
UNET SFStab= 1
UNET WFX= 1
UNET SFX= 1
UNET DSS MLevel= 4
UNET DZMax Abort= 100
UNET Convert EG Bridges= 0
UNET Use Existing IB Tables=-1
UNET Froude Reduction=False
UNET Froude Limit= 1
UNET Froude Power= 10
UNET Time Slicing=0,0, 5
Instantaneous Interval=1HOUR
DSS File=dss
Write IC File= 0
Echo Input=False
Echo Output=False
Write Detailed= 0
Detailed Automatic Start=False, 10
WQ ULTIMATE=-1
WQ Max Comp Step=1HOUR
WQ Output Interval=15MIN
WQ Output Selected Increments= 0
WQ Output face flow=0
WQ Output face velocity=0
WQ Output face area=0
WQ Output face dispersion=0
WQ Output cell volume=0
WQ Output cell surface area=0
WQ Output cell continuity=0
WQ Output face conc=0
WQ Output face dconc_dx=0
WQ Output face courant=0
WQ Output face peclet=0
WQ Output face adv mass=0
WQ Output face disp mass=0
WQ Output cell mass=0
WQ Output cell source sink temp=0
WQ Output cell source sink nsm=0
WQ Output MaxMinRange=-1
WQ Daily Max Min Mean=-1
WQ Daily Range=0
WQ Daily Time=0
WQ Create Restart=0
WQ Fixed Restart=0
WQ System Summary=False
Sorting and Armoring Iterations= 10
XS Update Threshold= 0.02
Hydraulics Update Threshold= 0.02
Energy Slope Method= 1
Volume Change Method= 0
XS Weighting Method= 0
Number of US Weighted Cross Sections= 1
Number of DS Weighted Cross Sections= 1
Upstream XS Weight=0.25
Main XS Weight=0.5
Downstream XS Weight=0.25
Number of DS XS's Weighted with US Boundary= 1
Upstream Boundary Weight= 1
Weight of XSs Associated with US Boundary= 0
Number of US XS's Weighted with DS Boundary= 1
Downstream Boundary Weight= 0.5
Weight of XSs Associated with DS Boundary= 0.5
Sediment Output Level= 4
Mass or Volume Output= 0
Output Increment Type= 1
Profile and TS Output Increment= 10
XS Output Flag= 0
XS Output Increment= 10
Disregard all LS=0
Disregard all Conn=0
Disregard all Breaches=0
Disregard all Pumps=0

--- lds_bloomery_swp_trib2.p01 (plan) ---

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Plan Title=lds_bloomery_swp_trib2_multiprofile
Short Identifier=lds_bloomery
Geom File=g01
Flow File=f02
Encroach Param=-1 ,0,0, 0

--- lds_bloomery_swp_trib2.f01 (steady flow) ---

Flow Title=lds_bloomery_swp_trib2
Program Version=4.00
Number of Profiles= 2
Profile Names=100-Year,AFW
River Rch & RM=Bloomery Trib 2,Reach - 1       ,8687.6
     730     730
River Rch & RM=Bloomery Trib 2,Reach - 1       ,5616.9
     851     851
Boundary for River Rch & Prof#=Bloomery Trib 2,Reach - 1       , 1
Up Type= 0
Dn Type= 3
Dn Slope=0.0059
Boundary for River Rch & Prof#=Bloomery Trib 2,Reach - 1       , 2
Up Type= 0
Dn Type= 3
Dn Slope=0.0059
DSS Import GetInterval= 0
DSS Import GetPeak= 0
DSS Import FillOption= 0

--- lds_bloomery_swp_trib2.f02 (steady flow) ---

Flow Title=lds_bloomery_swp_trib2_multiprofile
Program Version=4.00
Number of Profiles= 7
Profile Names=10yr,25yr,50yr,500yr,100yr_10%,100yr_20%,100yr_35%
River Rch & RM=Bloomery Trib 2,Reach - 1       ,8687.6
     450     660     750    1070     560     710     870
River Rch & RM=Bloomery Trib 2,Reach - 1       ,5616.9
     530     780     900    1350     800    1020    1250
Boundary for River Rch & Prof#=Bloomery Trib 2,Reach - 1       , 1
Up Type= 0
Dn Type= 3
Dn Slope=0.0059
Boundary for River Rch & Prof#=Bloomery Trib 2,Reach - 1       , 2
Up Type= 0
Dn Type= 3
Dn Slope=0.0059
DSS Import GetInterval= 0
DSS Import GetPeak= 0
DSS Import FillOption= 0

--- lds_bloomery_swp_trib2.g01 (geometry) ---

Geom Title=lds_bloomery_swp_trib2
Program Version=4.00

River Reach=Bloomery Trib 2 ,Reach - 1
Reach XY= 30
2310672.00000001721693.0000000152310512.00000001722039.000000015
2310424.00000003722045.000000015        2310370.722199.000000015
2310263.00000003         722269.2310280.00000003         722370.
2310163.99999999722447.000000015        2310128.         723054.
2309995.00000001         723312.2309668.00000003723334.000000015
2309591.00000001723445.0000000152309336.00000001         723513.
2308997.00000001         723900.2308467.00000001         724029.
2308312.99999999         724176.2308060.00000003724137.000000015
2307686.00000004         724256.2307417.00000003724475.000000015
2307087.99999999724427.0000000152306646.00000001         724144.
2306675.00000003723928.0000000152306533.00000001         723722.
2306414.00000004         723723.2306289.00000003         723459.
2306106.99999999723324.0000000152306049.00000001 723408.00000003
2305618.00000001         723258.2305612.00000003         723007.
        2305814.722836.0000000152305723.00000003         722637.

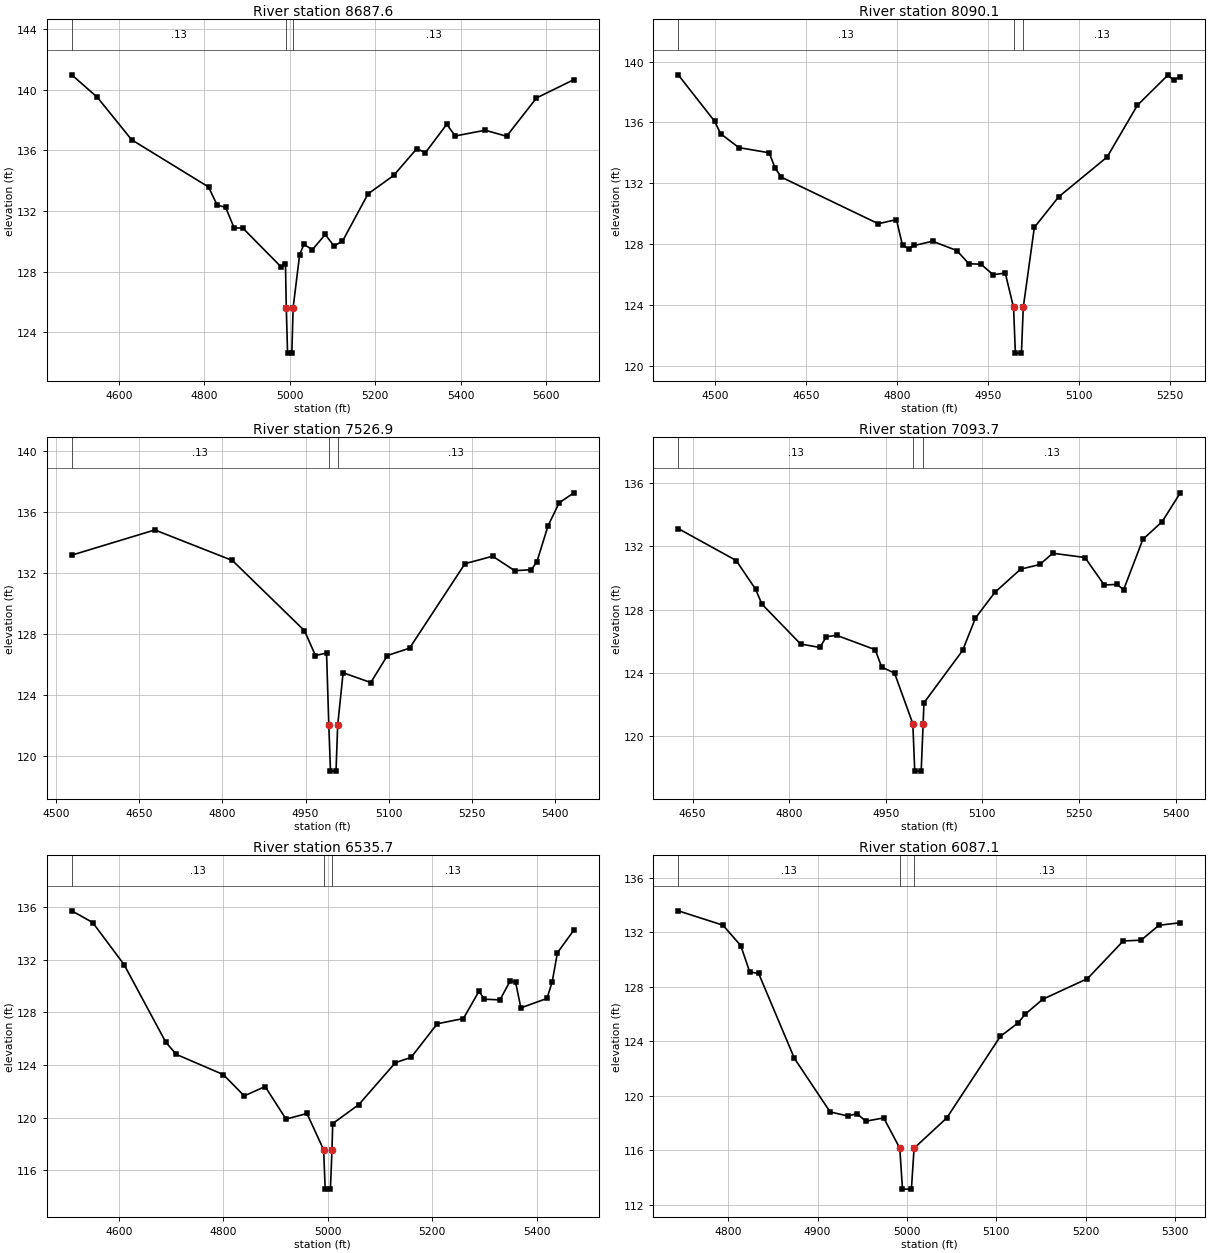
Type RM Length L Ch R = 1 ,8687.6  ,601.74,597.23,592.89
XS GIS Cut Line= 4
 2310183.1796875721529.2356770932310658.07942712721723.513020828
2310888.33398438    721853.031252311183.34765625722119.262369812
#Sta/Elev= 30
  4490.1     141  4550.1  139.51  4630.1  136.71  4810.1  133.59  4830.1   132.4
  4850.1  132.24  4870.1  130.88  4890.1  130.88  4980.1   128.3  4990.1   128.5
    4992  125.61    4995  122.61    5005  122.61    5008  125.61  5023.2  129.11
  5033.2  129.79  5053.2  129.45  5083.2  130.45  5103.2   129.7  5123.2  129.99
  5183.2  133.13  5243.2  134.35  5297.4  136.12  5317.4  135.85  5367.4  137.73
  5387.4  136.96  5457.4  137.34  5507.4  136.94  5577.4  139.47  5664.8  140.68
#Mann= 3 ,-1 , 0
  4490.1     .13       0    4992    .046       0    5008     .13       0
Bank Sta=4992,5008
XS Rating Curve= 0 ,0
Exp/Cntr=0.3,0.1

Type RM Length L Ch R = 1 ,8090.1  ,566.56,563.26,558.38
XS GIS Cut Line= 4
2309837.79817706722047.3079427032310219.15690109722126.458333328
2310391.84765628722169.6308593752310629.29752609722277.562500015
#Sta/Elev= 29
  4438.8  139.13  4498.8  136.08  4508.8  135.26  4538.8  134.35  4588.8  134.01
  4598.8  132.99  4608.8  132.41  4768.8  129.35  4798.8  129.62  4808.8  127.92
  4818.8  127.72  4828.3  127.92  4858.3   128.2  4898.3  127.59  4918.3  126.72
  4938.3  126.69  4958.3     126  4978.3  126.11    4992  123.85    4995  120.85
    5005  120.85    5008  123.85  5026.3  129.11  5066.3  131.11  5146.3  133.73
  5196.3  137.13  5246.3   139.1  5256.3  138.79  5267.1  139.01
#Mann= 3 ,-1 , 0
  4438.8     .13       0    4992    .046       0    5008     .13       0
Bank Sta=4992,5008
XS Rating Curve= 0 ,0
Exp/Cntr=0.3,0.1

Type RM Length L Ch R = 1 ,7526.9  ,432.45,433.22,433.64
XS GIS Cut Line= 3
2309715.47526044722471.8398437652310175.98437501 722565.38085939
 2310607.7109375722630.139973968
#Sta/Elev= 22
  4527.9  133.16  4677.9  134.81  4817.9  132.81  4947.9  128.22  4967.9  126.59
  4987.9  126.75    4992  122.02    4995  119.02    5005  119.02    5008  122.02
  5017.8  125.46  5067.8  124.82  5097.8  126.59  5137.8  127.07  5237.8   132.6
  5287.8  133.09  5327.8  132.14  5357.8  132.21  5367.8  132.74  5387.8  135.08
  5407.8  136.58  5434.4  137.24
#Mann= 3 ,-1 , 0
  4527.9     .13       0    4992    .046       0    5008     .13       0
Bank Sta=4992,5008
XS Rating Curve= 0 ,0
Exp/Cntr=0.3,0.1

Type RM Length L Ch R = 1 ,7093.7  ,542.27,557.9,575.79
XS GIS Cut Line= 4
  2309780.234375 722867.589843752310010.48893231722953.934895843
2310132.81119794722982.7167968752310535.75651044723047.475911468
#Sta/Elev= 29
  4627.7  133.12  4717.7   131.1  4747.7  129.29  4757.7  128.34  4817.7  125.82
  4847.7   125.6  4857.7  126.28  4873.6  126.37  4933.6  125.46  4943.6  124.36
  4963.6  123.98    4992  120.78    4995  117.78    5005  117.78    5008  120.78
  5009.3   122.1  5069.3  125.41  5089.3  127.46  5119.3  129.08  5159.3  130.55
  5189.3  130.85  5209.3  131.56  5259.3  131.29  5289.3  129.55  5309.3  129.59
  5319.3  129.25  5349.3  132.44  5379.3  133.56  5407.4  135.38
#Mann= 3 ,-1 , 0
  4627.7     .13       0    4992    .046       0    5008     .13       0
Bank Sta=4992,5008
XS Rating Curve= 0 ,0
Exp/Cntr=0.3,0.1

Type RM Length L Ch R = 1 ,6535.7  ,454.19,448.18,439.63
XS GIS Cut Line= 3
 2309686.6933594 722867.589843752309830.60221358723335.294270843
2309931.33854172723795.802734375
#Sta/Elev= 30
  4510.1  135.74  4550.1  134.85  4610.1  131.65  4690.1  125.73  4710.1  124.81
  4800.1  123.27  4840.1  121.65  4880.1  122.36  4920.1  119.88  4960.1  120.31
    4992  117.55    4995  114.55    5005  114.55    5008  117.55  5009.4  119.54
  5059.4  120.99  5129.4  124.18  5159.4  124.58  5209.4  127.14  5259.4  127.54
  5289.4  129.62  5299.4  129.01  5329.4  128.96  5349.4  130.43  5359.4   130.3
  5369.4  128.35  5419.4  129.07  5429.4  130.34  5439.4  132.55  5470.8  134.27
#Mann= 3 ,-1 , 0
  4510.1     .13       0    4992    .046       0    5008     .13       0
Bank Sta=4992,5008
XS Rating Curve= 0 ,0
Exp/Cntr=0.3,0.1

Type RM Length L Ch R = 1 ,6087.1  ,463.2,470.15,478.1
XS GIS Cut Line= 4
2309298.13932295723284.9257812652309456.43880209   723479.203125
2309557.17513023 723572.744140642309715.47526044723644.698567703
#Sta/Elev= 25
    4744  133.56    4794  132.51    4814  131.01    4824  129.08    4834  128.97
    4874  122.75    4914  118.82    4934  118.52    4944  118.69    4954  118.14
    4974  118.38    4992  116.16    4995  113.16    5005  113.16    5008  116.16
  5044.6  118.38  5104.6  124.36  5124.6  125.35  5132.1  125.97  5152.1  127.08
  5202.1  128.59  5242.1  131.35  5262.1  131.41  5282.1   132.5    5306  132.69
#Mann= 3 ,-1 , 0
    4744     .13       0    4992    .046       0    5008     .13       0
Bank Sta=4992,5008
XS Rating Curve= 0 ,0
Exp/Cntr=0.3,0.1

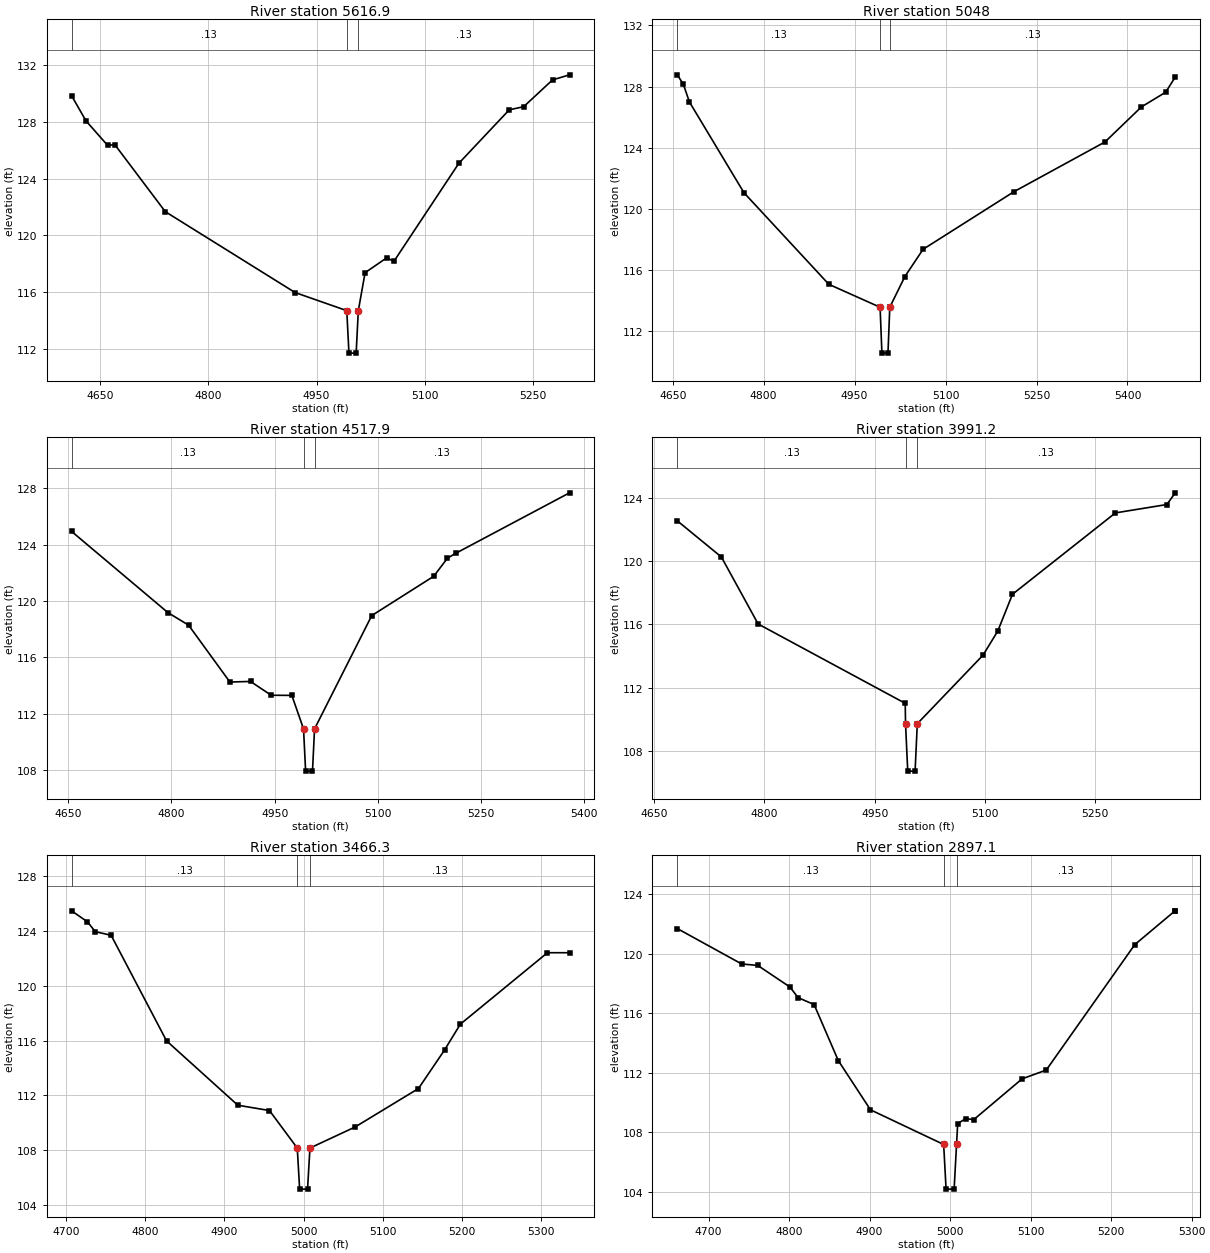
Type RM Length L Ch R = 1 ,5616.9  ,560.94,569.42,576.54
XS GIS Cut Line= 3
2308895.19401045723443.2259114682309154.22981773723731.043619797
2309312.52994794 723990.08007814
#Sta/Elev= 18
  4610.2  129.86  4630.2  128.08  4660.2  126.35  4670.2   126.4  4740.2  121.67
  4920.2  115.96    4992  114.68    4995  111.68    5005  111.68    5008  114.68
  5017.4  117.36  5047.4  118.41  5057.4  118.16  5147.4  125.08  5217.4  128.86
  5237.4  129.08  5277.4  130.97    5301  131.33
#Mann= 3 ,-1 , 0
  4610.2     .13       0    4992    .046       0    5008     .13       0
Bank Sta=4992,5008
XS Rating Curve= 0 ,0
Exp/Cntr=0.3,0.1

Type RM Length L Ch R = 1 ,5048    ,533.38,531,525.47
XS GIS Cut Line= 3
2308744.08919273723644.6985677032308744.08919273 723990.08007814
 2308715.3072917724464.979817718
#Sta/Elev= 16
  4657.5  128.77  4667.5  128.16  4677.5     127  4767.5  121.06  4907.5  115.07
    4992  113.57    4995  110.57    5005  110.57    5008  113.57  5032.9  115.58
  5062.9  117.36  5212.9  121.13  5362.9  124.38  5422.9  126.67  5462.9  127.63
  5478.7  128.62
#Mann= 3 ,-1 , 0
  4657.5     .13       0    4992    .046       0    5008     .13       0
Bank Sta=4992,5008
XS Rating Curve= 0 ,0
Exp/Cntr=0.3,0.1

Type RM Length L Ch R = 1 ,4517.9  ,535.26,527.66,521.68
XS GIS Cut Line= 4
2308290.77604166723831.779947937 2308312.3619792724177.162109375
2308355.53515628724385.8300781252308434.68489583724529.738932312
#Sta/Elev= 16
    4655  124.94    4795  119.17    4825  118.28    4885  114.24    4915  114.28
    4945   113.3    4975  113.29    4992  110.91    4995  107.91    5005  107.91
    5008  110.91  5091.1  118.96  5181.1  121.75  5201.1  123.04  5214.1  123.41
  5378.4  127.68
#Mann= 3 ,-1 , 0
    4655     .13       0    4992    .046       0    5008     .13       0
Bank Sta=4992,5008
XS Rating Curve= 0 ,0
Exp/Cntr=0.3,0.1

Type RM Length L Ch R = 1 ,3991.2  ,513.16,525.08,532.83
XS GIS Cut Line= 3
 2307664.7714844723961.2981770782307830.26692709724241.921223953
2308031.73958331724529.738932312
#Sta/Elev= 14
  4681.6  122.55  4741.6  120.26  4791.6  116.02  4991.6     111    4992  109.71
    4995  106.71    5005  106.71    5008  109.71  5097.4  114.05  5117.4  115.57
  5137.4   117.9  5277.4  123.05  5347.4  123.58  5358.7  124.32
#Mann= 3 ,-1 , 0
  4681.6     .13       0    4992    .046       0    5008     .13       0
Bank Sta=4992,5008
XS Rating Curve= 0 ,0
Exp/Cntr=0.3,0.1

Type RM Length L Ch R = 1 ,3466.3  ,559.75,569.88,581.32
XS GIS Cut Line= 4
2307376.95312503 724184.357421892307420.12630209724479.371093765
2307470.49414061724644.8665364682307535.25325523724788.775390625
#Sta/Elev= 17
  4706.9  125.48  4726.9  124.68  4736.9  123.96  4756.9  123.69  4826.9  115.98
  4916.9  111.28  4956.9  110.89    4992  108.15    4995  105.15    5005  105.15
    5008  108.15  5065.1  109.69  5145.1   112.5    5178  115.31    5198   117.2
    5308  122.42  5335.9  122.42
#Mann= 3 ,-1 , 0
  4706.9     .13       0    4992    .046       0    5008     .13       0
Bank Sta=4992,5008
XS Rating Curve= 0 ,0
Exp/Cntr=0.3,0.1

Type RM Length L Ch R = 1 ,2897.1  ,393.24,402.42,411.52
XS GIS Cut Line= 3
2307074.74414065724018.8619791722306909.24934895724313.875651062
 2306772.5358073724558.520833343
#Sta/Elev= 20
  4661.1  121.69  4741.1  119.31  4761.1  119.21  4801.1  117.76  4811.1  117.05
  4831.1  116.58  4861.1  112.82  4901.1  109.51    4992  107.18    4995  104.18
    5005  104.18    5008  107.18  5009.4  108.58  5019.4  108.92  5029.4  108.85
  5089.4  111.59  5119.4  112.18  5229.4  120.61  5279.4  122.88  5279.6  122.88
#Mann= 3 ,-1 , 0
  4661.1     .13       0    4992    .046       0    5008     .13       0
Bank Sta=4992,5008
XS Rating Curve= 0 ,0
Exp/Cntr=0.3,0.1

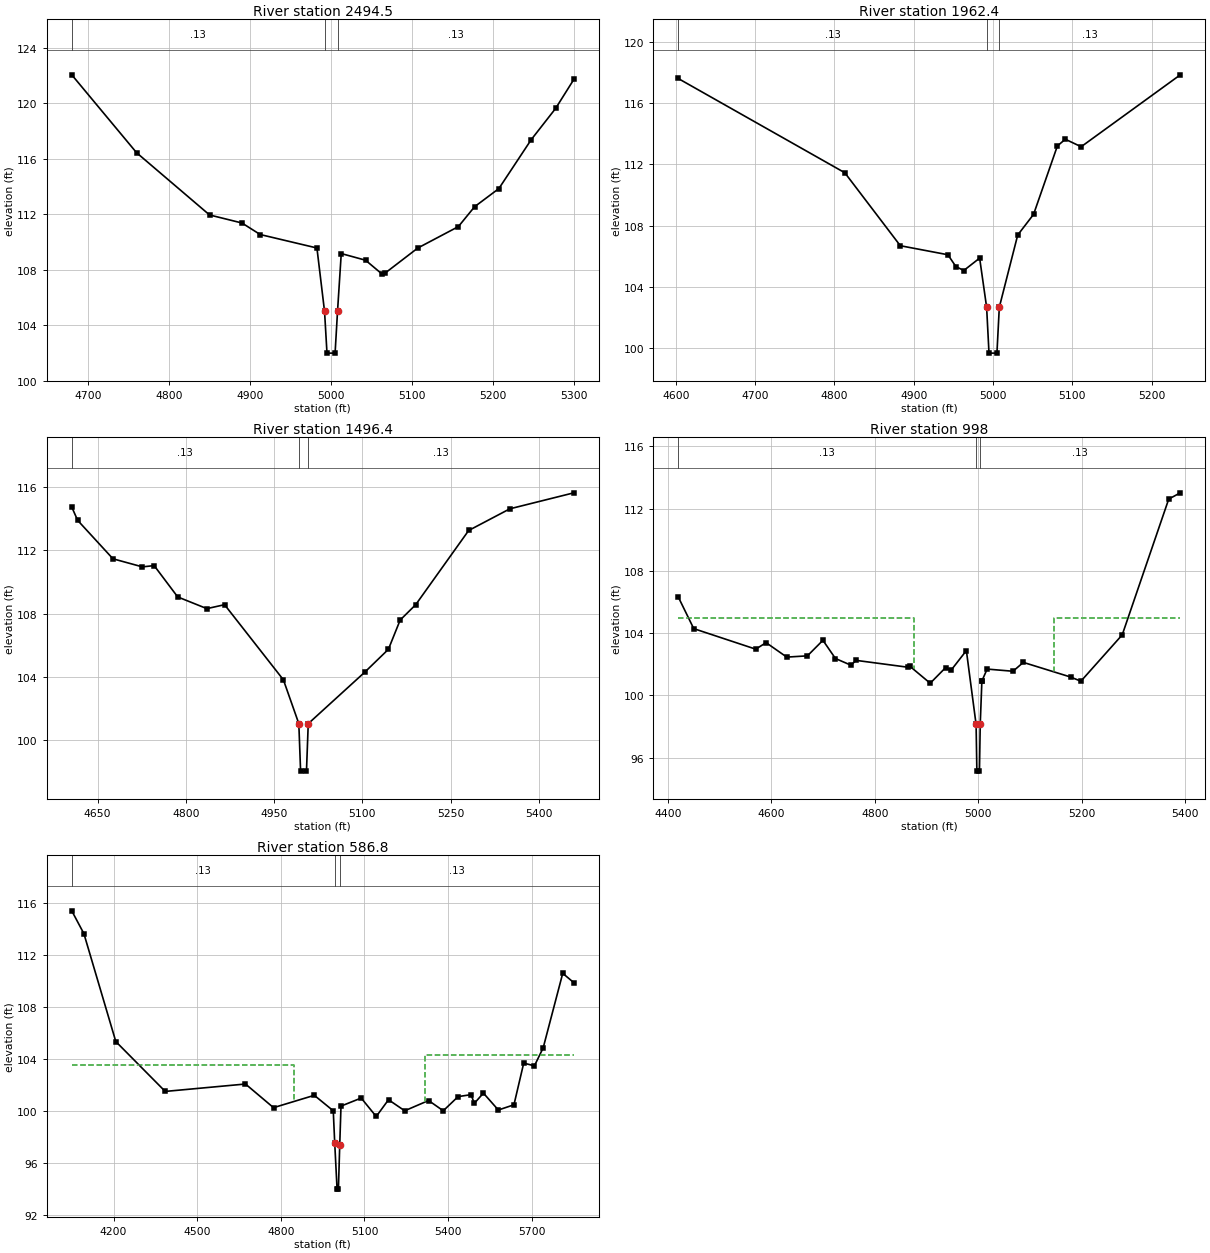
Type RM Length L Ch R = 1 ,2494.5  ,535.68,531.44,523.78
XS GIS Cut Line= 4
2306959.61718753723939.7122395932306743.75390626724026.057291687
2306607.04036459 724098.011718752306391.17643233 724184.35742189
#Sta/Elev= 21
  4680.1  122.04  4760.1  116.43  4850.1  111.95  4890.1  111.37  4912.6  110.54
  4982.6  109.57    4992     105    4995     102    5005     102    5008     105
  5012.6  109.17  5042.6  108.69  5062.6  107.71  5067.1  107.78  5107.1  109.57
  5157.1  111.11  5177.1  112.54  5207.1  113.85  5247.1  117.38  5277.1  119.62
  5299.6  121.71
#Mann= 3 ,-1 , 0
  4680.1     .13       0    4992    .046       0    5008     .13       0
Bank Sta=4992,5008
XS Rating Curve= 0 ,0
Exp/Cntr=0.3,0.1

Type RM Length L Ch R = 1 ,1962.4  ,465.9,465.61,466.95
XS GIS Cut Line= 3
 2306671.7994792723421.6393229372306412.76302086723723.848307297
2306304.83138023723932.516276047
#Sta/Elev= 17
  4603.2  117.61  4813.2  111.45  4883.2  106.68  4943.2  106.09  4953.2  105.32
  4963.2  105.06  4983.2  105.87    4992  102.66    4995   99.66    5005   99.66
    5008  102.66  5031.2  107.38  5051.2  108.73  5081.2   113.2  5091.2  113.64
  5111.2  113.15  5236.2  117.85
#Mann= 3 ,-1 , 0
  4603.2     .13       0    4992    .046       0    5008     .13       0
Bank Sta=4992,5008
XS Rating Curve= 0 ,0
Exp/Cntr=0.3,0.1

Type RM Length L Ch R = 1 ,1496.4  ,499.07,497.71,492.81
XS GIS Cut Line= 5
2306448.74023439723141.0169270782306254.46289065723263.339192703
2306153.72656251723385.6621093752306060.18554688723558.352864578
2306024.20833334723824.584635437
#Sta/Elev= 20
  4606.2  114.74  4616.2   113.9  4676.2  111.47  4726.2  110.96  4746.2  111.04
  4786.2  109.06  4835.8  108.32  4865.8  108.57  4965.8  103.82    4992  101.05
    4995   98.05    5005   98.05    5008  101.05  5104.2  104.31  5144.2  105.75
  5164.2   107.6  5190.6  108.57  5280.6  113.26  5350.6  114.63  5459.3  115.64
#Mann= 3 ,-1 , 0
  4606.2     .13       0    4992    .046       0    5008     .13       0
Bank Sta=4992,5008
XS Rating Curve= 0 ,0
Exp/Cntr=0.3,0.1

Type RM Length L Ch R = 1 ,998     ,398.54,410.96,426.81
XS GIS Cut Line= 6
2306295.11002605723052.9667968752306006.52018233723149.163411468
2305878.25846353723213.2942708432305814.12695314 723337.99414064
2305803.43880209723509.0104166722305885.38411459723704.966145843
#Sta/Elev= 30
  4419.6  106.33  4449.6  104.29  4569.6  102.97  4589.6  103.39  4629.6  102.46
  4669.6  102.54  4699.6  103.54  4723.8  102.37  4753.8  101.94  4763.8  102.25
  4863.8  101.81  4867.2  101.89  4907.2  100.78  4937.2  101.79  4947.2   101.6
  4977.2  102.88    4996   98.13  4997.5   95.13  5002.5   95.13    5004   98.13
  5007.2  100.92  5007.4  100.94  5017.4  101.69  5067.4  101.55  5087.4  102.12
  5178.8  101.18  5198.8  100.91  5278.8  103.89  5368.8  112.62  5391.2  113.02
#Mann= 3 ,-1 , 0
  4419.6     .13       0    4996    .045       0    5004     .13       0
#XS Ineff= 2 , 0
       0    4875     105    5146       0     105
Permanent Ineff=
       F       F
Bank Sta=4996,5004
XS Rating Curve= 0 ,0
Exp/Cntr=0.3,0.1

Type RM Length L Ch R = 1 ,586.8   ,591.95,586.79,581.65
XS GIS Cut Line= 6
2306487.21145642722758.9922408762306219.37665187 722854.80306527
2305666.28689291723063.8448639212305509.50554387723118.282832339
2305516.03810009723434.0230490712305574.83110598723873.881833777
#Sta/Elev= 30
    4050  115.42 4093.57  113.66 4207.93  105.36 4385.29  101.52 4673.24  102.09
 4773.83  100.27 4920.15  101.22 4988.14  100.03 4993.44   97.52 5001.81      94
  5006.6      94 5011.37    97.4 5015.89  100.39 5088.34  101.01 5142.29   99.59
 5186.32  100.88 5244.47  100.03 5330.08  100.82 5382.81  100.03  5435.9  101.12
 5482.47  101.27 5494.16   100.6 5526.81  101.39 5580.33  100.09 5636.36  100.49
 5671.42   103.7 5709.87  103.49 5741.34  104.88 5811.39  110.61 5851.27  109.89
#Mann= 3 ,-1 , 0
    4050     .13       0 4993.44    .045       0 5011.37     .13       0
#XS Ineff= 2 , 0
         4847.67  103.52    5319          104.36
Permanent Ineff=
       F       F
Bank Sta=4993.44,5011.37
XS Rating Curve= 0 ,0
Exp/Cntr=0.3,0.1
Stream Node=Bloomery Trib 2 ,Reach - 1       , 0 , 0 ,Upstream end
Stream Node=Bloomery Trib 2 ,Reach - 1       , 0 , 1 ,Downstream end

Chan Stop Cuts=-1

CM Alternative=Alternative #1
CM River Reach=Bloomery Trib 2 ,Reach - 1
 CM RS=586.8   ,109.89,591.95,586.79,581.65,5000,,,,,
Use User Specified Reach Order=0