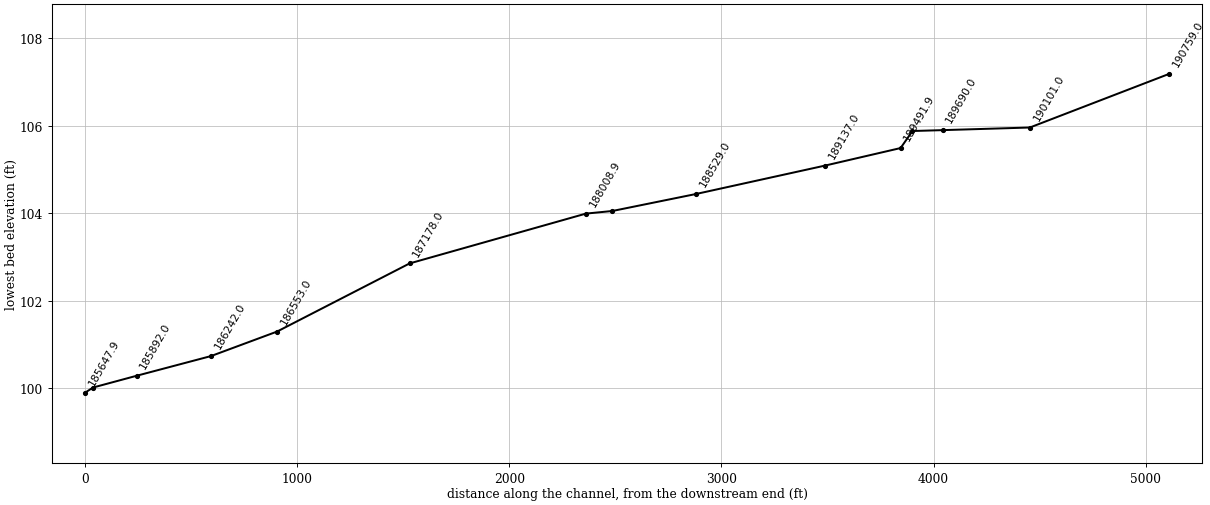
--- Town_Creek_FINAL.PRJ (project) ---

Proj Title=Town Creek
Current Plan=p02
Default Exp/Contr=.3,.1
English Units
Geom File=g01
Flow File=f02
Flow File=f01
Plan File=p02
Plan File=p01
Y Axis Title=Elevation
X Axis Title(PF)=Main Channel Distance
X Axis Title(XS)=Station
BEGIN DESCRIPTION:
NCFM-TarPam Basin
END DESCRIPTION:
DSS Export Rating Curves= 0
DSS Export Rating Curve Sorted= 0
DSS Export Volume Flow Curves= 0
DXF OffsetX= 0
DXF OffsetY= 0
DXF ScaleX= 1
DXF ScaleY= 10

--- Town_Creek_FINAL.p02 (plan) ---

Plan Title=Town Creek floodway
Version=Version 3.0.1  Mar 2001
Short Identifier=floodway
Geom File=g01
Flow File=f02
Subcritical Flow
K Sum by GR= 0
Std Step Tol= 0.01
Critical Tol= 0.01
Num of Std Step Trials= 20
Max Error Tol= 0.3
Flow Tol Ratio= 0.001
Split Flow NTrial= 30
Split Flow Tol= 0.02
Split Flow Ratio= 0.02
Log Output Level= 0
Friction Slope Method= 1
Unsteady Friction Slope Method= 2
Parabolic Critical Depth
Global Vel Dist= 0 , 0 , 0
Global Log Level= 0
CheckData=True
Encroach Param=-1 ,0,0, 2
Encroach River=Town Creek
Encroach Reach=Reach - 1
Encroach Node=190759.0
       1 4935.38 5053.86
Encroach Node=190101.0
       1    4900  5019.8
Encroach Node=189690.0
       1 4889.87    5050
Encroach Node=189547.9
       1    4970  5020.2
Encroach Node=189519.9
       1    4970  5020.2
Encroach Node=189491.9
       1    4970  5020.2
Encroach Node=189137.0
       1  4920.5 5085.49
Encroach Node=188529.0
       1    4940    5060
Encroach Node=188133.9
       1  4979.6  5028.2
Encroach Node=188071.4
       1  4979.6  5028.2
Encroach Node=188008.9
       1  4979.6  5028.2
Encroach Node=187178.0
       1  4783.5 5025.73
Encroach Node=186553.0
       1 4814.92    5075
Encroach Node=186242.0
       1 4878.19 5085.92
Encroach Node=185892.0
       1 4863.92 5067.68
Encroach Node=185685.9
       1  4976.1  5022.4
Encroach Node=185666.9
       1  4976.1  5022.4
Encroach Node=185647.9
       1  4976.1  5022.4
Encroach Node=185314.0
       1 4983.15 5016.85
Encroach Node=185196.4
       1  4809.7 5061.49
Encroach Node=185172.9
       1  4809.7 5061.49
Encroach Node=185149.4
       1  4809.7 5061.49
Encroach Node=184581.0
       1 4831.19 5034.47
Encroach Node=184186.0
       1 4818.23 5032.44
Encroach Node=183496.0
       1 4722.99 5016.85
Encroach Node=182925.0
       1    4766 5016.85
Encroach Node=182518.0
       1  4814.2 5042.95
Encroach Node=182161.0
       1 4902.31 5118.56
Encroach Node=181652.0
       1 4952.96 5096.34
Encroach Node=180980.0
       1    4900    5062
Encroach Node=180523.0
       1 4834.14 5016.85
Encroach Node=180072.0
       1 4937.74 5216.52
Encroach Node=179581.8
       1  4953.8  5050.2
Encroach Node=179550.8
       1  4953.8  5050.2
Encroach Node=179519.8
       1  4953.8  5050.2
Encroach Node=178690.0
       1  4951.8  5048.2
Encroach Node=178179.0
       1  4951.8  5048.2
Encroach Node=177762.0
       1    4925    5075
Encroach Node=177516.5
       1    4965    5150
Computation Interval=1HOUR
Output Interval=1HOUR
Run HTab= 0
Run UNet= 0
Run PostProcess= 0
UNET Theta= 1
UNET ZTol= 0.02
UNET ZSATol= 0.1
UNET MxIter= 20
UNET MaxInSteps= 20
UNET DtIC= 0
UNET DtMin= 0
UNET MaxCRTS= 20
UNET WFStab= 2
UNET SFStab= 1
UNET WFX= 1
UNET SFX= 1
UNET Convert EG Bridges=-1
UNET Use Existing IB Tables=-1
Instantaneous Interval=1HOUR
Write IC File= 0
Write Velocity= 0
Write Detailed= 0

--- Town_Creek_FINAL.p01 (plan) ---

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Plan Title=Town Creek
Short Identifier=Base Plan
Geom File= g01
Flow File= f01
Interactive Comp Mode
Encroach Param= -1, 0, 0, 0

--- Town_Creek_FINAL.f02 (steady flow) ---

Flow Title=floodway
Version=Version 3.0.1  Mar 2001
Number of Profiles= 2
Profile Names=100-YEAR,100-YR FW
River Rch & RM=Town Creek,Reach - 1       ,190759.0
    1490    1490
River Rch & RM=Town Creek,Reach - 1       ,186553
    1520    1520
River Rch & RM=Town Creek,Reach - 1       ,184186
    1560    1560
River Rch & RM=Town Creek,Reach - 1       ,181652
    1590    1590
River Rch & RM=Town Creek,Reach - 1       ,177762.0
    1670    1670
Boundary for River Rch & Prof#=Town Creek,Reach - 1       , 1
Up Type= 0
Dn Type= 1
Dn Known WS=96.32
Boundary for River Rch & Prof#=Town Creek,Reach - 1       , 2
Up Type= 0
Dn Type= 1
Dn Known WS=97.32
DSS Import GetInterval= 0
DSS Import GetPeak= 0
DSS Import FillOption= 0

--- Town_Creek_FINAL.f01 (steady flow) ---

Flow Title=Town Creek
Number of Profiles= 4
Profile Names=10-YEAR,50-YEAR,100-YEAR,500-YEAR
River Rch & RM=Town Creek,Reach - 1,190759
     629    1230    1490    2290
River Rch & RM=Town Creek,Reach - 1,186553
     642    1260    1520    2350
River Rch & RM=Town Creek,Reach - 1,184186
     655    1290    1560    2420
River Rch & RM=Town Creek,Reach - 1,181652
     667    1310    1590    2480
River Rch & RM=Town Creek,Reach - 1,177762.0
     748    1350    1670    2590
Boundary for River Rch & Prof#=Town Creek,Reach - 1, 1
Up Type= 0
Dn Type= 1
Dn Known WS=94.31
Boundary for River Rch & Prof#=Town Creek,Reach - 1, 2
Up Type= 0
Dn Type= 1
Dn Known WS=95.73
Boundary for River Rch & Prof#=Town Creek,Reach - 1, 3
Up Type= 0
Dn Type= 1
Dn Known WS=96.32
Boundary for River Rch & Prof#=Town Creek,Reach - 1, 4
Up Type= 0
Dn Type= 1
Dn Known WS=97.68

--- Town_Creek_FINAL.g01 (geometry) ---

Geom Title=Geom 01 by CodeH2 for Windows
Version=Version 3.0.1  Mar 2001

River Reach=Town Creek      ,Reach - 1
Reach XY= 2
              .5             .95              .5             .05

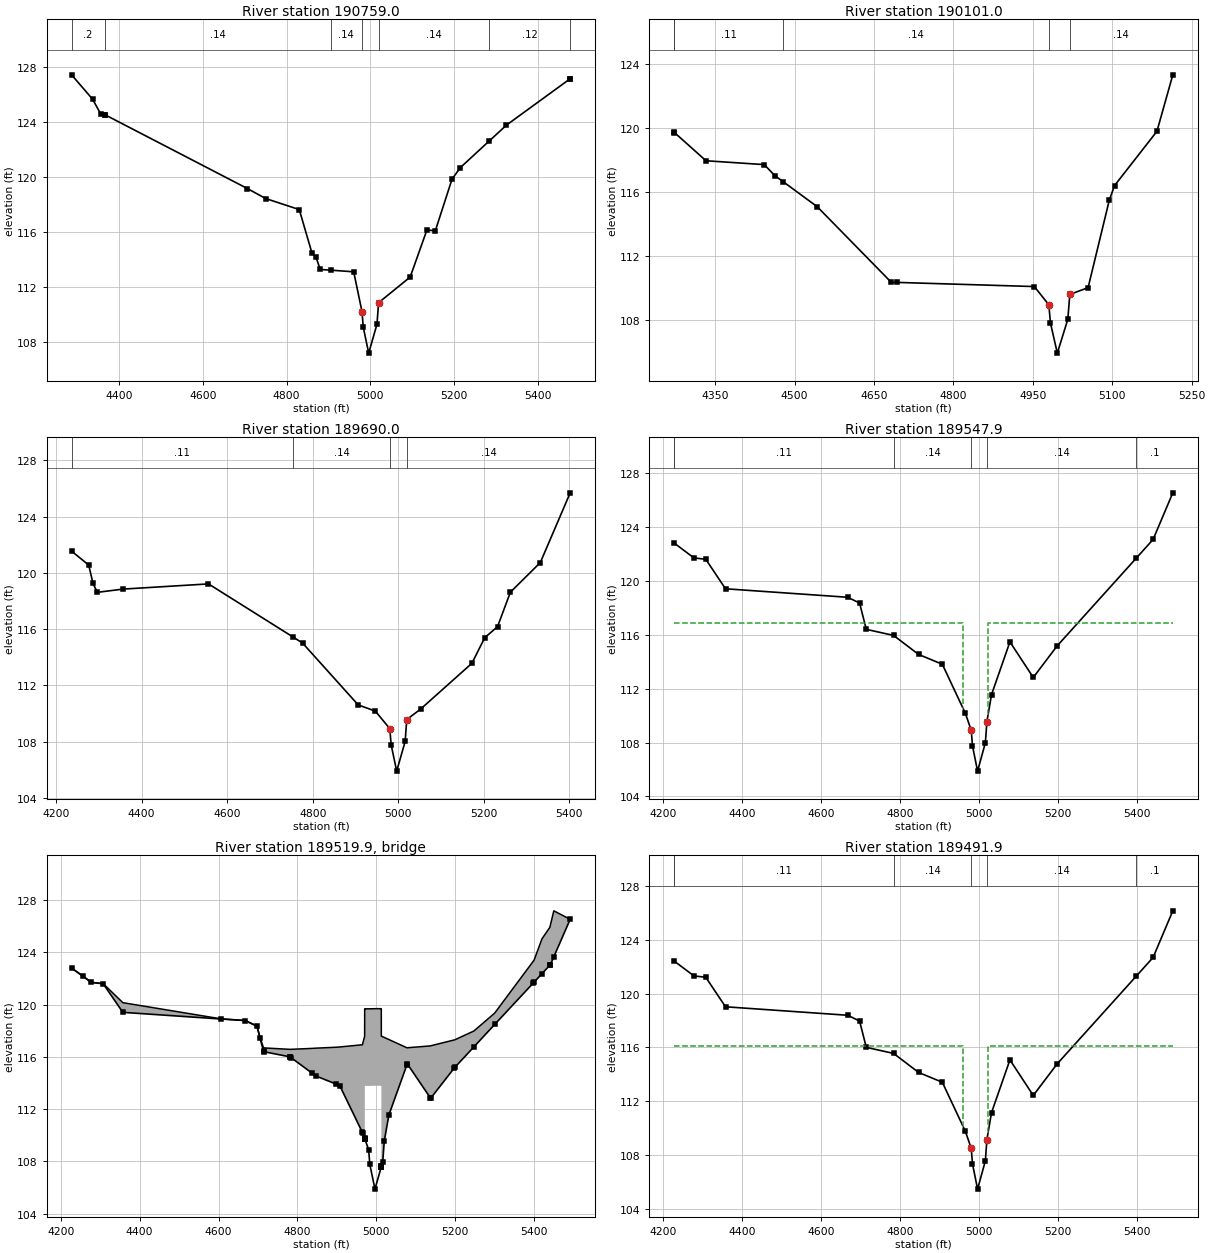
Type RM Length L Ch R = 1 ,190759.0,658,658,658
BEGIN DESCRIPTION:
Cross Section Town Creek 27.0
END DESCRIPTION:
#Sta/Elev= 27
  4286.5  127.45  4336.5  125.68  4356.5  124.58  4365.3  124.54  4366.5  124.54
  4706.5  119.17  4750.4  118.44  4830.4  117.64  4860.4   114.5  4870.4  114.17
  4880.4  113.28  4905.5  113.23  4960.4  113.11  4980.2  110.21  4983.2  109.08
  4996.2  107.19    5016   109.3  5019.8  110.86  5095.3  112.73  5135.3  116.16
  5155.3  116.09  5195.3  119.86  5215.3   120.7  5282.9   122.6  5325.3  123.79
  5477.3  127.16  5477.5  127.16
#Mann= 7 , 1 , 0
  4286.5      .2       0  4365.3     .14       0  4905.5     .14       0
  4980.2    .055       0  5019.8     .14       0  5282.9     .12       0
  5477.3      .2       0
Bank Sta=4980.2,5019.8
XS Rating Curve= 0
Exp/Cntr=.3,.1

Type RM Length L Ch R = 1 ,190101.0,411,411,411
BEGIN DESCRIPTION:
Cross Section Town Creek 26.0
END DESCRIPTION:
#Sta/Elev= 20
  4272.8  119.75  4273.3  119.74  4332.8  117.98  4442.8  117.74  4462.8  117.05
  4478.2  116.68  4542.8  115.11  4682.8  110.38  4692.8  110.38  4952.8  110.12
  4980.2  108.98  4983.2  107.85  4996.2  105.96    5016  108.07  5019.8  109.63
  5054.3  110.05  5094.3  115.51  5104.3  116.43  5184.3  119.82  5214.3  123.35
#Mann= 5 , 1 , 0
  4272.8      .2       0  4273.3     .11       0  4478.2     .14       0
  4980.2    .055       0  5019.8     .14       0
Bank Sta=4980.2,5019.8
XS Rating Curve= 0
Exp/Cntr=.3,.1

Type RM Length L Ch R = 1 ,189690.0,142.1,142.1,142.1
BEGIN DESCRIPTION:
Cross Section Town Creek 25.0
END DESCRIPTION:
#Sta/Elev= 22
  4236.3  121.55  4276.3  120.56  4286.3  119.26  4296.3  118.62  4356.3  118.85
  4556.3  119.22  4754.5  115.43  4776.3  115.01  4906.3  110.61  4946.3  110.17
  4980.2  108.92  4983.2  107.79  4996.2   105.9    5016  108.01  5019.8  109.57
    5052  110.31    5172  113.57    5202  115.39    5232  116.18    5262  118.63
    5332  120.74  5401.8   125.7
#Mann= 4 , 1 , 0
  4236.3     .11       0  4754.5     .14       0  4980.2    .055       0
  5019.8     .14       0
Bank Sta=4980.2,5019.8
XS Rating Curve= 0
Exp/Cntr=.5,.3

Type RM Length L Ch R = 1 ,189547.9,56,56,56
BEGIN DESCRIPTION:
Upstream Section of Bridge/Culvert/Weir
END DESCRIPTION:
#Sta/Elev= 23
  4227.5   122.8  4277.5   121.7  4307.5   121.6  4357.5  119.41  4667.5  118.78
  4697.5  118.35  4714.4   116.4  4783.6  115.95    4847  114.54  4907.2  113.81
  4965.5  110.18  4980.6   108.9  4983.6  107.77  4996.6  105.88  5016.4  107.99
  5020.2  109.55  5031.9  111.55  5078.6  115.47  5137.8  112.83    5198  115.16
  5398.2  121.66  5441.6  123.07  5491.6  126.53
#Mann= 6 , 1 , 0
  4227.5      .2       0  4227.5     .11       0  4783.6     .14       0
  4980.6    .055       0  5020.2     .14       0  5398.2      .1       0
#XS Ineff= 2 , 0
       0    4960   116.9    5023       0   116.9
Permanent Ineff=
       F       F
Bank Sta=4980.6,5020.2
XS Rating Curve= 0
Exp/Cntr=.5,.3

Type RM Length L Ch R = 3 ,189519.9,,,
BEGIN DESCRIPTION:
Elm City Road
Structure ID: W_TOC-5
END DESCRIPTION:
Bridge Culvert--1,0,-1,-1, 0
Deck Dist Width WeirC Skew NumUp NumDn MinLoCord MaxHiCord MaxSubmerge Is_Ogee
10,36,2.6,0, 53, 53, , , .95, 0, 1,1,,
  4227.5  4256.8  4277.5  4307.5  4357.5  4606.8  4667.5  4697.5  4705.5  4714.2
  4714.4  4780.2  4781.5  4783.6  4836.2    4847  4898.8  4907.2  4964.8  4965.5
 4970.47 4970.58 4970.69 4970.91    4971  4971.1  4980.6  4983.6  4996.6  5012.5
 5012.56 5012.67 5012.78 5012.89    5013  5016.4  5020.2  5031.9  5077.6  5078.6
  5136.5  5137.8    5198  5199.2  5247.3  5300.1  5398.2  5400.1  5420.1  5440.1
  5441.6  5450.1  5491.6
   122.8  122.17  121.71  121.61  120.15  118.91  118.79  118.36  117.44  116.69
  116.69  116.58  116.58  116.58  116.65  116.67  116.74  116.76  116.93  117.01
  117.58  119.68  119.68  119.68  119.68  119.68  119.68  119.68  119.69  119.69
  119.69  119.69  117.59  117.59  117.59  117.54  117.49  117.33   116.7   116.7
  116.84  116.85   117.3  117.31  117.98  119.35  123.33  123.41  125.04  125.92
  126.11  127.18  126.53
   122.8  122.16   121.7   121.6  119.41   118.9  118.78  118.35  117.43  116.42
   116.4  116.01     116  115.95  114.78  114.54  113.91  113.81  110.22  110.18
  109.76  109.75  109.74  109.72  113.78  113.78  113.78  113.78  113.79  113.79
  113.79  113.79  113.79  113.79  107.63  107.99  109.55  111.55  115.39  115.47
  112.89  112.83  115.16   115.2  116.76  118.48  121.66  121.72  122.37  123.02
  123.07  123.66  126.53
  4227.5  4256.8  4277.5  4307.5  4357.5  4606.8  4667.5  4697.5  4705.5  4714.2
  4714.4  4780.2  4781.5  4783.6  4836.2    4847  4898.8  4907.2  4964.8  4965.5
 4970.47 4970.58 4970.69 4970.91    4971  4971.1  4980.6  4983.6  4996.6  5012.5
 5012.56 5012.67 5012.78 5012.89    5013  5016.4  5020.2  5031.9  5077.6  5078.6
  5136.5  5137.8    5198  5199.2  5247.3  5300.1  5398.2  5400.1  5420.1  5440.1
  5441.6  5450.1  5491.6
   122.8  122.17  121.71  121.61  120.15  118.91  118.79  118.36  117.44  116.69
  116.69  116.58  116.58  116.58  116.65  116.67  116.74  116.76  116.93  117.01
  117.58  119.68  119.68  119.68  119.68  119.68  119.68  119.68  119.69  119.69
  119.69  119.69  117.59  117.59  117.59  117.54  117.49  117.33   116.7   116.7
  116.84  116.85   117.3  117.31  117.98  119.35  123.33  123.41  125.04  125.92
  126.11  127.18  126.53
  122.42  121.78  121.32  121.22  119.03  118.52   118.4  117.97  117.05  116.04
  116.02  115.63  115.62  115.57   114.4  114.16  113.53  113.43  109.84   109.8
  109.38  109.37  109.36  109.34   113.4   113.4   113.4   113.4  113.41  113.41
  113.41  113.41  113.41  113.41  107.25  107.61  109.17  111.17  115.01  115.09
  112.51  112.45  114.78  114.82  116.38   118.1  121.28  121.34  121.99  122.64
  122.69  123.28  126.15
BR Coef= 1 , 1 , 0 ,1.25, 0 ,,,.8,0,2,0,
WSPro=,,,, 1 ,,,, 0 ,,,, 0 ,,,,-1 ,-1 ,-1 , 0 , 0 , 0 , 0 , 0
BR U #Sta/Elev= 53
  4227.5   122.8  4256.8  122.16  4277.5   121.7  4307.5   121.6  4357.5  119.41
  4606.8   118.9  4667.5  118.78  4697.5  118.35  4705.5  117.43  4714.2  116.42
  4714.4   116.4  4780.2  116.01  4781.5     116  4783.6  115.95  4836.2  114.78
    4847  114.54  4898.8  113.91  4907.2  113.81  4964.8  110.22  4965.5  110.18
 4970.47  109.76 4970.58  109.75 4970.69  109.74 4970.91  109.72    4971  109.71
  4971.1  109.71  4980.6   108.9  4983.6  107.77  4996.6  105.88  5012.5  107.57
 5012.56  107.58 5012.67  107.59 5012.78   107.6 5012.89  107.62    5013  107.63
  5016.4  107.99  5020.2  109.55  5031.9  111.55  5077.6  115.39  5078.6  115.47
  5136.5  112.89  5137.8  112.83    5198  115.16  5199.2   115.2  5247.3  116.76
  5300.1  118.48  5398.2  121.66  5400.1  121.72  5420.1  122.37  5440.1  123.02
  5441.6  123.07  5450.1  123.66  5491.6  126.53
BR U #Mann= 6
  4227.5      .2  4227.5     .11  4783.6     .14  4980.6    .055  5020.2     .14
  5398.2      .1
BR U Banks=4980.6,5020.2
BR D #Sta/Elev= 53
  4227.5  122.42  4256.8  121.78  4277.5  121.32  4307.5  121.22  4357.5  119.03
  4606.8  118.52  4667.5   118.4  4697.5  117.97  4705.5  117.05  4714.2  116.04
  4714.4  116.02  4780.2  115.63  4781.5  115.62  4783.6  115.57  4836.2   114.4
    4847  114.16  4898.8  113.53  4907.2  113.43  4964.8  109.84  4965.5   109.8
 4970.47  109.38 4970.58  109.37 4970.69  109.36 4970.91  109.34    4971  109.33
  4971.1  109.33  4980.6  108.52  4983.6  107.39  4996.6   105.5  5012.5  107.19
 5012.56   107.2 5012.67  107.21 5012.78  107.22 5012.89  107.24    5013  107.25
  5016.4  107.61  5020.2  109.17  5031.9  111.17  5077.6  115.01  5078.6  115.09
  5136.5  112.51  5137.8  112.45    5198  114.78  5199.2  114.82  5247.3  116.38
  5300.1   118.1  5398.2  121.28  5400.1  121.34  5420.1  121.99  5440.1  122.64
  5441.6  122.69  5450.1  123.28  5491.6  126.15
BR D #Mann= 6
  4227.5      .2  4227.5     .11  4783.6     .14  4980.6    .055  5020.2     .14
  5398.2      .1
BR D Banks=4980.6,5020.2
BC Design=,, 0 ,, 0 ,,,,,,

Type RM Length L Ch R = 1 ,189491.9,354.9,354.9,354.9
BEGIN DESCRIPTION:
Downstream Section of Bridge/Culvert/Weir
END DESCRIPTION:
#Sta/Elev= 23
  4227.5  122.41  4277.5  121.31  4307.5  121.21  4357.5  119.02  4667.5  118.39
  4697.5  117.96  4714.4  116.01  4783.6  115.56    4847  114.15  4907.2  113.42
  4965.5  109.79  4980.6  108.51  4983.6  107.38  4996.6  105.49  5016.4   107.6
  5020.2  109.16  5031.9  111.16  5078.6  115.08  5137.8  112.44    5198  114.77
  5398.2  121.27  5441.6  122.68  5491.6  126.14
#Mann= 6 , 1 , 0
  4227.5      .2       0  4227.5     .11       0  4783.6     .14       0
  4980.6    .055       0  5020.2     .14       0  5398.2      .1       0
#XS Ineff= 2 , 0
       0    4960   116.1    5023       0   116.1
Permanent Ineff=
       F       F
Bank Sta=4980.6,5020.2
XS Rating Curve= 0
Exp/Cntr=.5,.3

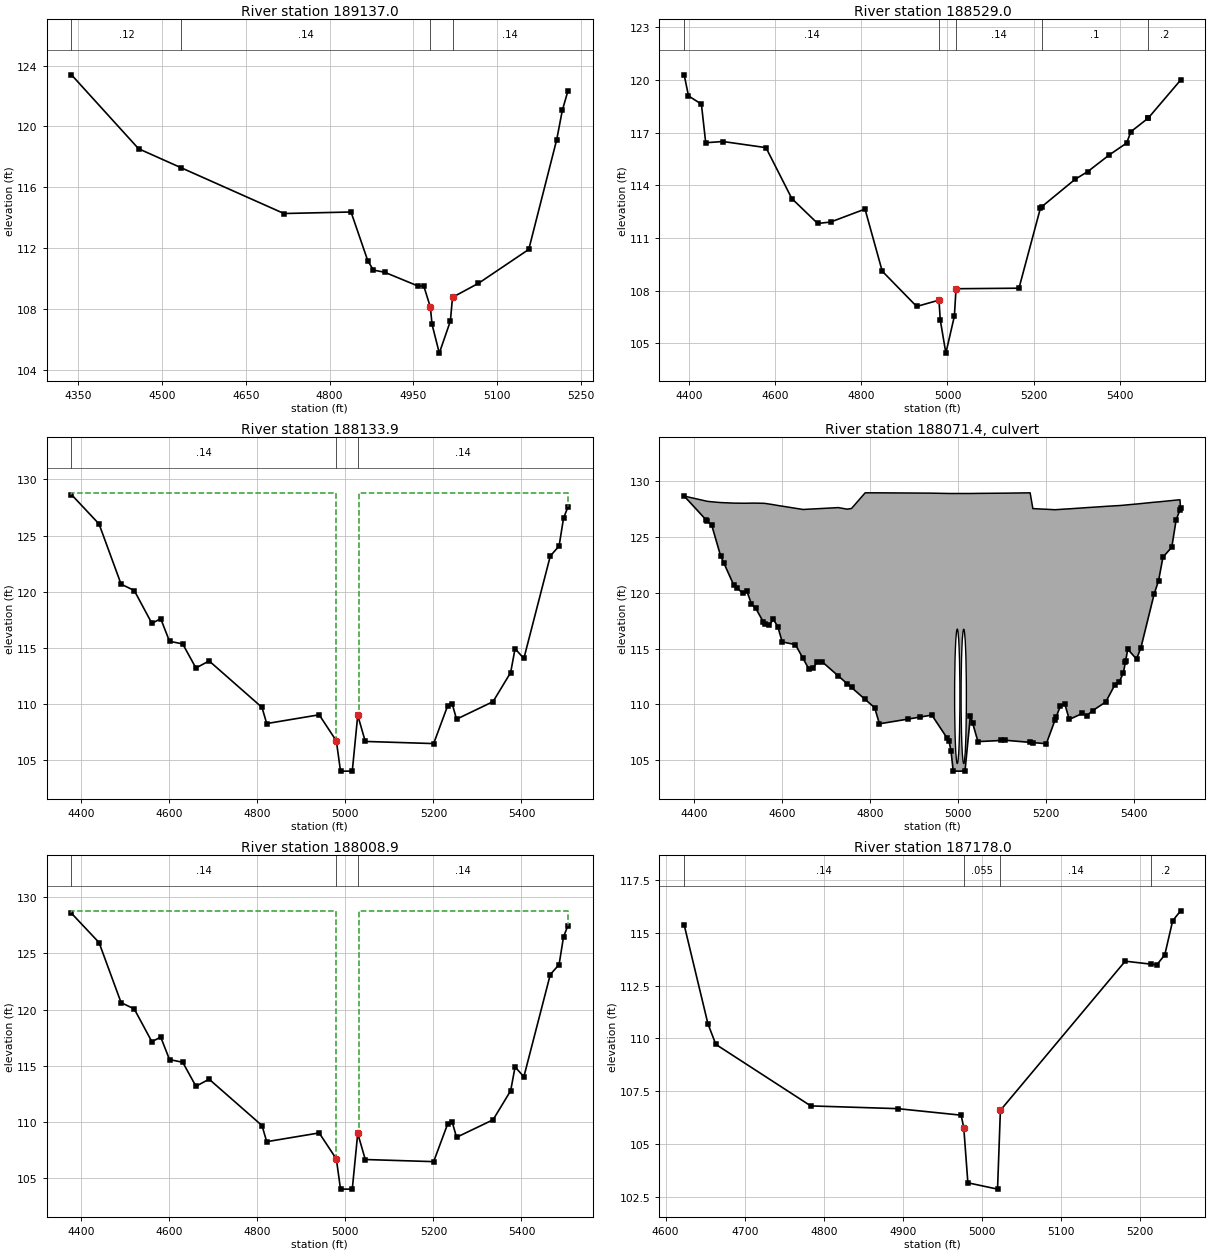
Type RM Length L Ch R = 1 ,189137.0,608,608,608
BEGIN DESCRIPTION:
Cross Section Town Creek 24.0
END DESCRIPTION:
#Sta/Elev= 20
  4338.3  123.39  4458.3  118.53    4535  117.27  4718.3  114.27  4838.3  114.37
  4868.3  111.16  4878.3  110.55  4898.3  110.41  4958.3   109.5  4968.3  109.52
  4980.2  108.11  4983.2  106.98  4996.2  105.09    5016   107.2  5019.8  108.76
  5066.2  109.68  5156.2  111.91  5206.2  119.13  5216.2  121.05  5226.2  122.33
#Mann= 4 , 1 , 0
  4338.3     .12       0    4535     .14       0  4980.2    .055       0
  5019.8     .14       0
Bank Sta=4980.2,5019.8
XS Rating Curve= 0
Exp/Cntr=.3,.1

Type RM Length L Ch R = 1 ,188529.0,395.1,395.1,395.1
BEGIN DESCRIPTION:
Cross Section Town Creek 23.0
END DESCRIPTION:
#Sta/Elev= 28
  4388.4   120.3  4398.4   119.1  4428.4  118.63  4438.4  116.43  4478.4   116.5
  4578.4  116.15  4638.4  113.25  4698.4  111.83  4728.4  111.91  4808.4  112.65
  4848.4  109.11  4928.4   107.1  4980.2  107.46  4983.2  106.33  4996.2  104.44
    5016  106.55  5019.8  108.11    5166  108.14    5216  112.72  5218.8  112.78
    5296  114.34    5326  114.79    5376  115.74    5416  116.41    5426  117.06
    5466  117.83  5466.1  117.83  5541.4     120
#Mann= 5 , 1 , 0
  4388.4     .14       0  4980.2    .055       0  5019.8     .14       0
  5218.8      .1       0    5466      .2       0
Bank Sta=4980.2,5019.8
XS Rating Curve= 0
Exp/Cntr=.5,.3

Type RM Length L Ch R = 1 ,188133.9,125,125,125
BEGIN DESCRIPTION:
Upstream Section of Bridge/Culvert/Weir
END DESCRIPTION:
#Sta/Elev= 30
  4378.1  128.64  4440.7  126.03  4490.7  120.68  4520.7  120.11  4560.7  117.19
  4580.7  117.61  4600.7   115.6  4630.7  115.36  4660.7  113.22  4690.7  113.85
  4810.7  109.72  4821.5  108.28  4940.6  109.06  4979.6  106.74  4989.1  104.05
  5015.8  104.05  5028.2  109.02  5045.3  106.69  5200.6   106.5  5232.6  109.88
  5242.6  110.05  5252.6  108.67  5335.5  110.23  5375.5  112.82  5385.5  114.94
  5405.5  114.07  5465.5  123.18  5485.5  124.07  5495.5  126.53  5505.5  127.54
#Mann= 3 ,-1 , 0
  4378.1     .14       0  4979.6    .055       0  5028.2     .14       0
#XS Ineff= 2 , 0
       0  4979.6   128.8    5030       0   128.8
Permanent Ineff=
       F       F
Bank Sta=4979.6,5028.2
XS Rating Curve= 0
Exp/Cntr=.5,.3

Type RM Length L Ch R = 2 ,188071.4,,,
BEGIN DESCRIPTION:
Railroad
Structure ID: W_TOC-4
END DESCRIPTION:
Bridge Culvert--1,0,-1,-1, 0
Deck Dist Width WeirC Skew NumUp NumDn MinLoCord MaxHiCord MaxSubmerge Is_Ogee
10,105,3,0, 58, 58, , , .95, 0, 1,1,,
  4378.1  4430.7  4440.7  4460.7  4490.7  4510.7  4520.7  4530.7  4540.7  4560.7
  4570.7  4580.7  4590.7  4600.7  4630.7  4648.1  4660.7  4670.7  4680.7  4690.7
  4728.1  4748.1  4758.1  4789.1  4810.7  4821.5  4940.6  4979.6  4984.2  4989.1
  5015.8  5028.2  5045.3  5107.1  5163.8    5170  5200.6    5220  5232.6  5242.6
  5252.6  5282.6  5292.6  5305.5  5335.5  5355.5  5365.5  5375.5  5385.5  5405.5
  5415.5  5445.5  5455.5  5465.5  5485.5  5495.5  5504.1  5505.5
  128.63  128.16  128.12  128.05     128  127.99  127.99     128     128  127.98
  127.92  127.86  127.79  127.73  127.54  127.43  127.46  127.48   127.5  127.52
   127.6  127.46  127.52  128.92  128.92  128.92  128.89  128.86  128.86  128.86
  128.86  128.86  128.87  128.89  128.92  127.51  127.45  127.41  127.44  127.47
  127.49  127.57   127.6  127.63  127.71  127.76  127.78  127.81  127.85  127.92
  127.96  128.08  128.11  128.15  128.23  128.27   128.3  127.53
  128.63  126.38  126.02   123.3  120.67  119.96   120.1     119  118.59  117.18
  117.08   117.6  116.96  115.59  115.35  114.11  113.21  113.26  113.81  113.84
  112.55  111.86  111.52  110.45  109.71  108.27  109.05  106.73  105.81  104.04
  104.04  109.01  106.68   106.8  106.61  106.59  106.49  108.57  109.87  110.04
  108.66   109.2     109  109.44  110.22   111.7  111.97  112.81  114.93  114.06
  115.09  119.88  121.07  123.17  124.06  126.52  127.39  127.53
  4378.1  4430.7  4440.7  4460.7  4490.7  4510.7  4520.7  4530.7  4540.7  4560.7
  4570.7  4580.7  4590.7  4600.7  4630.7  4648.1  4660.7  4670.7  4680.7  4690.7
  4728.1  4748.1  4758.1  4789.1  4810.7  4821.5  4940.6  4979.6  4984.2  4989.1
  5015.8  5028.2  5045.3  5107.1  5163.8    5170  5200.6    5220  5232.6  5242.6
  5252.6  5282.6  5292.6  5305.5  5335.5  5355.5  5365.5  5375.5  5385.5  5405.5
  5415.5  5445.5  5455.5  5465.5  5485.5  5495.5  5504.1  5505.5
  128.63  128.16  128.12  128.05     128  127.99  127.99     128     128  127.98
  127.92  127.86  127.79  127.73  127.54  127.43  127.46  127.48   127.5  127.52
   127.6  127.46  127.52  128.92  128.92  128.92  128.89  128.86  128.86  128.86
  128.86  128.86  128.87  128.89  128.92  127.51  127.45  127.41  127.44  127.47
  127.49  127.57   127.6  127.63  127.71  127.76  127.78  127.81  127.85  127.92
  127.96  128.08  128.11  128.15  128.23  128.27   128.3  127.53
  128.59  126.34  125.98  123.26  120.63  119.92  120.06  118.96  118.55  117.14
  117.04  117.56  116.92  115.55  115.31  114.07  113.17  113.22  113.77   113.8
  112.51  111.82  111.48  110.41  109.67  108.23  109.01  106.69  105.77     104
     104  108.97  106.64  106.76  106.57  106.55  106.45  108.53  109.83     110
  108.62  109.16  108.96   109.4  110.18  111.66  111.93  112.77  114.89  114.02
  115.05  119.84  121.03  123.13  124.02  126.48  127.35  127.49
BR Coef= 1 , 0 , 0 ,1.25, 0 ,,,.8,-1,2,0,
WSPro=,,,, 1 ,,,, 0 ,,,, 0 ,,,,-1 ,-1 ,-1 , 0 , 0 , 0 , 0 , 0
Culvert=1,12,,105,.024,.9,1,2,3,104.73,4998.3,104,4998.3,Culvert #1  , 0 ,10
Culvert Bottom n=.024
Culvert=1,12,,105,.024,.9,1,2,3,104.72,5013,104,5013,Culvert #2  , 0 ,10
Culvert Bottom n=.024
BR U #Sta/Elev= 70
  4378.1  128.63  4428.1  126.49  4430.7  126.38  4440.7  126.02  4460.7   123.3
  4468.1  122.65  4490.7  120.67  4498.1  120.41  4510.7  119.96  4520.7   120.1
  4530.7     119  4540.7  118.59  4558.1  117.36  4560.7  117.18  4570.7  117.08
  4580.7   117.6  4590.7  116.96  4600.7  115.59  4630.7  115.35  4648.1  114.11
  4660.7  113.21  4670.7  113.26  4680.7  113.81  4690.7  113.84  4728.1  112.55
  4748.1  111.86  4758.1  111.52  4789.1  110.45  4810.7  109.71  4821.5  108.27
  4886.2  108.69  4913.2  108.87  4940.6  109.05  4974.9  107.01  4979.6  106.73
  4984.2  105.81  4989.1  104.04  5015.8  104.04  5028.2  109.01  5033.2  108.33
  5045.3  106.68  5098.5  106.78  5107.1   106.8  5163.8  106.61    5170  106.59
  5200.6  106.49    5220  108.57  5222.6  108.85  5232.6  109.87  5242.6  110.04
  5252.6  108.66  5282.6   109.2  5292.6     109  5305.5  109.44  5335.5  110.22
  5355.5   111.7  5365.5  111.97  5375.5  112.81    5380  113.76  5380.8  113.93
  5385.5  114.93  5405.5  114.06  5415.5  115.09  5445.5  119.88  5455.5  121.07
  5465.5  123.17  5485.5  124.06  5495.5  126.52  5504.1  127.39  5505.5  127.53
BR U #Mann= 3
  4378.1     .14  4979.6    .055  5028.2     .14
BR U Banks=4979.6,5028.2
BR D #Sta/Elev= 70
  4378.1  128.59  4428.1  126.45  4430.7  126.34  4440.7  125.98  4460.7  123.26
  4468.1  122.61  4490.7  120.63  4498.1  120.37  4510.7  119.92  4520.7  120.06
  4530.7  118.96  4540.7  118.55  4558.1  117.32  4560.7  117.14  4570.7  117.04
  4580.7  117.56  4590.7  116.92  4600.7  115.55  4630.7  115.31  4648.1  114.07
  4660.7  113.17  4670.7  113.22  4680.7  113.77  4690.7   113.8  4728.1  112.51
  4748.1  111.82  4758.1  111.48  4789.1  110.41  4810.7  109.67  4821.5  108.23
  4886.2  108.65  4913.2  108.83  4940.6  109.01  4974.9  106.97  4979.6  106.69
  4984.2  105.77  4989.1     104  5015.8     104  5028.2  108.97  5033.2  108.29
  5045.3  106.64  5098.5  106.74  5107.1  106.76  5163.8  106.57    5170  106.55
  5200.6  106.45    5220  108.53  5222.6  108.81  5232.6  109.83  5242.6     110
  5252.6  108.62  5282.6  109.16  5292.6  108.96  5305.5   109.4  5335.5  110.18
  5355.5  111.66  5365.5  111.93  5375.5  112.77    5380  113.72  5380.8  113.89
  5385.5  114.89  5405.5  114.02  5415.5  115.05  5445.5  119.84  5455.5  121.03
  5465.5  123.13  5485.5  124.02  5495.5  126.48  5504.1  127.35  5505.5  127.49
BR D #Mann= 3
  4378.1     .14  4979.6    .055  5028.2     .14
BR D Banks=4979.6,5028.2
BC Design=,, 0 ,, 0 ,,,,,,

Type RM Length L Ch R = 1 ,188008.9,830.9,830.9,830.9
BEGIN DESCRIPTION:
Downstream Section of Bridge/Culvert/Weir
END DESCRIPTION:
#Sta/Elev= 30
  4378.1  128.58  4440.7  125.97  4490.7  120.62  4520.7  120.05  4560.7  117.13
  4580.7  117.55  4600.7  115.54  4630.7   115.3  4660.7  113.16  4690.7  113.79
  4810.7  109.66  4821.5  108.22  4940.6     109  4979.6  106.68  4989.1  103.99
  5015.8  103.99  5028.2  108.96  5045.3  106.63  5200.6  106.44  5232.6  109.82
  5242.6  109.99  5252.6  108.61  5335.5  110.17  5375.5  112.76  5385.5  114.88
  5405.5  114.01  5465.5  123.12  5485.5  124.01  5495.5  126.47  5505.5  127.48
#Mann= 3 ,-1 , 0
  4378.1     .14       0  4979.6    .055       0  5028.2     .14       0
#XS Ineff= 2 , 0
       0  4979.6   128.8    5030       0   128.8
Permanent Ineff=
       F       F
Bank Sta=4979.6,5028.2
XS Rating Curve= 0
Exp/Cntr=.5,.3

Type RM Length L Ch R = 1 ,187178.0,625,625,625
BEGIN DESCRIPTION:
Cross Section Town Creek 20.0
END DESCRIPTION:
#Sta/Elev= 16
  4623.5  115.39  4653.5   110.7  4663.5  109.72  4783.5   106.8  4893.5  106.67
  4973.5  106.36 4976.85  105.77 4982.05  103.15 5019.55  102.85 5023.15  106.59
  5180.9  113.67  5213.2  113.53  5220.9   113.5  5230.9  113.97  5240.9  115.59
  5250.9  116.06
#Mann= 4 , 1 , 0
  4623.5     .14       0 4976.85    .055       0 5023.15     .14       0
  5213.2      .2       0
Bank Sta=4976.85,5023.15
XS Rating Curve= 0
Exp/Cntr=.3,.1

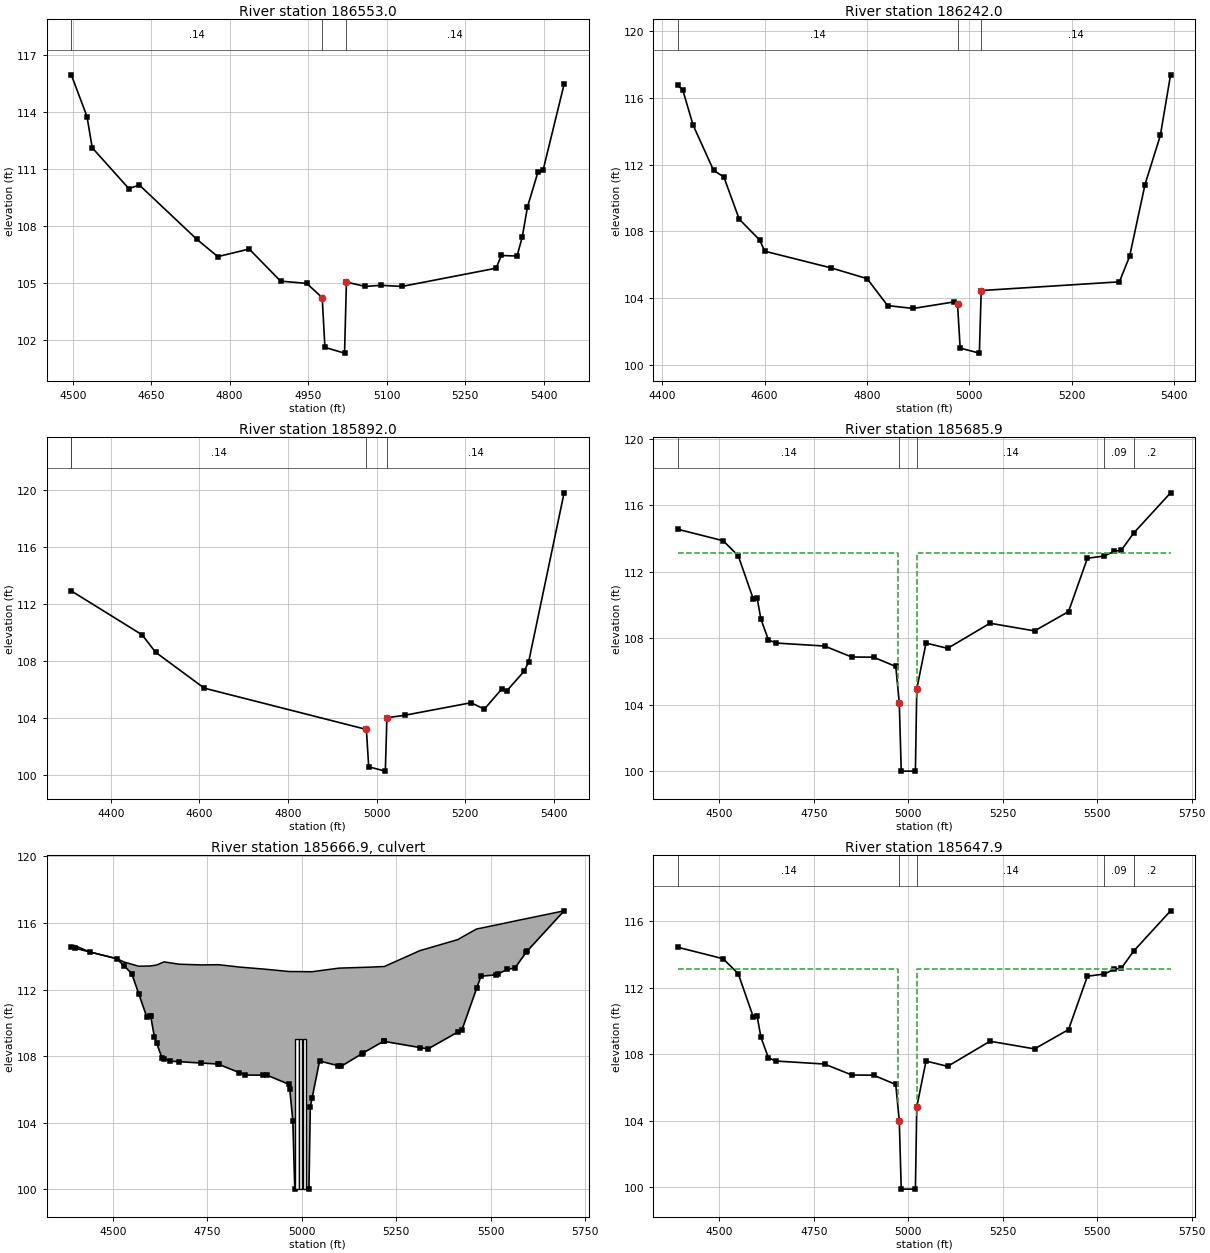
Type RM Length L Ch R = 1 ,186553.0,311,311,311
BEGIN DESCRIPTION:
Cross Section Town Creek 19.0
END DESCRIPTION:
#Sta/Elev= 25
  4497.3  115.94  4527.3  113.74  4537.3   112.1  4607.3  109.95  4627.3  110.14
  4737.3  107.28  4777.3  106.37  4837.3  106.77  4897.3  105.08  4947.3  104.96
 4976.85  104.21 4982.05  101.59 5019.55  101.29 5023.15  105.03  5059.2   104.8
  5089.2  104.86  5129.2   104.8  5309.2  105.76  5319.2  106.43  5349.2   106.4
  5359.2   107.4  5369.2  108.99  5389.2  110.82  5399.2  110.94  5439.2  115.45
#Mann= 3 , 1 , 0
  4497.3     .14       0 4976.85    .055       0 5023.15     .14       0
Bank Sta=4976.85,5023.15
XS Rating Curve= 0
Exp/Cntr=.3,.1

Type RM Length L Ch R = 1 ,186242.0,350,350,350
BEGIN DESCRIPTION:
Cross Section Town Creek 18.0
END DESCRIPTION:
#Sta/Elev= 22
  4430.2  116.74  4440.2  116.43  4460.2  114.35  4500.2  111.65  4520.2  111.26
  4550.2  108.74  4590.2  107.49  4600.2  106.82  4730.2  105.82  4800.2  105.18
  4840.2  103.57  4890.2   103.4  4970.2  103.79 4976.85  103.65 4982.05  101.03
 5019.55  100.73 5023.15  104.47  5293.2  104.99  5313.2  106.52  5343.2   110.8
  5373.2  113.74  5393.2  117.36
#Mann= 3 , 1 , 0
  4430.2     .14       0 4976.85    .055       0 5023.15     .14       0
Bank Sta=4976.85,5023.15
XS Rating Curve= 0
Exp/Cntr=.3,.1

Type RM Length L Ch R = 1 ,185892.0,206.1,206.1,206.1
BEGIN DESCRIPTION:
Cross Section Town Creek 17.0
END DESCRIPTION:
#Sta/Elev= 16
    4311   112.9    4471  109.82    4501  108.61    4611  106.09 4976.85   103.2
 4982.05  100.58 5019.55  100.28 5023.15  104.02    5063  104.19    5213  105.07
    5243  104.62    5283  106.06    5293  105.88    5333  107.28    5343  107.94
    5423  119.77
#Mann= 4 , 1 , 0
    4311      .2       0    4311     .14       0 4976.85    .055       0
 5023.15     .14       0
Bank Sta=4976.85,5023.15
XS Rating Curve= 0
Exp/Cntr=.5,.3

Type RM Length L Ch R = 1 ,185685.9,38,38,38
BEGIN DESCRIPTION:
Upstream Section of Bridge/Culvert/Weir
END DESCRIPTION:
#Sta/Elev= 27
  4389.8  114.55  4509.8  113.86  4549.8  112.96  4589.8  110.35  4599.8  110.42
  4609.8  109.15  4629.8   107.9  4649.8  107.71  4778.2  107.53  4850.4  106.87
  4907.9  106.86  4966.8   106.3  4976.1  104.13  4981.3  100.01  5018.8  100.01
  5022.4  104.95  5046.9  107.71    5104  107.39  5216.3   108.9  5334.1  108.44
  5424.1   109.6  5474.1  112.81  5518.8  112.94  5544.1  113.22  5564.1   113.3
  5596.5  114.32  5694.2  116.74
#Mann= 5 , 1 , 0
  4389.8     .14       0  4976.1    .055       0  5022.4     .14       0
  5518.8     .09       0  5596.5      .2       0
#XS Ineff= 2 , 0
       0    4972   113.1    5022       0   113.1
Permanent Ineff=
       F       F
Bank Sta=4976.1,5022.4
XS Rating Curve= 0
Exp/Cntr=.5,.3

Type RM Length L Ch R = 2 ,185666.9,,,
BEGIN DESCRIPTION:
US 301
Structure ID: W_TOC-3
END DESCRIPTION:
Bridge Culvert--1,0,-1,-1, 0
Deck Dist Width WeirC Skew NumUp NumDn MinLoCord MaxHiCord MaxSubmerge Is_Ogee
10,18,3,0, 50, 50, , , .95, 0, 1,1,,
  4389.8  4398.3  4438.3  4509.8  4529.8  4549.8  4568.3  4589.8  4598.3  4599.8
  4609.8  4615.5  4629.8  4635.5  4649.8  4675.5  4733.4  4778.2  4780.2  4834.7
  4850.4  4898.4  4907.9  4966.8  4967.9  4976.1  4981.3  5018.8  5022.4  5027.3
  5046.9  5096.3    5104  5159.8  5161.8  5216.3  5218.1  5312.7  5334.1  5412.7
  5424.1  5462.7  5474.1  5514.1  5518.8  5544.1  5564.1  5594.1  5596.5  5694.2
  114.54  114.65  114.26  113.86  113.65  113.52   113.4  113.41  113.41  113.42
  113.45  113.47  113.61  113.66  113.61  113.52  113.48  113.49  113.49  113.35
  113.32  113.23  113.21  113.08  113.08  113.08  113.08  113.07  113.07  113.07
  113.13  113.28  113.29  113.33  113.33  113.38  113.38  114.34  114.48     115
  115.15  115.64  115.69  115.88   115.9  116.02  116.12  116.26  116.27  116.73
  114.54  114.49  114.26  113.85  113.42  112.95  111.74  110.34   110.4  110.41
  109.14  108.78  107.89  107.84   107.7  107.66  107.58  107.52   107.5     107
  106.86  106.85  106.85  106.29  106.03  104.12     100     100  104.94  105.49
   107.7  107.42  107.38  108.15  108.18  108.89  108.88  108.51  108.43  109.44
  109.59  112.07   112.8  112.88  112.93  113.21  113.29  114.25  114.31  116.73
  4389.8  4398.3  4438.3  4509.8  4529.8  4549.8  4568.3  4589.8  4598.3  4599.8
  4609.8  4615.5  4629.8  4635.5  4649.8  4675.5  4733.4  4778.2  4780.2  4834.7
  4850.4  4898.4  4907.9  4966.8  4967.9  4976.1  4981.3  5018.8  5022.4  5027.3
  5046.9  5096.3    5104  5159.8  5161.8  5216.3  5218.1  5312.7  5334.1  5412.7
  5424.1  5462.7  5474.1  5514.1  5518.8  5544.1  5564.1  5594.1  5596.5  5694.2
  114.54  114.65  114.26  113.86  113.65  113.52   113.4  113.41  113.41  113.42
  113.45  113.47  113.61  113.66  113.61  113.52  113.48  113.49  113.49  113.35
  113.32  113.23  113.21  113.08  113.08  113.08  113.08  113.07  113.07  113.07
  113.13  113.28  113.29  113.33  113.33  113.38  113.38  114.34  114.48     115
  115.15  115.64  115.69  115.88   115.9  116.02  116.12  116.26  116.27  116.73
  114.47  114.42  114.19  113.78  113.35  112.88  111.67  110.27  110.33  110.34
  109.07  108.71  107.82  107.77  107.63  107.59  107.51  107.45  107.43  106.93
  106.79  106.78  106.78  106.22  105.96  104.05   99.93   99.93  104.87  105.42
  107.63  107.35  107.31  108.08  108.11  108.82  108.81  108.44  108.36  109.37
  109.52     112  112.73  112.81  112.86  113.14  113.22  114.18  114.24  116.66
BR Coef= 1 , 0 , 0 ,1.25, 0 ,,,.8,-1,2,0,
WSPro=,,,, 1 ,,,, 0 ,,,, 0 ,,,,-1 ,-1 ,-1 , 0 , 0 , 0 , 0 , 0
Culvert=2,9,9,18,.015,.4,1,8,1,100.02,4987.2,99.93,4987.2,Culvert #1  , 0 ,10
Culvert Bottom n=.015
Culvert=2,9,9,18,.015,.4,1,8,1,100.03,4997.1,99.93,4997.1,Culvert #2  , 0 ,10
Culvert Bottom n=.015
Culvert=2,9,9,18,.015,.4,1,8,1,100.03,5007,99.93,5007,Culvert #3  , 0 ,10
Culvert Bottom n=.015
BR U #Sta/Elev= 50
  4389.8  114.54  4398.3  114.49  4438.3  114.26  4509.8  113.85  4529.8  113.42
  4549.8  112.95  4568.3  111.74  4589.8  110.34  4598.3   110.4  4599.8  110.41
  4609.8  109.14  4615.5  108.78  4629.8  107.89  4635.5  107.84  4649.8   107.7
  4675.5  107.66  4733.4  107.58  4778.2  107.52  4780.2   107.5  4834.7     107
  4850.4  106.86  4898.4  106.85  4907.9  106.85  4966.8  106.29  4967.9  106.03
  4976.1  104.12  4981.3     100  5018.8     100  5022.4  104.94  5027.3  105.49
  5046.9   107.7  5096.3  107.42    5104  107.38  5159.8  108.15  5161.8  108.18
  5216.3  108.89  5218.1  108.88  5312.7  108.51  5334.1  108.43  5412.7  109.44
  5424.1  109.59  5462.7  112.07  5474.1   112.8  5514.1  112.88  5518.8  112.93
  5544.1  113.21  5564.1  113.29  5594.1  114.25  5596.5  114.31  5694.2  116.73
BR U #Mann= 5
  4389.8     .14  4976.1    .055  5022.4     .14  5518.8     .09  5596.5      .2
BR U Banks=4976.1,5022.4
BR D #Sta/Elev= 50
  4389.8  114.47  4398.3  114.42  4438.3  114.19  4509.8  113.78  4529.8  113.35
  4549.8  112.88  4568.3  111.67  4589.8  110.27  4598.3  110.33  4599.8  110.34
  4609.8  109.07  4615.5  108.71  4629.8  107.82  4635.5  107.77  4649.8  107.63
  4675.5  107.59  4733.4  107.51  4778.2  107.45  4780.2  107.43  4834.7  106.93
  4850.4  106.79  4898.4  106.78  4907.9  106.78  4966.8  106.22  4967.9  105.96
  4976.1  104.05  4981.3   99.93  5018.8   99.93  5022.4  104.87  5027.3  105.42
  5046.9  107.63  5096.3  107.35    5104  107.31  5159.8  108.08  5161.8  108.11
  5216.3  108.82  5218.1  108.81  5312.7  108.44  5334.1  108.36  5412.7  109.37
  5424.1  109.52  5462.7     112  5474.1  112.73  5514.1  112.81  5518.8  112.86
  5544.1  113.14  5564.1  113.22  5594.1  114.18  5596.5  114.24  5694.2  116.66
BR D #Mann= 5
  4389.8     .14  4976.1    .055  5022.4     .14  5518.8     .09  5596.5      .2
BR D Banks=4976.1,5022.4
BC Design=,, 0 ,, 0 ,,,,,,

Type RM Length L Ch R = 1 ,185647.9,333.9,333.9,333.9
BEGIN DESCRIPTION:
Downstream Section of Bridge/Culvert/Weir
END DESCRIPTION:
#Sta/Elev= 27
  4389.8  114.43  4509.8  113.74  4549.8  112.84  4589.8  110.23  4599.8   110.3
  4609.8  109.03  4629.8  107.78  4649.8  107.59  4778.2  107.41  4850.4  106.75
  4907.9  106.74  4966.8  106.18  4976.1  104.01  4981.3   99.89  5018.8   99.89
  5022.4  104.83  5046.9  107.59    5104  107.27  5216.3  108.78  5334.1  108.32
  5424.1  109.48  5474.1  112.69  5518.8  112.82  5544.1   113.1  5564.1  113.18
  5596.5   114.2  5694.2  116.62
#Mann= 5 , 1 , 0
  4389.8     .14       0  4976.1    .055       0  5022.4     .14       0
  5518.8     .09       0  5596.5      .2       0
#XS Ineff= 2 , 0
       0    4972   113.1    5022       0   113.1
Permanent Ineff=
       F       F
Bank Sta=4976.1,5022.4
XS Rating Curve= 0
Exp/Cntr=.5,.3