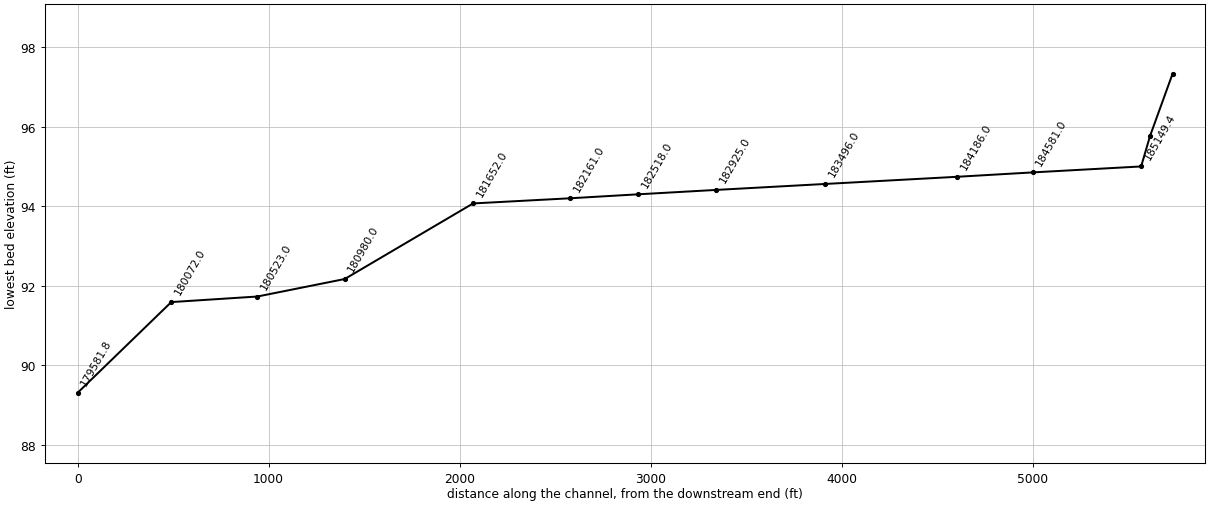
HEC-RAS study Town_Creek_FINAL.PRJ: Town Creek

--- Town_Creek_FINAL.g01 (geometry) --- (continued)

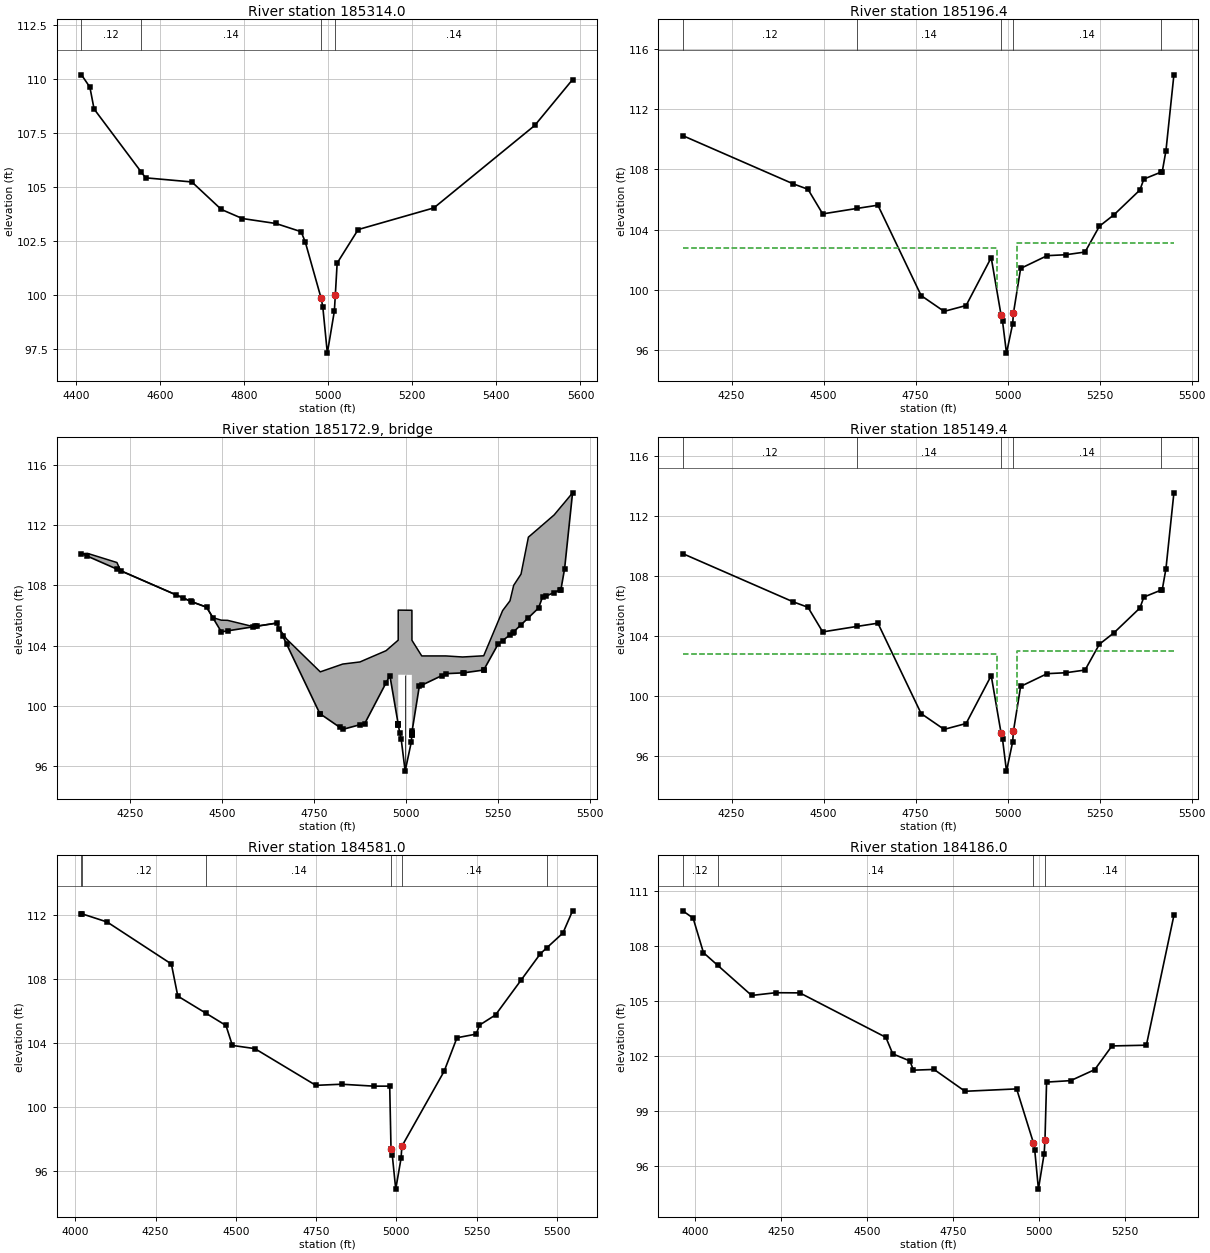
Type RM Length L Ch R = 1 ,185314.0,117.6,117.6,117.6
BEGIN DESCRIPTION:
Cross Section Town Creek 16.0
END DESCRIPTION:
#Sta/Elev= 21
    4413  110.19    4433  109.62    4443  108.61  4555.1   105.7  4565.6  105.43
  4675.6  105.24  4745.6  103.97  4795.6  103.55  4875.6  103.32  4935.6  102.94
  4945.6  102.45 4983.15   99.86 4987.05   99.47 4997.85   97.33 5014.55   99.27
 5016.85  100.01  5021.2  101.49  5071.2  103.04  5251.2  104.04  5491.2  107.85
  5581.2  109.97
#Mann= 4 , 1 , 0
    4413     .12       0  4555.1     .14       0 4983.15    .045       0
 5016.85     .14       0
Bank Sta=4983.15,5016.85
XS Rating Curve= 0
Exp/Cntr=.5,.3

Type RM Length L Ch R = 1 ,185196.4,47,47,47
BEGIN DESCRIPTION:
Upstream Section of Bridge/Culvert/Weir
END DESCRIPTION:
#Sta/Elev= 27
  4117.7  110.25  4417.7  107.04  4457.7  106.68  4497.7  105.04  4589.6   105.4
  4647.7  105.62  4765.2    99.6  4827.5   98.55  4887.3   98.94  4955.5  102.13
  4982.3    98.3  4986.2   97.91    4997   95.77  5013.7   97.71    5016   98.45
  5035.4  101.41  5107.5  102.26  5157.8  102.32  5210.4   102.5  5249.4  104.22
  5289.4  104.99  5359.4  106.63  5370.2  107.36  5416.6  107.82  5420.2  107.86
  5430.2  109.25  5451.8   114.3
#Mann= 5 , 1 , 0
  4117.7     .12       0  4589.6     .14       0  4982.3    .045       0
    5016     .14       0  5416.6     .12       0
#XS Ineff= 2 , 0
       0    4970   102.8    5025       0   103.1
Permanent Ineff=
       F       F
Bank Sta=4982.3,5016
XS Rating Curve= 0
Exp/Cntr=.5,.3

Type RM Length L Ch R = 3 ,185172.9,,,
BEGIN DESCRIPTION:
Rock Quarry Road
Structure ID: W_TOC-2
END DESCRIPTION:
Bridge Culvert--1,0,-1,-1, 0
Deck Dist Width WeirC Skew NumUp NumDn MinLoCord MaxHiCord MaxSubmerge Is_Ogee
10,27,2.6,0, 44, 44, , , .95, 0, 1,1,,
  4117.7    4134    4214    4224  4417.7  4457.7  4474.7  4497.7  4514.7  4584.7
  4647.7  4654.7  4674.7  4766.4  4827.5  4874.3  4887.3  4945.2  4955.5  4978.1
  4978.2  4978.3 5015.19 5015.29  5015.4  5015.5    5016  5035.4  5042.1  5107.5
  5153.1  5210.4  5249.4  5261.8  5281.8  5291.8  5311.8  5331.8  5359.4  5370.2
  5401.8  5420.2  5430.2  5451.8
  110.12  110.14  109.53  108.99  106.92  106.56  105.86  105.69  105.68  105.26
   105.5  105.14  104.44  102.25  102.77  102.91  103.05  103.66  103.88  104.36
  106.36  106.36  106.35  106.35  106.35  104.35  104.33  103.57  103.31  103.31
  103.24  103.32   105.6  106.33  106.98  108.01  108.76  111.22   111.8  112.03
   112.7  113.24  113.53  114.17
  110.12  109.95  109.09  108.98  106.91  106.55  105.85  104.91  104.98  105.25
  105.49  105.13  104.11   99.45   98.42   98.73   98.81  101.52     102   98.77
   98.76  102.06  102.05   98.09   98.13   98.16   98.32  101.28  101.36  102.13
  102.18  102.37  104.09  104.33  104.71  104.92  105.38  105.85   106.5  107.23
  107.53  107.73  109.12  114.17
  4117.7    4134    4214    4224  4417.7  4457.7  4474.7  4497.7  4514.7  4584.7
  4647.7  4654.7  4674.7  4766.4  4827.5  4874.3  4887.3  4945.2  4955.5  4978.1
  4978.2  4978.3 5015.19 5015.29  5015.4  5015.5    5016  5035.4  5042.1  5107.5
  5153.1  5210.4  5249.4  5261.8  5281.8  5291.8  5311.8  5331.8  5359.4  5370.2
  5401.8  5420.2  5430.2  5451.8
  110.12  110.14  109.53  108.99  106.92  106.56  105.86  105.69  105.68  105.26
   105.5  105.14  104.44  102.25  102.77  102.91  103.05  103.66  103.88  104.36
  106.36  106.36  106.35  106.35  106.35  104.35  104.33  103.57  103.31  103.31
  103.24  103.32   105.6  106.33  106.98  108.01  108.76  111.22   111.8  112.03
   112.7  113.24  113.53  114.17
  109.48  109.31  108.45  108.34  106.27  105.91  105.21  104.27  104.34  104.61
  104.85  104.49  103.47   98.81   97.78   98.09   98.17  100.88  101.36   98.13
   98.12  101.42  101.41   97.45   97.49   97.52   97.68  100.64  100.72  101.49
  101.54  101.73  103.45  103.69  104.07  104.28  104.74  105.21  105.86  106.59
  106.89  107.09  108.48  113.53
Pier Skew, UpSta & Num, DnSta & Num=  ,4997, 2 ,4997, 2 , 0 , 0 , 0 ,,
       1       1
    94.7  103.05
       1       1
   94.06  102.41
BR Coef= 1 , 1 , 0 ,1.25, 0 ,,,.8,0,2,0,
WSPro=,,,, 1 ,,,, 0 ,,,, 0 ,,,,-1 ,-1 ,-1 , 0 , 0 , 0 , 0 , 0
BR U #Sta/Elev= 67
  4117.7  110.12    4134  109.95    4214  109.09    4224  108.98    4374  107.38
    4394  107.16    4414  106.95  4417.7  106.91  4457.7  106.55  4474.7  105.85
  4497.7  104.91  4514.7  104.98  4584.7  105.25  4589.6  105.27  4594.7  105.29
  4647.7  105.49  4654.7  105.13  4664.7  104.62  4674.7  104.11  4765.2   99.47
  4766.4   99.45  4819.2   98.56  4827.5   98.42  4874.3   98.73  4887.3   98.81
  4945.2  101.52  4955.5     102 4977.91    98.8 4977.99   98.79  4978.1   98.77
  4978.2   98.76  4978.3   98.74 4978.41   98.73  4982.3   98.17  4986.2   97.78
    4997   95.64  5013.7   97.58  5015.1   98.03 5015.19   98.06 5015.29   98.09
  5015.4   98.13  5015.5   98.16 5015.61   98.19    5016   98.32  5035.4  101.28
  5042.1  101.36  5095.9  101.99  5107.5  102.13  5153.1  102.18  5157.8  102.19
  5210.3  102.37  5210.4  102.37  5249.4  104.09  5261.8  104.33  5281.8  104.71
  5289.4  104.86  5291.8  104.92  5311.8  105.38  5331.8  105.85  5359.4   106.5
  5370.2  107.23  5380.2   107.3  5401.8  107.53  5416.6  107.69  5420.2  107.73
  5430.2  109.12  5451.8  114.17
BR U #Mann= 5
  4117.7     .12  4589.6     .14  4982.3    .045    5016     .14  5416.6     .12
BR U Banks=4982.3,5016
BR D #Sta/Elev= 67
  4117.7  109.48    4134  109.31    4214  108.45    4224  108.34    4374  106.74
    4394  106.52    4414  106.31  4417.7  106.27  4457.7  105.91  4474.7  105.21
  4497.7  104.27  4514.7  104.34  4584.7  104.61  4589.6  104.63  4594.7  104.65
  4647.7  104.85  4654.7  104.49  4664.7  103.98  4674.7  103.47  4765.2   98.83
  4766.4   98.81  4819.2   97.92  4827.5   97.78  4874.3   98.09  4887.3   98.17
  4945.2  100.88  4955.5  101.36 4977.91   98.16 4977.99   98.15  4978.1   98.13
  4978.2   98.12  4978.3    98.1 4978.41   98.09  4982.3   97.53  4986.2   97.14
    4997      95  5013.7   96.94  5015.1   97.39 5015.19   97.42 5015.29   97.45
  5015.4   97.49  5015.5   97.52 5015.61   97.55    5016   97.68  5035.4  100.64
  5042.1  100.72  5095.9  101.35  5107.5  101.49  5153.1  101.54  5157.8  101.55
  5210.3  101.73  5210.4  101.73  5249.4  103.45  5261.8  103.69  5281.8  104.07
  5289.4  104.22  5291.8  104.28  5311.8  104.74  5331.8  105.21  5359.4  105.86
  5370.2  106.59  5380.2  106.66  5401.8  106.89  5416.6  107.05  5420.2  107.09
  5430.2  108.48  5451.8  113.53
BR D #Mann= 5
  4117.7     .12  4589.6     .14  4982.3    .045    5016     .14  5416.6     .12
BR D Banks=4982.3,5016
BC Design=,, 0 ,, 0 ,,,,,,

Type RM Length L Ch R = 1 ,185149.4,568.4,568.4,568.4
BEGIN DESCRIPTION:
Downstream Section of Bridge/Culvert/Weir
END DESCRIPTION:
#Sta/Elev= 27
  4117.7  109.48  4417.7  106.27  4457.7  105.91  4497.7  104.27  4589.6  104.63
  4647.7  104.85  4765.2   98.83  4827.5   97.78  4887.3   98.17  4955.5  101.36
  4982.3   97.53  4986.2   97.14    4997      95  5013.7   96.94    5016   97.68
  5035.4  100.64  5107.5  101.49  5157.8  101.55  5210.4  101.73  5249.4  103.45
  5289.4  104.22  5359.4  105.86  5370.2  106.59  5416.6  107.05  5420.2  107.09
  5430.2  108.48  5451.8  113.53
#Mann= 5 , 1 , 0
  4117.7     .12       0  4589.6     .14       0  4982.3    .045       0
    5016     .14       0  5416.6     .12       0
#XS Ineff= 2 , 0
       0    4970   102.8    5025       0     103
Permanent Ineff=
       F       F
Bank Sta=4982.3,5016
XS Rating Curve= 0
Exp/Cntr=.5,.3

Type RM Length L Ch R = 1 ,184581.0,395,395,395
BEGIN DESCRIPTION:
Cross Section Town Creek 15.0
END DESCRIPTION:
#Sta/Elev= 28
  4019.1   112.1  4019.6   112.1  4099.1  111.58  4299.1  108.95  4319.1  106.94
  4406.5  105.87  4469.1   105.1  4489.1  103.85  4559.1  103.65  4749.1  101.35
  4829.1  101.42  4929.1   101.3  4979.1   101.3 4983.15   97.38 4987.05   96.99
 4997.85   94.85 5014.55   96.79 5016.85   97.53  5148.6  102.23  5188.6  104.33
  5248.6  104.56  5258.6  105.12  5308.6  105.76  5388.6  107.95  5448.6   109.6
  5468.2  109.96  5518.6  110.89  5548.6  112.28
#Mann= 6 , 1 , 0
  4019.1      .2       0  4019.6     .12       0  4406.5     .14       0
 4983.15    .045       0 5016.85     .14       0  5468.2     .12       0
Bank Sta=4983.15,5016.85
XS Rating Curve= 0
Exp/Cntr=.3,.1

Type RM Length L Ch R = 1 ,184186.0,690,690,690
BEGIN DESCRIPTION:
Cross Section Town Creek 14.0
END DESCRIPTION:
#Sta/Elev= 25
  3964.5   109.9  3994.5   109.5  4024.5  107.62  4065.9  106.93  4164.5  105.29
  4234.5  105.44  4304.5  105.43  4554.5  103.01  4574.5  102.11  4624.5  101.72
  4634.5  101.22  4694.5  101.26  4784.5  100.07  4934.5   100.2 4983.15   97.27
 4987.05   96.88 4997.85   94.74 5014.55   96.68 5016.85   97.42  5021.5  100.57
  5091.5  100.65  5161.5  101.25  5211.5  102.54  5311.5  102.58  5391.5  109.65
#Mann= 4 , 1 , 0
  3964.5     .12       0  4065.9     .14       0 4983.15    .045       0
 5016.85     .14       0
Bank Sta=4983.15,5016.85
XS Rating Curve= 0
Exp/Cntr=.3,.1

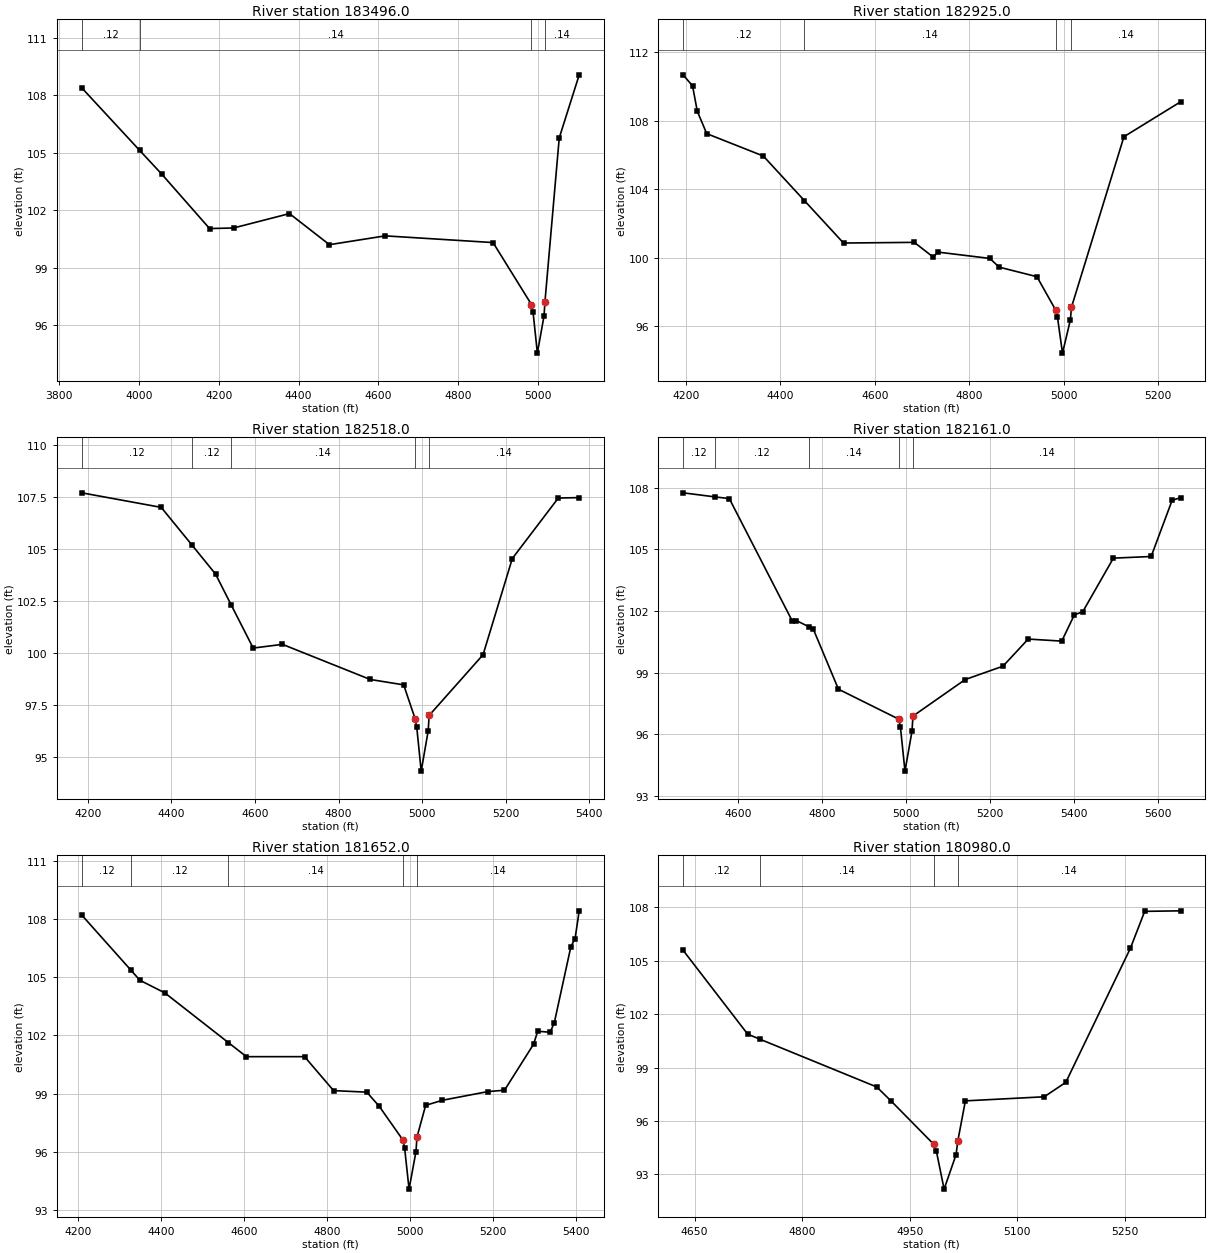
Type RM Length L Ch R = 1 ,183496.0,571,571,571
BEGIN DESCRIPTION:
Cross Section Town Creek 13.0
END DESCRIPTION:
#Sta/Elev= 16
  3857.2  108.38  4001.8  105.13  4057.2  103.89  4177.2  101.05  4237.2  101.08
  4377.2  101.83  4477.2  100.21  4616.9  100.67  4886.9  100.32 4983.15   97.09
 4987.05    96.7 4997.85   94.56 5014.55    96.5 5016.85   97.24  5052.6  105.77
  5102.6  109.06
#Mann= 4 , 1 , 0
  3857.2     .12       0  4001.8     .14       0 4983.15    .045       0
 5016.85     .14       0
Bank Sta=4983.15,5016.85
XS Rating Curve= 0
Exp/Cntr=.3,.1

Type RM Length L Ch R = 1 ,182925.0,407,407,407
BEGIN DESCRIPTION:
Cross Section Town Creek 12.0
END DESCRIPTION:
#Sta/Elev= 20
  4193.7  110.69  4213.7  110.04  4223.7  108.56  4243.7  107.25  4363.7  105.94
  4450.8  103.33  4533.7  100.85  4683.7  100.89  4723.7  100.03  4733.7  100.32
  4843.7   99.95  4863.7   99.44  4943.7   98.88 4983.15   96.94 4987.05   96.55
 4997.85   94.41 5014.55   96.35 5016.85   97.09  5128.1  107.07  5248.1  109.11
#Mann= 4 , 1 , 0
  4193.7     .12       0  4450.8     .14       0 4983.15    .045       0
 5016.85     .14       0
Bank Sta=4983.15,5016.85
XS Rating Curve= 0
Exp/Cntr=.3,.1

Type RM Length L Ch R = 1 ,182518.0,357,357,357
BEGIN DESCRIPTION:
Cross Section Town Creek 11.0
END DESCRIPTION:
#Sta/Elev= 18
  4185.9  107.69  4375.9  106.99  4450.2  105.16  4505.9  103.78  4543.2   102.3
  4595.9  100.22  4665.9   100.4  4875.9   98.71  4955.9   98.45 4983.15   96.83
 4987.05   96.44 4997.85    94.3 5014.55   96.24 5016.85   96.98  5145.8    99.9
  5215.8  104.53  5325.8  107.44  5375.8  107.46
#Mann= 5 , 1 , 0
  4185.9     .12       0  4450.2     .12       0  4543.2     .14       0
 4983.15    .045       0 5016.85     .14       0
Bank Sta=4983.15,5016.85
XS Rating Curve= 0
Exp/Cntr=.3,.1

Type RM Length L Ch R = 1 ,182161.0,509,509,509
BEGIN DESCRIPTION:
Cross Section Town Creek 10.0
END DESCRIPTION:
#Sta/Elev= 23
  4469.3  107.75    4546  107.55  4579.3  107.47  4729.3  101.51  4739.3  101.53
  4768.7  101.23  4779.3  101.12  4839.3   98.19 4983.15   96.73 4987.05   96.34
 4997.85    94.2 5014.55   96.14 5016.85   96.88  5141.4   98.66  5231.4   99.31
  5291.4  100.63  5371.4  100.53  5401.4  101.81  5421.4  101.96  5494.4  104.57
  5584.4  104.65  5634.4  107.39  5654.4  107.51
#Mann= 5 , 1 , 0
  4469.3     .12       0    4546     .12       0  4768.7     .14       0
 4983.15    .045       0 5016.85     .14       0
Bank Sta=4983.15,5016.85
XS Rating Curve= 0
Exp/Cntr=.3,.1

Type RM Length L Ch R = 1 ,181652.0,672,672,672
BEGIN DESCRIPTION:
Cross Section Town Creek 9.0
END DESCRIPTION:
#Sta/Elev= 26
  4209.3   108.2  4328.1  105.35  4349.3  104.84  4409.3  104.19  4562.2  101.63
    4606   100.9    4746   100.9    4816   99.15    4896   99.07    4926   98.34
 4983.15    96.6 4987.05   96.21 4997.85   94.07 5014.55   96.01 5016.85   96.75
  5037.8   98.39  5077.8   98.65  5187.8    99.1  5227.8   99.17  5297.8  101.54
  5307.8  102.21  5337.8  102.16  5347.8  102.65  5387.8  106.58  5397.8  106.98
  5407.8  108.42
#Mann= 5 , 1 , 0
  4209.3     .12       0  4328.1     .12       0  4562.2     .14       0
 4983.15    .045       0 5016.85     .14       0
Bank Sta=4983.15,5016.85
XS Rating Curve= 0
Exp/Cntr=.3,.1

Type RM Length L Ch R = 1 ,180980.0,457,457,457
BEGIN DESCRIPTION:
Cross Section Town Creek 8.0
END DESCRIPTION:
#Sta/Elev= 16
    4634  105.59    4724  100.88  4741.4  100.59    4904   97.91    4924   97.12
 4983.15    94.7 4987.05   94.31 4997.85   92.17 5014.55   94.11 5016.85   94.85
  5027.5   97.13  5137.5   97.36  5167.5   98.17  5257.5   105.7  5277.5  107.78
  5327.5  107.81
#Mann= 4 , 1 , 0
    4634     .12       0  4741.4     .14       0 4983.15    .045       0
 5016.85     .14       0
Bank Sta=4983.15,5016.85
XS Rating Curve= 0
Exp/Cntr=.3,.1

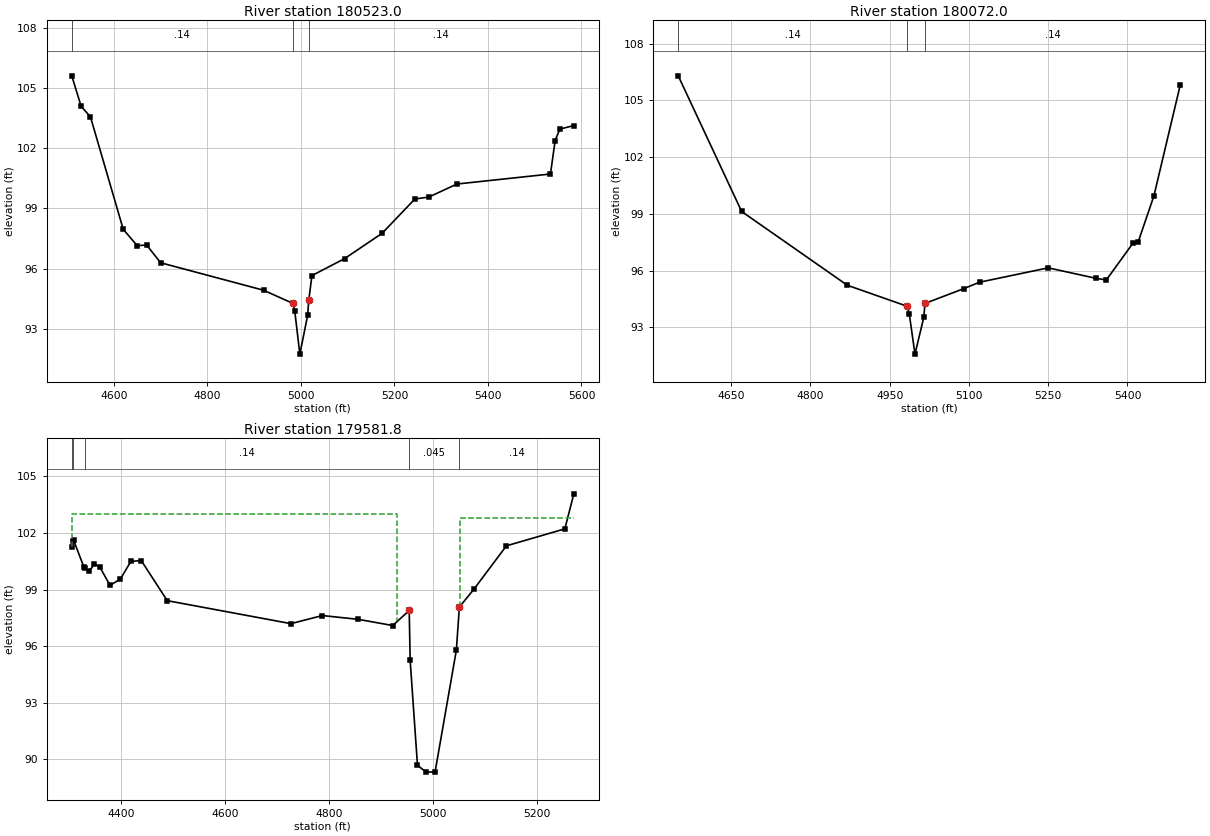
Type RM Length L Ch R = 1 ,180523.0,451,451,451
BEGIN DESCRIPTION:
Cross Section Town Creek 7.0
END DESCRIPTION:
#Sta/Elev= 23
  4510.2  105.62  4530.2   104.1  4550.2  103.57  4620.2   97.96  4650.2   97.14
  4670.2   97.18  4700.2   96.29  4920.2   94.92 4983.15   94.26 4987.05   93.87
 4997.85   91.73 5014.55   93.67 5016.85   94.41  5023.7   95.65  5093.7    96.5
  5173.7   97.76  5243.7   99.47  5273.7   99.57  5333.7  100.22  5533.7  100.72
  5543.7  102.39  5553.7  102.96  5583.7  103.14
#Mann= 3 , 1 , 0
  4510.2     .14       0 4983.15    .045       0 5016.85     .14       0
Bank Sta=4983.15,5016.85
XS Rating Curve= 0
Exp/Cntr=.3,.1

Type RM Length L Ch R = 1 ,180072.0,490.2,490.2,490.2
BEGIN DESCRIPTION:
Cross Section Town Creek 6.0
END DESCRIPTION:
#Sta/Elev= 17
  4549.9   106.3  4669.9   99.13  4869.9   95.23 4983.15   94.12 4987.05   93.73
 4997.85   91.59 5014.55   93.53 5016.85   94.27    5090   95.05    5120   95.39
    5250   96.15    5340    95.6    5360   95.51    5410   97.44    5420    97.5
    5450   99.95    5500  105.83
#Mann= 3 , 1 , 0
  4549.9     .14       0 4983.15    .045       0 5016.85     .14       0
Bank Sta=4983.15,5016.85
XS Rating Curve= 0
Exp/Cntr=.5,.3

Type RM Length L Ch R = 1 ,179581.8,62,62,62
BEGIN DESCRIPTION:
Upstream Section of Bridge/Culvert/Weir
END DESCRIPTION:
#Sta/Elev= 28
  4305.3  101.26  4308.4  101.58  4308.8  101.62  4328.8  100.18  4331.2  100.13
  4338.8   99.97  4348.8  100.35  4358.8  100.22  4378.8   99.22  4398.8   99.56
  4418.8  100.49  4438.8  100.54  4488.8   98.41  4726.5   97.19  4786.9   97.62
  4855.6   97.42  4922.2   97.09  4953.8   97.89  4955.6   95.25  4969.7   89.67
  4986.4   89.31  5003.5   89.32  5044.4   95.78  5050.2   98.07  5078.2   99.02
  5140.6  101.32  5252.9  102.22  5270.2  104.08
#Mann= 5 , 1 , 0
  4305.3      .2       0  4308.4     .12       0  4331.2     .14       0
  4953.8    .045       0  5050.2     .14       0
#XS Ineff= 2 , 0
       0    4931     103    5051       0   102.8
Permanent Ineff=
       F       F
Bank Sta=4953.8,5050.2
XS Rating Curve= 0
Exp/Cntr=.5,.3