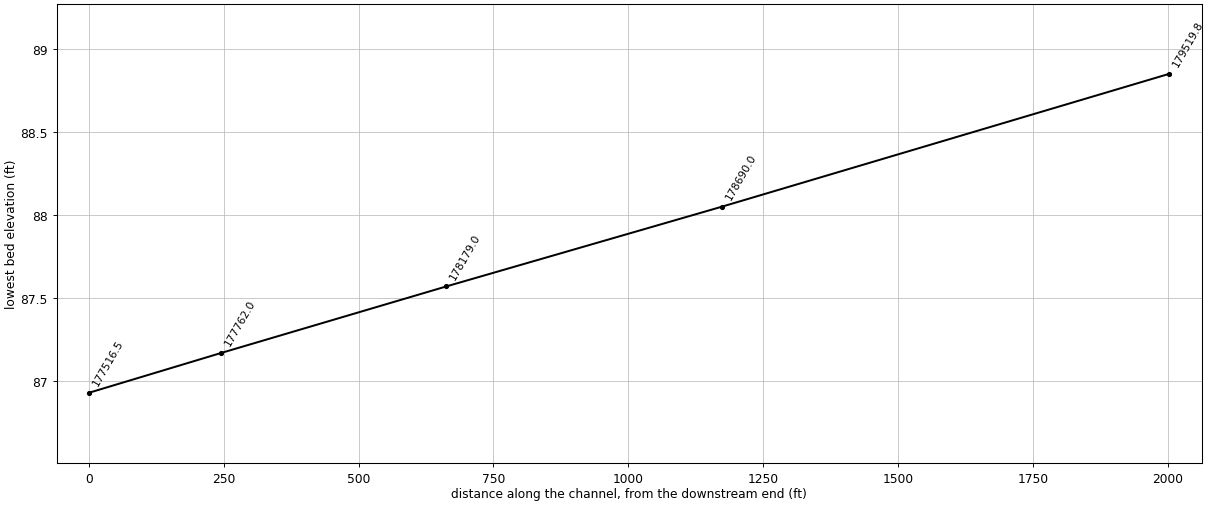
HEC-RAS study Town_Creek_FINAL.PRJ: Town Creek

--- Town_Creek_FINAL.g01 (geometry) --- (continued)

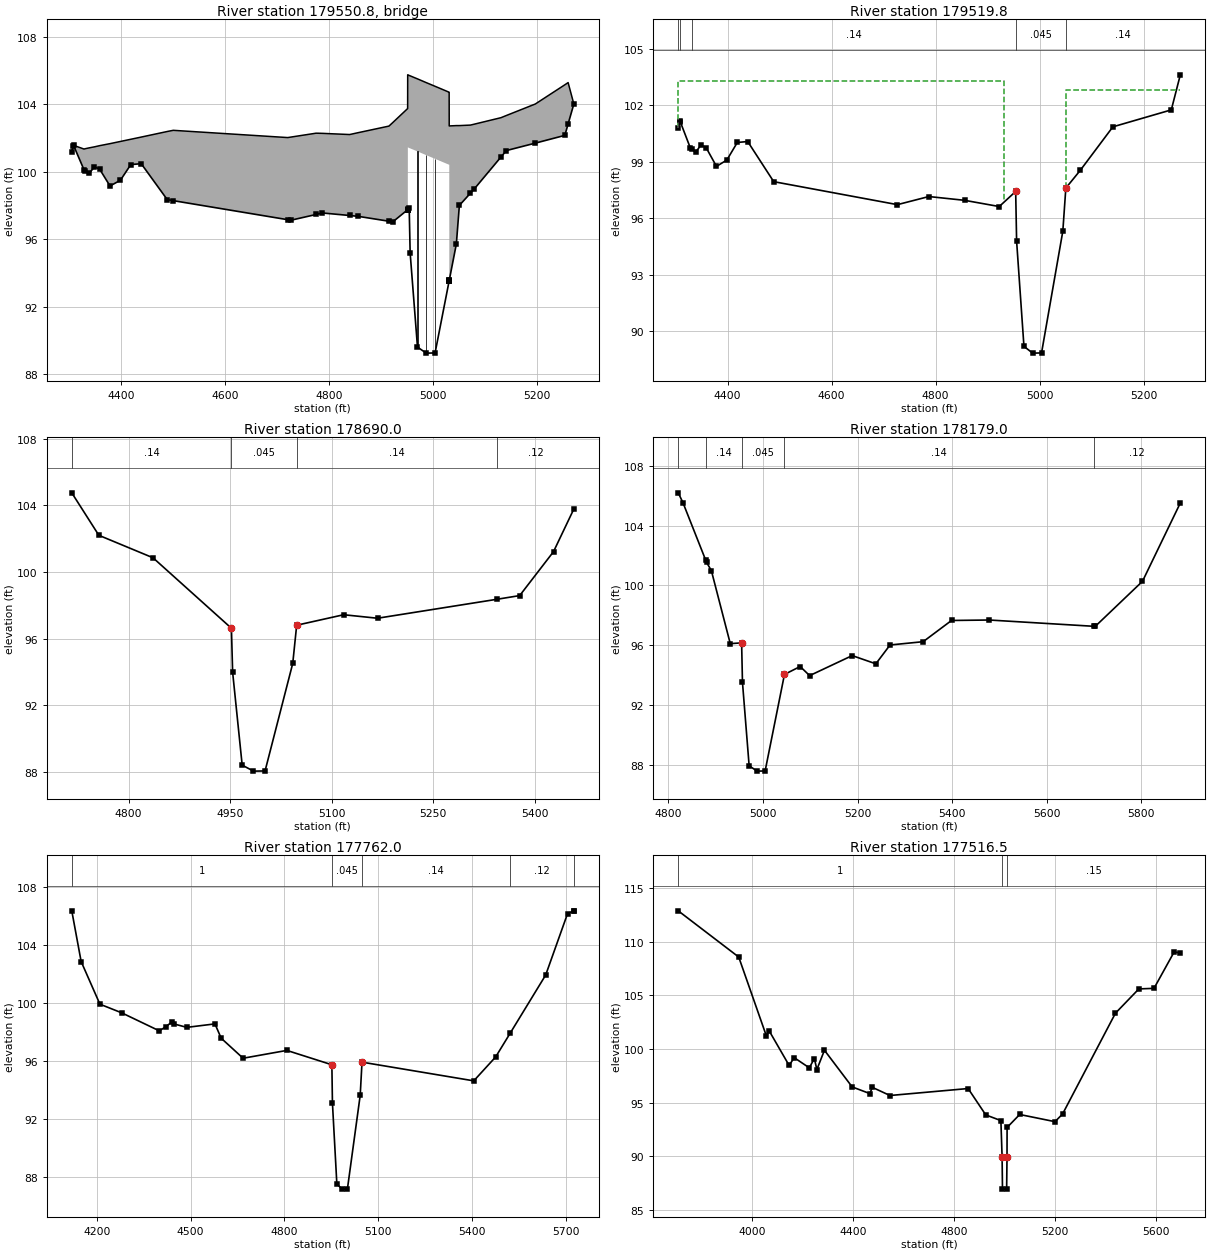
Type RM Length L Ch R = 3 ,179550.8,,,
BEGIN DESCRIPTION:
Bottoms Dairy Road
Structure ID: W_TOC-1
END DESCRIPTION:
Bridge Culvert--1,0,-1,-1, 0
Deck Dist Width WeirC Skew NumUp NumDn MinLoCord MaxHiCord MaxSubmerge Is_Ogee
10,42,2.6,0, 49, 49, , , .95, 0, 1,1,,
  4305.3  4308.4  4308.8  4328.8  4331.2  4338.8  4348.8  4358.8  4378.8  4398.8
  4418.8  4438.8  4488.8  4500.3  4720.4  4726.5  4774.9  4786.9  4839.3  4855.6
  4914.8  4922.2 4950.77 4950.88 4950.99 4951.11  4951.2  4951.3  4953.8  4955.6
  4969.7  4986.4  5003.5  5030.4 5030.46 5030.57 5030.68 5030.79  5030.9  5044.4
  5050.2  5071.4  5078.2  5130.2  5140.6  5196.1  5252.9  5259.2  5270.2
   101.2  101.53  101.57  101.35  101.37  101.42  101.48  101.55  101.67   101.8
  101.93  102.06  102.39  102.46  102.03  102.06  102.29  102.28  102.21  102.32
  102.71  102.92  103.75  105.75  105.75  105.75  105.75  105.75  105.71  105.69
  105.51  105.29  105.07  104.72  104.72  104.72  102.72  102.72  102.72  102.74
  102.74  102.77  102.82  103.21  103.34  104.02  105.16  105.29  104.02
   101.2  101.52  101.56  100.12  100.07   99.91  100.29  100.16   99.16    99.5
  100.43  100.48   98.35   98.29   97.16   97.13   97.47   97.56   97.41   97.36
   97.07   97.03   97.75   97.76   97.76   97.76  101.45  101.45  101.41  101.39
  101.21  100.99  100.77  100.42  100.42  100.42  100.42  100.42   93.59   95.72
   98.01   98.73   98.96  100.88  101.26   101.7  102.16  102.84  104.02
  4305.3  4308.4  4308.8  4328.8  4331.2  4338.8  4348.8  4358.8  4378.8  4398.8
  4418.8  4438.8  4488.8  4500.3  4720.4  4726.5  4774.9  4786.9  4839.3  4855.6
  4914.8  4922.2 4950.77 4950.88 4950.99 4951.11  4951.2  4951.3  4953.8  4955.6
  4969.7  4986.4  5003.5  5030.4 5030.46 5030.57 5030.68 5030.79  5030.9  5044.4
  5050.2  5071.4  5078.2  5130.2  5140.6  5196.1  5252.9  5259.2  5270.2
   101.2  101.53  101.57  101.35  101.37  101.42  101.48  101.55  101.67   101.8
  101.93  102.06  102.39  102.46  102.03  102.06  102.29  102.28  102.21  102.32
  102.71  102.92  103.75  105.75  105.75  105.75  105.75  105.75  105.71  105.69
  105.51  105.29  105.07  104.72  104.72  104.72  102.72  102.72  102.72  102.74
  102.74  102.77  102.82  103.21  103.34  104.02  105.16  105.29  104.02
  100.81  101.13  101.17   99.73   99.68   99.52    99.9   99.77   98.77   99.11
  100.04  100.09   97.96    97.9   96.77   96.74   97.08   97.17   97.02   96.97
   96.68   96.64   97.36   97.37   97.37   97.37  101.06  101.06  101.02     101
  100.82   100.6  100.38  100.03  100.03  100.03  100.03  100.03    93.2   95.33
   97.62   98.34   98.57  100.49  100.87  101.31  101.77  102.45  103.63
Pier Skew, UpSta & Num, DnSta & Num=  ,4969.7, 2 ,4969.7, 2 , 0 , 0 , 0 ,,
       1       1
    88.6  102.22
       1       1
   88.21  101.83
Pier Skew, UpSta & Num, DnSta & Num=  ,4986.4, 2 ,4986.4, 2 , 0 , 0 , 0 ,,
       1       1
   88.25     102
       1       1
   87.86  101.61
Pier Skew, UpSta & Num, DnSta & Num=  ,5003.5, 2 ,5003.5, 2 , 0 , 0 , 0 ,,
       1       1
   88.26  101.78
       1       1
   87.87  101.39
BR Coef= 1 , 1 , 0 ,1.25, 0 ,,,.8,0,2,0,
WSPro=,,,, 1 ,,,, 0 ,,,, 0 ,,,,-1 ,-1 ,-1 , 0 , 0 , 0 , 0 , 0
BR U #Sta/Elev= 49
  4305.3   101.2  4308.4  101.52  4308.8  101.56  4328.8  100.12  4331.2  100.07
  4338.8   99.91  4348.8  100.29  4358.8  100.16  4378.8   99.16  4398.8    99.5
  4418.8  100.43  4438.8  100.48  4488.8   98.35  4500.3   98.29  4720.4   97.16
  4726.5   97.13  4774.9   97.47  4786.9   97.56  4839.3   97.41  4855.6   97.36
  4914.8   97.07  4922.2   97.03 4950.77   97.75 4950.88   97.76 4950.99   97.76
 4951.11   97.76  4951.2   97.76  4951.3   97.77  4953.8   97.83  4955.6   95.19
  4969.7   89.61  4986.4   89.25  5003.5   89.26  5030.4   93.51 5030.46   93.52
 5030.57   93.54 5030.68   93.55 5030.79   93.57  5030.9   93.59  5044.4   95.72
  5050.2   98.01  5071.4   98.73  5078.2   98.96  5130.2  100.88  5140.6  101.26
  5196.1   101.7  5252.9  102.16  5259.2  102.84  5270.2  104.02
BR U #Mann= 5
  4305.3      .2  4308.4     .12  4331.2     .14  4953.8    .045  5050.2     .14
BR U Banks=4953.8,5050.2
BR D #Sta/Elev= 49
  4305.3  100.81  4308.4  101.13  4308.8  101.17  4328.8   99.73  4331.2   99.68
  4338.8   99.52  4348.8    99.9  4358.8   99.77  4378.8   98.77  4398.8   99.11
  4418.8  100.04  4438.8  100.09  4488.8   97.96  4500.3    97.9  4720.4   96.77
  4726.5   96.74  4774.9   97.08  4786.9   97.17  4839.3   97.02  4855.6   96.97
  4914.8   96.68  4922.2   96.64 4950.77   97.36 4950.88   97.37 4950.99   97.37
 4951.11   97.37  4951.2   97.37  4951.3   97.38  4953.8   97.44  4955.6    94.8
  4969.7   89.22  4986.4   88.86  5003.5   88.87  5030.4   93.12 5030.46   93.13
 5030.57   93.15 5030.68   93.16 5030.79   93.18  5030.9    93.2  5044.4   95.33
  5050.2   97.62  5071.4   98.34  5078.2   98.57  5130.2  100.49  5140.6  100.87
  5196.1  101.31  5252.9  101.77  5259.2  102.45  5270.2  103.63
BR D #Mann= 5
  4305.3      .2  4308.4     .12  4331.2     .14  4953.8    .045  5050.2     .14
BR D Banks=4953.8,5050.2
BC Design=,, 0 ,, 0 ,,,,,,

Type RM Length L Ch R = 1 ,179519.8,829.8,829.8,829.8
BEGIN DESCRIPTION:
Downstream Section of Bridge/Culvert/Weir
END DESCRIPTION:
#Sta/Elev= 28
  4305.3   100.8  4308.4  101.12  4308.8  101.16  4328.8   99.72  4331.2   99.67
  4338.8   99.51  4348.8   99.89  4358.8   99.76  4378.8   98.76  4398.8    99.1
  4418.8  100.03  4438.8  100.08  4488.8   97.95  4726.5   96.73  4786.9   97.16
  4855.6   96.96  4922.2   96.63  4953.8   97.43  4955.6   94.79  4969.7   89.21
  4986.4   88.85  5003.5   88.86  5044.4   95.32  5050.2   97.61  5078.2   98.56
  5140.6  100.86  5252.9  101.76  5270.2  103.62
#Mann= 5 , 1 , 0
  4305.3      .2       0  4308.4     .12       0  4331.2     .14       0
  4953.8    .045       0  5050.2     .14       0
#XS Ineff= 2 , 0
       0    4931   103.3    5051       0   102.8
Permanent Ineff=
       F       F
Bank Sta=4953.8,5050.2
XS Rating Curve= 0
Exp/Cntr=.5,.3

Type RM Length L Ch R = 1 ,178690.0,511,511,511
BEGIN DESCRIPTION:
Cross Section Town Creek 3.5
END DESCRIPTION:
#Sta/Elev= 16
    4716  104.76    4756  102.21    4836  100.86  4951.8   96.63  4953.6   93.99
  4967.7   88.41  4984.4   88.05  5001.5   88.06  5042.4   94.52  5048.2   96.81
  5117.6   97.44  5167.6   97.23  5344.3   98.37  5377.6   98.59  5427.6  101.23
  5457.6  103.79
#Mann= 4 , 1 , 0
    4716     .14       0  4951.8    .045       0  5048.2     .14       0
  5344.3     .12       0
Bank Sta=4951.8,5048.2
XS Rating Curve= 0
Exp/Cntr=.3,.1

Type RM Length L Ch R = 1 ,178179.0,417,417,417
BEGIN DESCRIPTION:
Cross Section Town Creek 3.0
END DESCRIPTION:
#Sta/Elev= 24
  4820.7  106.19  4830.7  105.53  4878.8  101.68  4880.7  101.53  4890.7  100.99
  4930.7    96.1  4954.7   96.15  4956.5   93.51  4970.6   87.93  4987.3   87.57
  5004.4   87.58  5045.3   94.04  5078.5   94.57  5098.5   93.96  5188.5    95.3
  5238.5   94.75  5268.5   96.01  5338.5   96.23  5398.5   97.65  5478.5   97.68
  5699.2   97.26  5702.2   97.25  5802.2  100.27  5882.2  105.51
#Mann= 5 , 1 , 0
  4820.7     .12       0  4878.8     .14       0  4954.7    .045       0
  5045.3     .14       0  5699.2     .12       0
Bank Sta=4954.7,5045.3
XS Rating Curve= 0
Exp/Cntr=.3,.1

Type RM Length L Ch R = 1 ,177762.0,245.5,245.5,245.5
BEGIN DESCRIPTION:
Cross Section Town Creek 2.0
END DESCRIPTION:
#Sta/Elev= 27
  4119.8  106.37  4149.8  102.87  4209.8   99.93  4279.8   99.33  4399.8   98.09
  4419.8   98.36  4439.8    98.7  4447.8   98.56  4487.8   98.33  4577.8   98.57
  4597.8   97.58  4667.8    96.2  4807.8   96.74  4951.8   95.75  4953.6   93.11
  4967.7   87.53  4984.4   87.17  5001.5   87.18  5042.4   93.64  5048.2   95.93
  5405.7   94.64  5475.7   96.29  5522.2   97.93  5635.7  101.94  5705.7  106.18
  5725.6  106.36  5725.8  106.36
#Mann= 5 , 1 , 0
  4119.8       1       0  4951.8    .045       0  5048.2     .14       0
  5522.2     .12       0  5725.6      .2       0
Bank Sta=4951.8,5048.2
XS Rating Curve= 0
Exp/Cntr=.3,.1

Type RM Length L Ch R = 1 ,177516.5,0,0,0
BEGIN DESCRIPTION:
Town Creek 1.0
END DESCRIPTION:
#Sta/Elev= 30
  3705.4  112.88  3945.4  108.57  4055.4  101.19  4065.4  101.72  4145.4   98.46
  4165.4   99.19  4225.4   98.24  4245.4   99.11  4255.4   98.08  4285.4   99.88
  4395.4   96.46  4465.4   95.84  4475.4   96.42  4545.4   95.66  4855.4   96.31
  4925.4   93.85  4985.4   93.32  4990.2   89.93  4991.7   86.93  5008.2   86.93
  5009.7   89.93    5010   92.68    5060   93.89    5200   93.22    5230   93.93
    5440  103.34  5532.8   105.6  5592.8  105.65  5672.8  109.05  5697.2  108.95
#Mann= 3 , 1 , 0
  3705.4       1       0  4990.2     .05       0  5009.7     .15       0
Bank Sta=4990.2,5009.7
XS Rating Curve= 0
Exp/Cntr=.3,.1

Chan Stop Cuts=-1